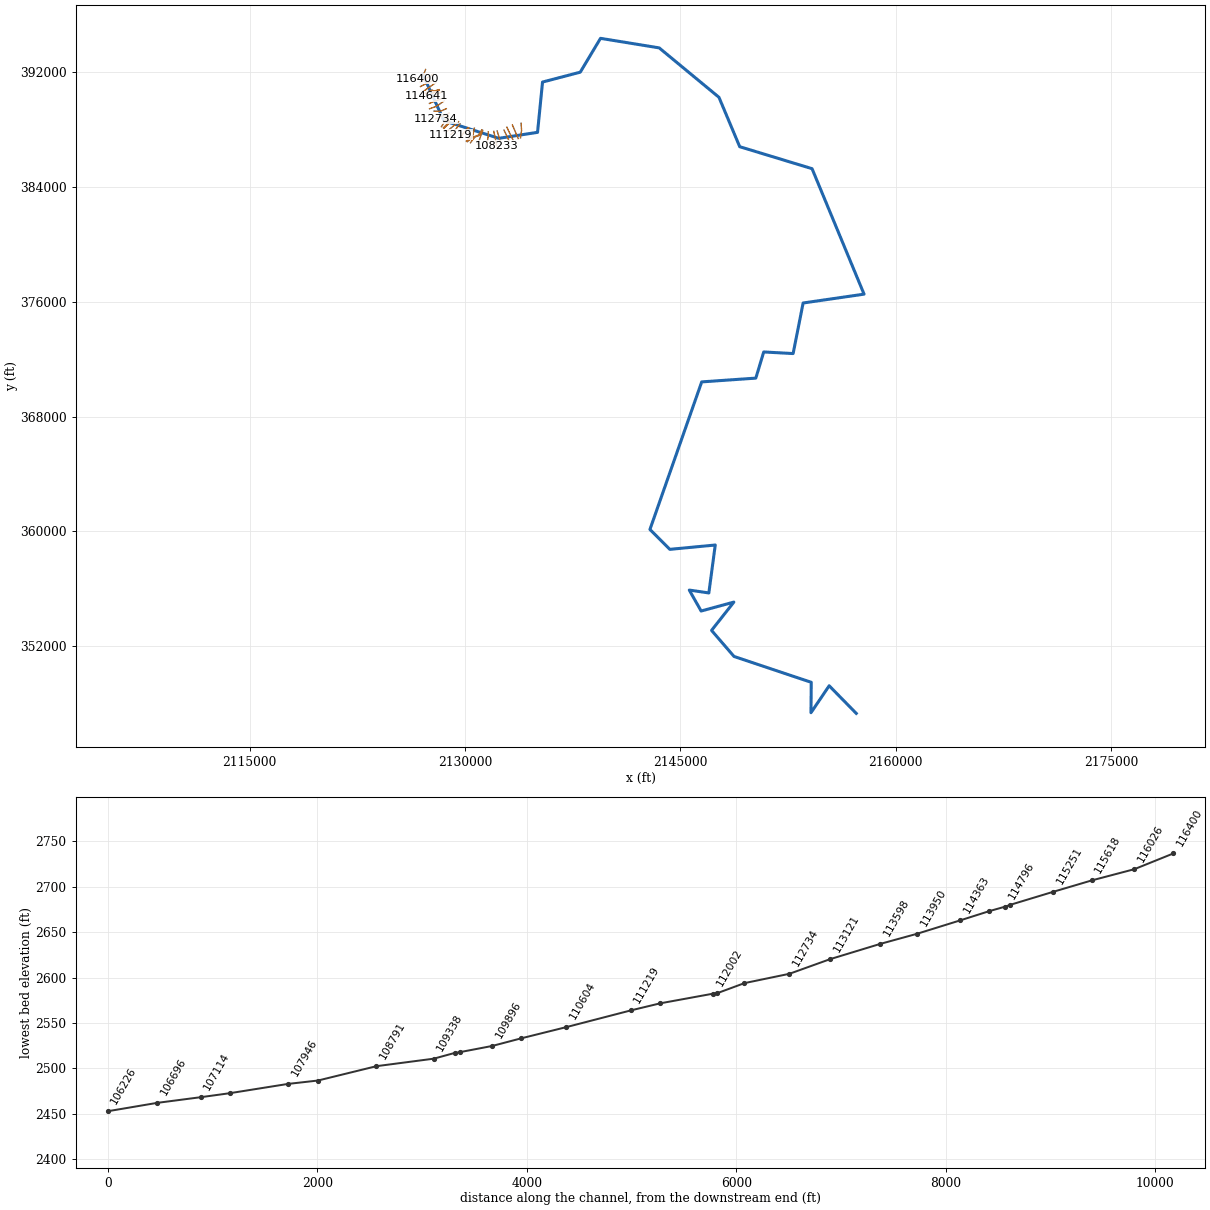
--- SPRINGCK.prj (project) ---

Proj Title=SPRINGCK
Current Plan=p01
Default Exp/Contr=0.3,0.1
English Units
Geom File=g01
Flow File=f01
Plan File=p01
Y Axis Title=Elevation
X Axis Title(PF)=Main Channel Distance
X Axis Title(XS)=Station
BEGIN DESCRIPTION:
Stream Name- Spring Creek
Flood Zone: Zone A
Greenbrier County, WV
County-Wide Study
WVDHSEM-2018-3, Flood Risk Project
HEC-RAS Version: 5.0.7
General Notes:
For the Hydrology regression was used.
END DESCRIPTION:
DSS Export Rating Curves= 0
DSS Export Rating Curve Sorted= 0
DSS Export Volume Flow Curves= 0
DXF Filename=A2a.
DXF OffsetX= 0
DXF OffsetY= 0
DXF ScaleX= 1
DXF ScaleY= 10

--- SPRINGCK.p01 (plan) ---

Plan Title=Floodplain
Program Version=5.07
Short Identifier=Floodplain
Geom File=g01
Flow File=f01
Subcritical Flow
K Sum by GR= 0
Std Step Tol= 0.01
Critical Tol= 0.01
Num of Std Step Trials= 20
Max Error Tol= 0.3
Flow Tol Ratio= 0.001
Split Flow NTrial= 30
Split Flow Tol= 0.02
Split Flow Ratio= 0.02
Log Output Level= 0
Friction Slope Method= 1
Unsteady Friction Slope Method= 2
Unsteady Bridges Friction Slope Method= 1
Parabolic Critical Depth
Global Vel Dist= 0 , 0 , 0
Global Log Level= 0
CheckData=True
Encroach Param=-1 ,0,0, 0
Computation Interval=1MIN
Output Interval=1HOUR
Instantaneous Interval=1HOUR
Mapping Interval=1HOUR
Computation Time Step Use Courant=        0
Computation Time Step Use Time Series=    0
Computation Time Step Count To Double=0
Computation Time Step Max Doubling=0
Computation Time Step Max Halving=0
Computation Time Step Residence Courant=0
Run HTab= 0
Run UNet= 0
Run Sediment= 0
Run PostProcess= 0
Run WQNet= 0
Run RASMapper= 0
UNET Theta= 1
UNET Theta Warmup= 1
UNET ZTol= 0.02
UNET ZSATol= 0.02
UNET MxIter= 20
UNET Max Iter WO Improvement= 0
UNET MaxInSteps= 0
UNET DtIC= 0
UNET DtMin= 0
UNET MaxCRTS= 20
UNET WFStab= 2
UNET SFStab= 1
UNET WFX= 1
UNET SFX= 1
UNET 1D Methodology=Finite Difference
UNET DSS MLevel= 4
UNET Pardiso=0
UNET DZMax Abort= 100
UNET Use Existing IB Tables=-1
UNET Froude Reduction=False
UNET Froude Limit= 0.8
UNET Froude Power= 4
UNET D1 Cores= 0
UNET D2 Coriolis=0
UNET D2 Cores= 0
UNET D2 Theta= 1
UNET D2 Theta Warmup= 1
UNET D2 Z Tol= 0.01
UNET D2 Volume Tol= 0.01
UNET D2 Max Iterations= 20
UNET D2 Equation= 0
UNET D2 RampUpFraction=0.1
UNET D2 TimeSlices= 1
UNET D2 BCVolumeCheck=0
UNET D1D2 MaxIter= 0
UNET D1D2 ZTol=0.01
UNET D1D2 QTol=0.1
UNET D1D2 MinQTol=1
Write IC File= 0
Write IC File at Fixed DateTime=0
Write IC File at Sim End=0
Echo Input=False
Echo Parameters=False
Echo Output=False
Write Detailed= 0
HDF Write Warmup=0
HDF Write Time Slices=0
HDF Flush=0
HDF Face Node Velocities=0
HDF Compression= 1
HDF Chunk Size= 1
HDF Spatial Parts= 1
HDF Use Max Rows=0
HDF Fixed Rows= 1
Calibration Method= 0
Calibration Iterations= 20
Calibration Max Change=0.05
Calibration Tolerance=0.2
Calibration Maximum=1.5
Calibration Minimum=0.5
Calibration Optimization Method= 1
WQ AD Non Conservative
WQ ULTIMATE=-1
WQ Max Comp Step=1HOUR
WQ Output Interval=15MIN
WQ Output Selected Increments= 0
WQ Output face flow=0
WQ Output face velocity=0
WQ Output face area=0
WQ Output face dispersion=0
WQ Output cell volume=0
WQ Output cell surface area=0
WQ Output cell continuity=0
WQ Output cumulative cell continuity=0
WQ Output face conc=0
WQ Output face dconc_dx=0
WQ Output face courant=0
WQ Output face peclet=0
WQ Output face adv mass=0
WQ Output face disp mass=0
WQ Output cell mass=0
WQ Output cell source sink temp=0
WQ Output nsm pathways=0
WQ Output nsm derived pathways=0
WQ Output MaxMinRange=-1
WQ Daily Max Min Mean=-1
WQ Daily Range=0
WQ Daily Time=0
WQ Create Restart=0
WQ Fixed Restart=0
WQ System Summary=0
WQ Write To DSS=0
WQ Use Fixed Temperature=0
Sorting and Armoring Iterations= 10
XS Update Threshold= 0.02
Bed Roughness Predictor= 0
Hydraulics Update Threshold= 0.02
Energy Slope Method= 1
Volume Change Method= 1
Sediment Retention Method= 0
XS Weighting Method= 0
Number of US Weighted Cross Sections= 1
Number of DS Weighted Cross Sections= 1
Upstream XS Weight=0
Main XS Weight=1
Downstream XS Weight=0
Number of DS XS's Weighted with US Boundary= 1
Upstream Boundary Weight= 1
Weight of XSs Associated with US Boundary= 0
Number of US XS's Weighted with DS Boundary= 1
Downstream Boundary Weight= 0.5
Weight of XSs Associated with DS Boundary= 0.5
Percentile Method= 0
Sediment Output Level= 3
Mass or Volume Output= 0
Output Increment Type= 1
Profile and TS Output Increment= 1
XS Output Flag= 0
XS Output Increment= 10
Write Gradation File= 0
Read Gradation Hotstart= 0
Write HDF5 File= 1
Write Binary Output= 1
Write DSS Sediment File= 0
SV Curve= 0
Specific Gage Flag= 0

--- SPRINGCK.f01 (steady flow) ---

Flow Title=Flow
Program Version=5.07
Number of Profiles= 6
Profile Names=f1p,f10p,f4p,f2p,f02p,f1pplus
River Rch & RM=SPRINGCK,Main            ,116400
     547     289     384     463     765     809
River Rch & RM=SPRINGCK,Main            ,114842
     614     325     432     520     857     908
River Rch & RM=SPRINGCK,Main            ,112305
     879     473     623     747    1220    1300
River Rch & RM=SPRINGCK,Main            ,109587
    1040     562     739     884    1430    1540
River Rch & RM=SPRINGCK,Main            ,108233
    1230     670     879    1050    1700    1820
River Rch & RM=SPRINGCK,Main            ,105252
    1710     943    1230    1460    2340    2530
River Rch & RM=SPRINGCK,Main            ,100185
    1910    1050    1370    1630    2600    2820
River Rch & RM=SPRINGCK,Main            ,97138
    2120    1180    1530    1820    2890    3140
River Rch & RM=SPRINGCK,Main            ,91518
    3120    1760    2270    2680    4220    4610
River Rch & RM=SPRINGCK,Main            ,84319
    3740    2120    2730    3210    5040    5520
River Rch & RM=SPRINGCK,Main            ,74913
    5110    2940    3750    4410    6840    7550
River Rch & RM=SPRINGCK,Main            ,72796
    6660    3870    4910    5760    8880    9850
River Rch & RM=SPRINGCK,Main            ,65895
    7650    4470    5660    6630   10200   11300
River Rch & RM=SPRINGCK,Main            ,50311
    8500    4990    6300    7370   11300   12600
River Rch & RM=SPRINGCK,Main            ,33430
   13000    7780    9760   11300   17200   19300
River Rch & RM=SPRINGCK,Main            ,31435
   14500    8710   10900   12700   19100   21500
Boundary for River Rch & Prof#=SPRINGCK,Main            , 1
Up Type= 0
Dn Type= 3
Dn Slope=0.001342
Boundary for River Rch & Prof#=SPRINGCK,Main            , 2
Up Type= 0
Dn Type= 3
Dn Slope=0.001342
Boundary for River Rch & Prof#=SPRINGCK,Main            , 3
Up Type= 0
Dn Type= 3
Dn Slope=0.001342
Boundary for River Rch & Prof#=SPRINGCK,Main            , 4
Up Type= 0
Dn Type= 3
Dn Slope=0.001342
Boundary for River Rch & Prof#=SPRINGCK,Main            , 5
Up Type= 0
Dn Type= 3
Dn Slope=0.001342
Boundary for River Rch & Prof#=SPRINGCK,Main            , 6
Up Type= 0
Dn Type= 3
Dn Slope=0.001342
DSS Import GetInterval= 0
DSS Import GetPeak= 0
DSS Import FillOption= 0

--- SPRINGCK.g01 (geometry) ---

Geom Title=Geometry
Program Version=5.07

River Reach=SPRINGCK        ,Main
Reach XY= 30
2127069.03172831391837.1649962932128528.10866848388624.376357064
 2132352.9605988 387394.110116812135053.40926614387811.597470805
2135400.41808656391316.6278623042138028.36755505 392004.09269473
2139436.52189097394363.1211131362143523.34016089393698.377035812
2147685.17337264390254.0400924832149130.64095414386810.944944561
2154167.66401656  385278.88239192157789.31458163376533.255198151
2153547.04616331375917.122572139 2152850.8920438372393.269383639
2150803.28918363372503.7793332342150251.37854205370680.972939476
2146484.29519697370418.8898022322142879.72563447360133.398890316
2144263.61459897358746.7323723142147428.05905747359048.398763731
2146981.39229989355708.3988820612145618.05906856355908.607143059
2146445.14238814354448.1904444842148723.55909114 355071.12128523
2147170.22558364353098.3434066472148734.56595889351281.422171727
2154111.30225264349481.0747225582154093.94106689347362.151138887
2155360.43394072 349238.887214812157246.23528722347315.069212064

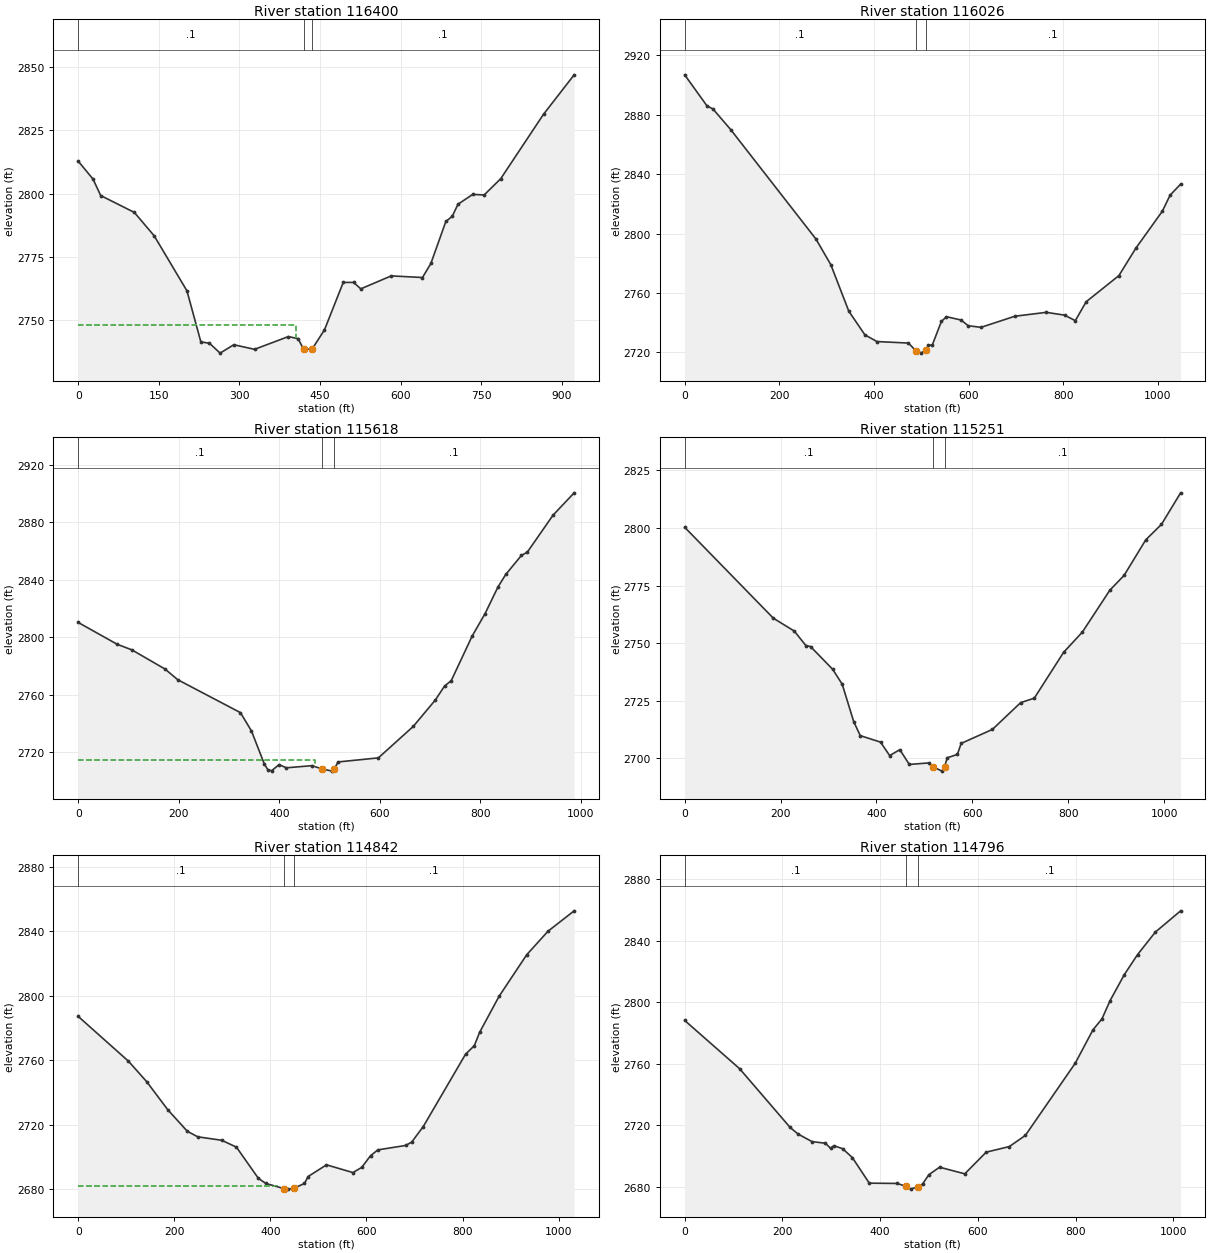
Type RM Length L Ch R = 1 ,116400  ,374.7,373.8,371.8
XS GIS Cut Line= 3
2127254.06922181392193.7547169772127118.90577821391826.541212559
2126669.57006273391542.014222562
#Sta/Elev= 30
       0 2812.84    27.6 2805.75    41.8 2799.24   104.5 2792.55   141.4 2783.29
   202.4  2761.5   228.3 2741.28   244.3 2740.76   264.1 2736.84   289.6 2740.16
   328.2 2738.34   391.1 2743.39   409.4 2742.56  419.362738.415  435.262738.416
   458.4 2746.06   493.3 2764.83   512.7 2764.84   525.9 2762.28   582.6 2767.42
   640.8 2766.78   656.4 2772.33   684.3 2788.98   696.2 2791.01   706.9  2795.8
   734.4  2799.7   755.6 2799.46   786.5 2805.93   866.1 2831.42   923.1 2847.03
#Mann= 3 ,-1 , 0
       0      .1       0  419.36    .045       0  435.26      .1       0
#XS Ineff= 2 , 0
          405.21 2747.79
Permanent Ineff=
       F       F
Bank Sta=419.36,435.26
XS Rating Curve= 0 ,0
Exp/Cntr=0.3,0.1

Type RM Length L Ch R = 1 ,116026  ,407,408.1,407.2
XS GIS Cut Line= 2
2127781.99467514391861.6503943062126884.84784739391319.791897982
#Sta/Elev= 30
       0 2906.92    47.4 2885.89    59.8 2883.93    97.2 2870.05   277.3 2796.35
   308.8 2779.05   346.8 2747.73   380.9 2731.74   406.3 2727.24   472.9 2726.22
  488.022721.203   499.7 2719.44  509.452721.661     515 2724.59   523.4    2725
   542.5 2740.77   553.3 2743.98     584 2741.74   599.3 2737.91   626.2  2736.8
   697.8  2744.3   764.2 2746.91     803 2745.02   825.5 2741.31   848.5 2754.05
   917.7 2771.68   953.5 2790.14  1009.5 2815.06  1025.9 2825.87  1048.1 2833.29
#Mann= 3 ,-1 , 0
       0      .1       0  488.02    .045       0  509.45      .1       0
Bank Sta=488.02,509.45
XS Rating Curve= 0 ,0
Exp/Cntr=0.3,0.1

Type RM Length L Ch R = 1 ,115618  ,362.3,367.2,367.7
XS GIS Cut Line= 2
 2127781.4087183391441.9415880592126896.65326998391005.309915394
#Sta/Elev= 30
       0 2810.38    77.5 2795.21   106.8 2791.32   172.7 2777.99   198.1 2770.56
   322.7  2747.7   344.6 2734.99   370.2 2712.05   377.5 2707.88   384.9 2707.35
   399.5 2711.56   414.1 2709.34   465.2 2710.83  485.122708.539   505.6 2707.03
  509.442708.308   516.7  2713.4   597.1 2716.24   666.6 2738.14   710.5  2756.5
   728.8  2766.2   742.1 2769.93   783.6 2800.88   809.3 2816.48   835.1 2835.09
   850.5 2843.74   881.7 2856.99   893.4 2859.24   944.6 2884.98   986.6  2900.5
#Mann= 3 ,-1 , 0
       0      .1       0  485.12    .045       0  509.44      .1       0
#XS Ineff= 2 , 0
          470.29 2714.76
Permanent Ineff=
       F       F
Bank Sta=485.12,509.44
XS Rating Curve= 0 ,0
Exp/Cntr=0.3,0.1

Type RM Length L Ch R = 1 ,115251  ,416.7,408.8,395.7
XS GIS Cut Line= 4
2127958.87555496391265.8612315652127586.69683738391007.542194396
2127297.63409531390804.4172725682127111.69680314390672.472654566
#Sta/Elev= 30
       0 2800.35   184.8  2760.9   228.8 2755.26   252.7 2749.01   262.5 2748.57
   308.6 2738.72   328.5 2732.24   352.6 2715.95   366.2 2709.91   408.5  2707.1
   427.5 2701.26   448.7 2703.82   468.5 2697.41   508.6 2698.06     517 2696.48
   536.6 2694.51  541.95 2696.43   547.6  2700.3   568.7 2701.76   576.7 2706.55
   641.8 2712.62   700.7 2724.24   729.1 2726.17   790.2 2746.05   829.4 2754.86
   886.7 2773.03   916.4 2779.46   961.7 2794.91   994.4 2801.61  1034.3 2815.29
#Mann= 3 , 0 , 0
       0      .1       0     517    .045       0  541.95      .1       0
Bank Sta=517,541.95
XS Rating Curve= 0 ,0
Exp/Cntr=0.5,0.3

Type RM Length L Ch R = 1 ,114842  ,45.8,45.7,45.1
XS GIS Cut Line= 4
2128186.97155547390781.2224370542127840.53064731 390686.43095997
2127704.24581489390768.0279096372127243.61222172390539.338734478
#Sta/Elev= 30
       0 2787.23   104.6 2759.48   142.7 2746.74   186.4 2729.41   227.2 2716.03
   248.8 2712.63   298.7 2710.48   329.3 2706.24     375 2686.91   390.6  2683.7
  428.582680.537   437.5 2680.21  449.732680.879   470.9 2683.71   478.5    2688
   516.8 2695.26   571.8 2690.47   590.1 2693.66   608.4 2700.89   623.7 2704.53
   681.7 2707.28   694.2 2709.38   718.3 2719.01   806.2 2763.79   824.5  2769.1
   835.5 2777.34   875.8 2799.57   933.5 2825.41   977.8    2840  1032.3 2852.65
#Mann= 3 ,-1 , 0
       0      .1       0  428.58    .045       0  449.73      .1       0
#XS Ineff= 2 , 0
          418.58  2682.2  459.73          2682.2
Permanent Ineff=
       F       F
Bank Sta=428.58,449.73
XS Rating Curve= 0 ,0
Exp/Cntr=0.5,0.3

Type RM Length L Ch R = 1 ,114796  ,136.5,155.5,167.4
XS GIS Cut Line= 5
2128192.52699055390775.6670019782127834.45421588390659.347352728
2127794.52352147 390660.64951548 2127695.9994403390721.847555816
2127261.79788089390511.951650143
#Sta/Elev= 30
       0 2788.07   112.4 2756.66   215.6 2718.49   232.1 2714.12   260.5 2709.22
     288 2708.15   298.4 2704.93   305.3 2706.55   323.3  2704.6   343.2 2698.76
   377.7 2682.19   434.6 2681.99  453.262680.108   462.5  2678.3  477.662679.976
   486.7 2681.65   499.8 2687.76   521.5 2692.56   573.1 2688.26   616.9 2702.35
   664.2 2705.99     697 2713.23     799 2760.18   835.5 2782.02   853.7 2789.05
   870.4 2800.96   899.4 2817.82   926.6 2830.91     963 2845.54  1014.7 2859.38
#Mann= 3 ,-1 , 0
       0      .1       0  453.26    .045       0  477.66      .1       0
Bank Sta=453.26,477.66
XS Rating Curve= 0 ,0
Exp/Cntr=0.5,0.3

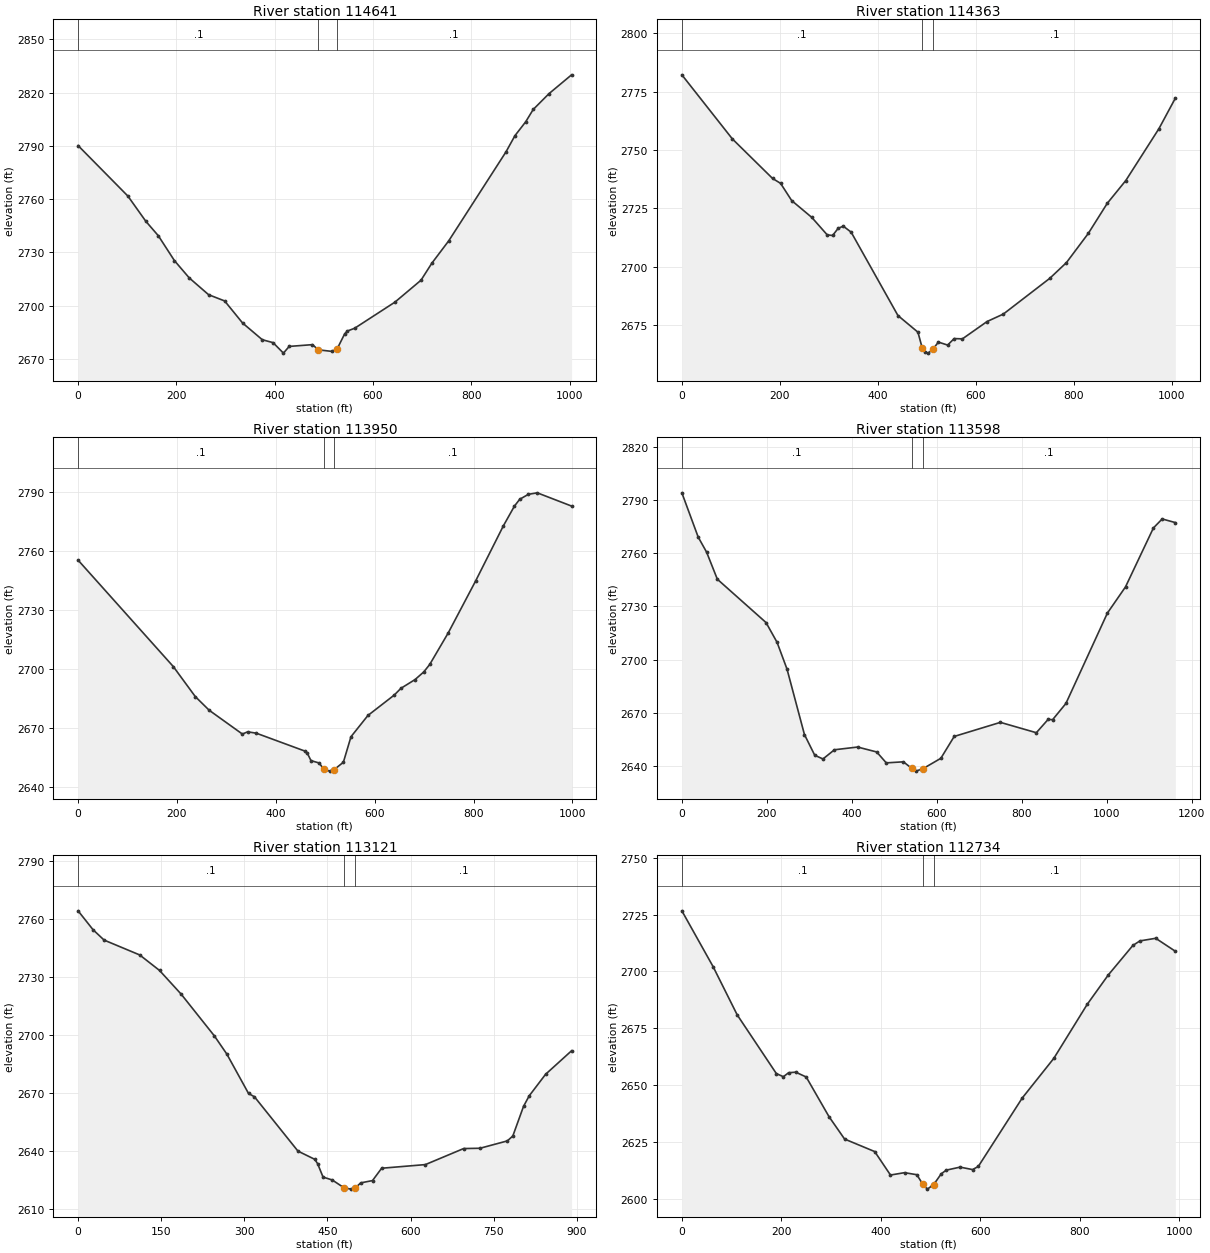
Type RM Length L Ch R = 1 ,114641  ,265.2,278,278
XS GIS Cut Line= 2
2128206.55977088390761.6043660642127303.17870364390323.397893399
#Sta/Elev= 30
       0 2790.18   101.3 2761.73   137.8 2747.53   163.3 2739.36   196.1 2725.33
   226.2  2715.6   265.5 2706.16   298.2 2702.63   334.7  2690.2   374.8 2680.78
   396.7 2679.14   417.8 2673.23   429.5 2677.01   476.9 2678.01     489 2675.08
     517 2674.19  526.562675.333   542.5 2684.14   547.9 2685.68   562.6 2687.23
   644.6 2701.95   697.7 2714.31   719.8 2723.91   754.2 2736.53   870.7 2786.66
   888.9 2795.77   910.8  2803.6     926 2810.51   958.2 2819.45  1004.1 2830.04
#Mann= 3 , 0 , 0
       0      .1       0     489    .045       0  526.56      .1       0
Bank Sta=489,526.56
XS Rating Curve= 0 ,0
Exp/Cntr=0.3,0.1

Type RM Length L Ch R = 1 ,114363  ,414.1,412.6,410.2
XS GIS Cut Line= 2
2128411.34676288390656.0707844792127539.02173589 390152.61116147
#Sta/Elev= 30
       0 2782.21     103 2754.78     185 2737.86   201.5 2735.73   224.2 2728.35
   265.1 2721.17   296.6 2713.69   307.6 2713.41   318.9 2716.45   329.4 2717.42
   345.5 2714.84     441 2679.14   481.8 2672.01  490.512665.283   495.7 2663.57
   502.9 2663.04   513.2 2664.92   523.5 2667.77   542.4 2666.49   555.8 2669.27
   572.6 2669.15     623 2676.58   656.1 2679.76   750.8 2695.05   784.9  2701.8
   829.6 2714.32   868.2 2727.18   906.1 2736.96   973.7 2759.16  1007.2 2772.22
#Mann= 3 , 0 , 0
       0      .1       0  490.51    .045       0   513.2      .1       0
Bank Sta=490.51,513.2
XS Rating Curve= 0 ,0
Exp/Cntr=0.3,0.1

Type RM Length L Ch R = 1 ,113950  ,348.1,352,353.2
XS GIS Cut Line= 2
2128453.90376438390196.7803644842127525.83016121389829.369681984
#Sta/Elev= 30
       0  2755.4   192.6 2701.35     237 2686.13   265.2 2679.16   332.3 2667.08
   342.9 2668.21   360.5 2667.52   459.3 2658.38   463.5 2657.43   471.1 2653.58
   487.5 2652.39  496.842649.317   508.7 2648.25  517.572648.949   536.6 2652.77
     552 2665.73   586.3 2676.53   639.3 2686.84   653.1 2690.32   681.6 2694.75
   699.3 2698.65   711.3 2702.44   748.7 2718.45     804 2744.78   860.4 2772.91
   882.7 2782.88   893.3 2786.32   910.9 2788.84   928.8 2789.59   998.2 2782.86
#Mann= 3 ,-1 , 0
       0      .1       0  496.84    .045       0  517.57      .1       0
Bank Sta=496.84,517.57
XS Rating Curve= 0 ,0
Exp/Cntr=0.3,0.1

Type RM Length L Ch R = 1 ,113598  ,480.6,477.2,471.4
XS GIS Cut Line= 4
2128543.28219455389998.7837132222128199.53222589389751.908550814
2127965.78203721389609.0961723922127528.18251872389453.815314978
#Sta/Elev= 30
       0 2794.09    38.5 2769.08    58.2 2760.64    83.5 2745.35   198.1 2720.91
   224.1 2709.74   247.5 2694.63   288.5 2657.74   312.7 2646.05   332.1 2643.95
   359.1 2649.14   413.7 2650.68   458.5  2647.9   481.1 2641.75   521.4 2642.34
  540.612638.731   550.3 2637.09   566.72638.351   609.5 2644.32     641 2656.66
   749.7  2664.6   834.3 2658.76   862.1 2666.28   872.6 2666.11   903.9 2675.25
  1001.5 2726.23  1044.2 2741.04  1109.9 2774.29  1130.5 2779.35  1161.5  2777.3
#Mann= 3 ,-1 , 0
       0      .1       0  540.61    .045       0   566.7      .1       0
Bank Sta=540.61,566.7
XS Rating Curve= 0 ,0
Exp/Cntr=0.3,0.1

Type RM Length L Ch R = 1 ,113121  ,383.9,387.2,388.9
XS GIS Cut Line= 4
2128699.91409914389458.7257382272128306.33778656389290.149303734
2128179.94860363389275.5659995682127845.53916746389295.357626647
#Sta/Elev= 30
       0  2764.2      27 2754.43    46.9 2749.08   111.2 2741.39   146.9 2733.39
   185.9 2721.15   245.9 2699.54   268.4 2690.14   307.5  2669.8   318.2 2668.07
   396.7 2639.99     427 2635.74   432.1 2633.53     442 2626.55   458.5 2625.07
  480.372620.927   492.9 2620.33  500.442621.084     510 2623.56   531.2 2624.75
   547.7 2631.13   626.6 2633.01   695.6  2641.3   725.2 2641.46   774.5 2645.26
   784.4 2647.81   803.7 2663.12   813.9 2668.55   843.5  2679.7   890.4 2691.86
#Mann= 3 ,-1 , 0
       0      .1       0  480.37    .045       0  500.44      .1       0
Bank Sta=480.37,500.44
XS Rating Curve= 0 ,0
Exp/Cntr=0.3,0.1

Type RM Length L Ch R = 1 ,112734  ,406.2,429.2,433.5
XS GIS Cut Line= 2
2128875.87929839389122.8113838142127954.00417364388754.755689472
#Sta/Elev= 30
       0 2726.68    62.8 2702.14   111.3 2680.91     190  2655.1   204.1  2653.7
   214.7 2655.45   228.9 2655.71   250.1 2653.58     296 2636.12   327.3 2626.28
   387.9 2620.77   419.6 2610.45   447.9 2611.49   472.6 2610.59  484.542606.437
   493.8 2604.25   506.6 2606.28   521.7 2610.99   531.8  2612.6   559.6 2613.93
   584.8 2612.85   596.3 2614.24   684.6 2644.33   748.2  2661.8   815.3 2685.54
   857.7 2698.47   907.1 2711.44   921.3 2713.45   953.1  2714.6   992.6 2708.89
#Mann= 3 , 0 , 0
       0      .1       0  484.54    .045       0   506.6      .1       0
Bank Sta=484.54,506.6
XS Rating Curve= 0 ,0
Exp/Cntr=0.3,0.1

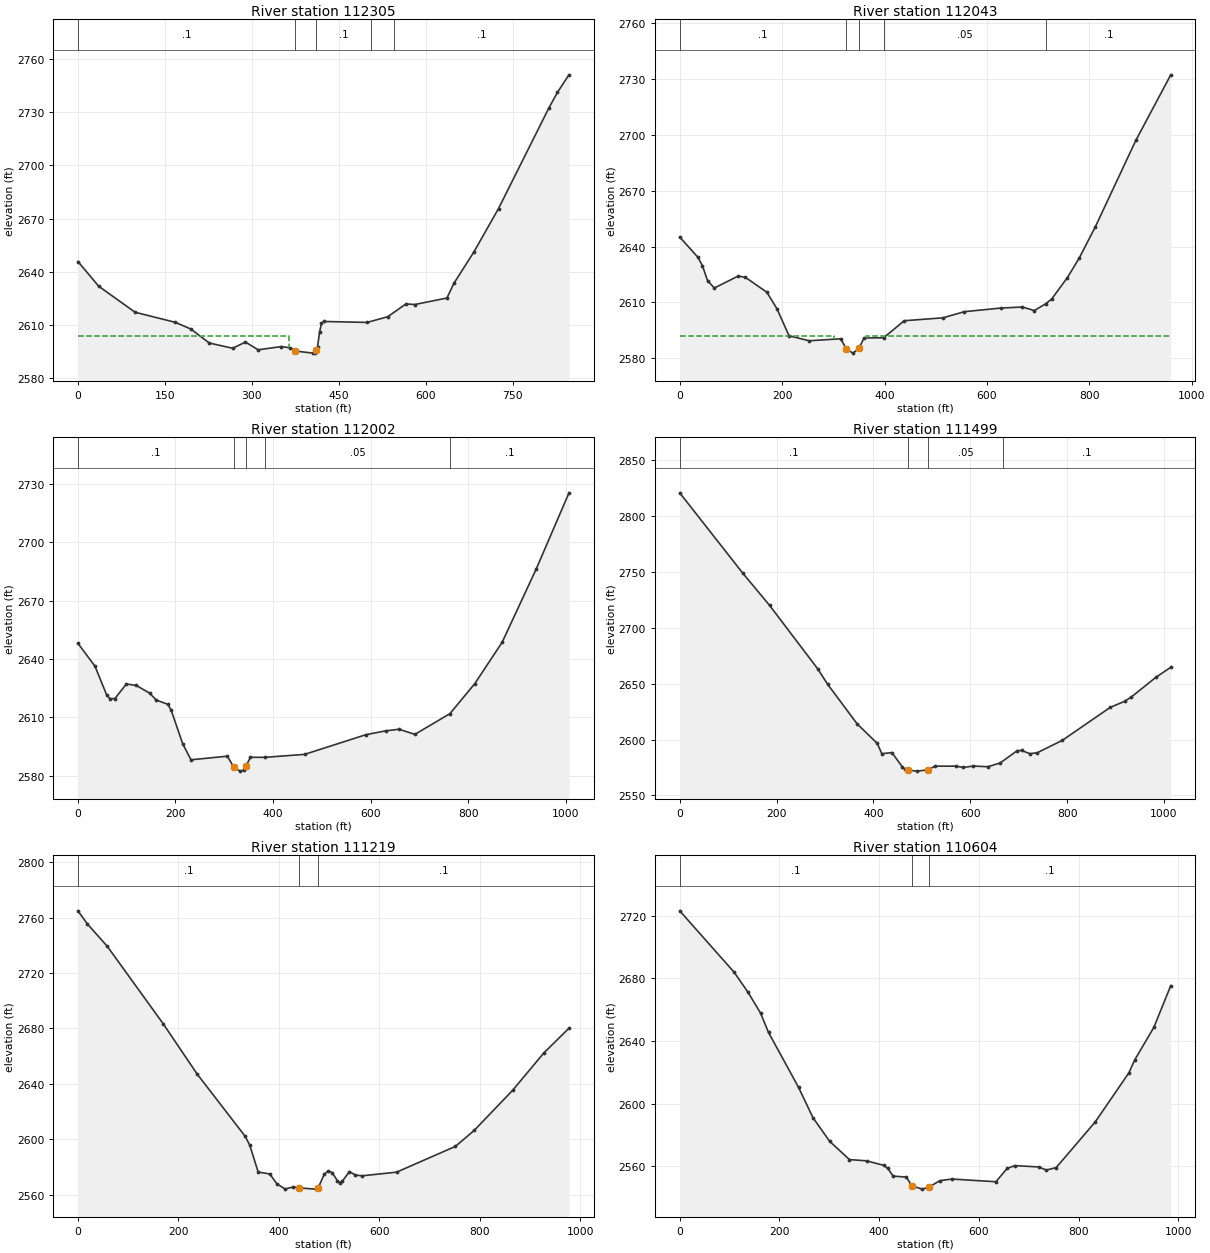
Type RM Length L Ch R = 1 ,112305  ,240.7,262.1,271
XS GIS Cut Line= 5
2128777.28894439388935.9272431432128606.22498205388591.326226309
2128597.52125931388573.3193725652128588.81786464388555.312190726
2128355.29241306 388202.99891898
#Sta/Elev= 30
       0 2645.69    35.8 2631.76    98.5 2617.08   168.1 2611.36   194.9 2607.58
   226.7 2599.68     267 2596.73     289 2600.23     311 2595.85   351.2  2597.7
   366.3 2596.96  374.942595.185   405.5 2593.98   409.7 2594.14  411.44 2595.59
   413.4 2597.56     417  2605.9   420.2 2610.79   424.7 2611.86     499 2611.32
   534.5 2614.52     566 2621.75   581.4 2621.44   636.8 2625.11   648.6 2633.32
   683.2 2651.08   725.8 2675.65   812.4 2732.26   827.5 2741.27   847.4 2751.15
#Mann= 5 ,-1 , 0
       0      .1       0  374.94    .045       0  411.44      .1       0
  504.99     .05       0  545.73      .1       0
#XS Ineff= 2 , 0
          365.03 2603.74
Permanent Ineff=
       F       F
Bank Sta=374.94,411.44
XS Rating Curve= 0 ,0
Exp/Cntr=0.5,0.3

Type RM Length L Ch R = 1 ,112043  ,43.1,40.1,36.3
XS GIS Cut Line= 5
2128791.57303655388924.3954420542128835.32327713388622.312384814
2128870.73987298388561.8955108972128854.76779206388486.895660892
2128497.12874356388127.173283234
#Sta/Elev= 30
       0 2645.13    35.6 2634.22    44.4 2629.68    54.3 2621.73    67.6 2617.76
   114.2 2624.18   128.2  2623.5   170.3 2615.47   190.2 2606.49   213.4 2592.15
   252.8 2589.45   314.5  2590.5  325.662584.929   338.5 2582.81   349.82585.334
   360.1 2590.92   398.4 2591.06   438.6 2600.21   514.1 2601.75     556 2605.06
   626.8 2606.99   669.5 2607.57   692.7 2605.66     715 2609.32   726.6 2611.88
   757.4  2623.4   780.6 2633.96   811.9 2650.64     891 2697.02   959.2 2732.18
#Mann= 5 ,-1 , 0
       0      .1       0  325.66    .045       0   349.8      .1       0
   398.4     .05       0     715      .1       0
#XS Ineff= 2 , 0
           301.7  2592.1   363.8          2592.1
Permanent Ineff=
       F       F
Bank Sta=325.66,349.8
XS Rating Curve= 0 ,0
Exp/Cntr=0.5,0.3

Type RM Length L Ch R = 1 ,112002  ,512.8,503.9,488.7
XS GIS Cut Line= 6
2128805.99459563388924.057516232 2128884.3277723388627.391114816
2128898.77229722388569.613015145 2128914.3277123 388507.39102672
2128904.32773231388450.7241453082128535.99447948388085.168774053
#Sta/Elev= 30
       0 2648.06    34.9 2636.28    58.6 2621.68    65.4 2619.59    75.6  2619.6
    99.3 2627.16   119.7 2626.38   147.1 2622.42   160.4  2618.9   184.2  2616.7
     191 2613.76   214.7 2596.45   231.7 2588.14   306.3 2589.99  319.372584.407
   332.5 2582.31   340.1 2582.83  344.452584.898   353.7 2589.44   383.1  2589.4
   464.8 2590.93   590.5 2601.06   630.7 2603.02   658.5 2603.86     691 2601.23
   762.9  2611.9   813.8 2627.33     870 2648.65   939.9 2686.38    1007  2725.5
#Mann= 5 ,-1 , 0
       0      .1       0  319.37    .045       0  344.45      .1       0
   383.1     .05       0   762.9      .1       0
Bank Sta=319.37,344.45
XS Rating Curve= 0 ,0
Exp/Cntr=0.5,0.3

Type RM Length L Ch R = 1 ,111499  ,274.7,279.3,283.8
XS GIS Cut Line= 2
2129553.49802189388555.3259702322128777.50351089387902.602866232
#Sta/Elev= 30
       0 2821.02     130 2749.14   185.7  2720.1   284.8 2663.42   305.5 2649.46
   366.4 2613.99     408 2596.48   417.3 2587.29   438.3 2588.28   459.2 2575.72
   464.4  2573.5  471.022572.618   489.5 2571.68  513.552572.837   526.7 2576.13
   570.3 2576.14   585.5 2574.98   605.9 2576.22   636.5 2575.64   661.8 2579.01
   696.7 2589.96     706 2590.18   723.2 2587.27   738.5  2588.2   789.9 2599.22
   888.8 2628.74   918.8 2634.26   932.1 2637.93   983.1 2655.66    1014 2664.73
#Mann= 4 ,-1 , 0
       0      .1       0  471.02    .045       0  513.55     .05       0
  667.45      .1       0
Bank Sta=471.02,513.55
XS Rating Curve= 0 ,0
Exp/Cntr=0.3,0.1

Type RM Length L Ch R = 1 ,111219  ,614.1,615,612.3
XS GIS Cut Line= 5
2129654.49388289388402.9640702312129420.11902355388109.214001566
2129346.16051005 388010.255866142129327.41054755387973.797605723
2129025.32716222387658.172580808
#Sta/Elev= 30
       0 2764.99    18.7  2755.5    58.4 2739.33   169.8 2683.29   237.1  2647.1
   332.8 2602.05   341.8 2595.76   358.6 2576.28   381.8 2574.84   395.9 2567.72
   412.3 2563.97   428.8 2565.53  438.962564.813   473.7 2563.91  478.212564.847
   490.1 2574.72   498.3 2577.06   505.8 2575.89   516.1 2570.06     521  2568.6
   525.8 2569.52   540.3 2576.59   552.3 2574.05   565.9 2573.56     634 2576.16
   751.1 2594.78   788.5 2606.32     865 2635.29   926.6 2662.09   977.2 2680.21
#Mann= 3 ,-1 , 0
       0      .1       0  438.96    .045       0  478.21      .1       0
Bank Sta=438.96,478.21
XS Rating Curve= 0 ,0
Exp/Cntr=0.3,0.1

Type RM Length L Ch R = 1 ,110604  ,418.7,432.9,443
XS GIS Cut Line= 2
2130200.38485147388132.9783897252129592.65050264387357.655793399
#Sta/Elev= 30
       0 2723.13   109.1 2683.97   137.1 2671.13   162.2 2657.84   178.1 2645.52
   238.3 2610.51   267.4 2591.06   300.6 2576.11   340.5 2564.37   374.9  2563.6
   409.2 2560.69   417.5 2558.74   428.1 2553.82   454.9 2553.23   465.3 2547.62
   486.6 2545.53   500.9 2547.01   521.7 2550.91     546 2551.97   634.3 2550.24
   656.8 2558.73   672.2 2560.53   720.6 2559.67   735.3 2557.68   755.2 2559.28
   833.5 2588.39   901.1 2619.77   912.9 2628.05   951.1  2648.7   985.1  2675.4
#Mann= 3 ,-1 , 0
       0      .1       0   465.3    .045       0   500.9      .1       0
Bank Sta=465.3,500.9
XS Rating Curve= 0 ,0
Exp/Cntr=0.3,0.1

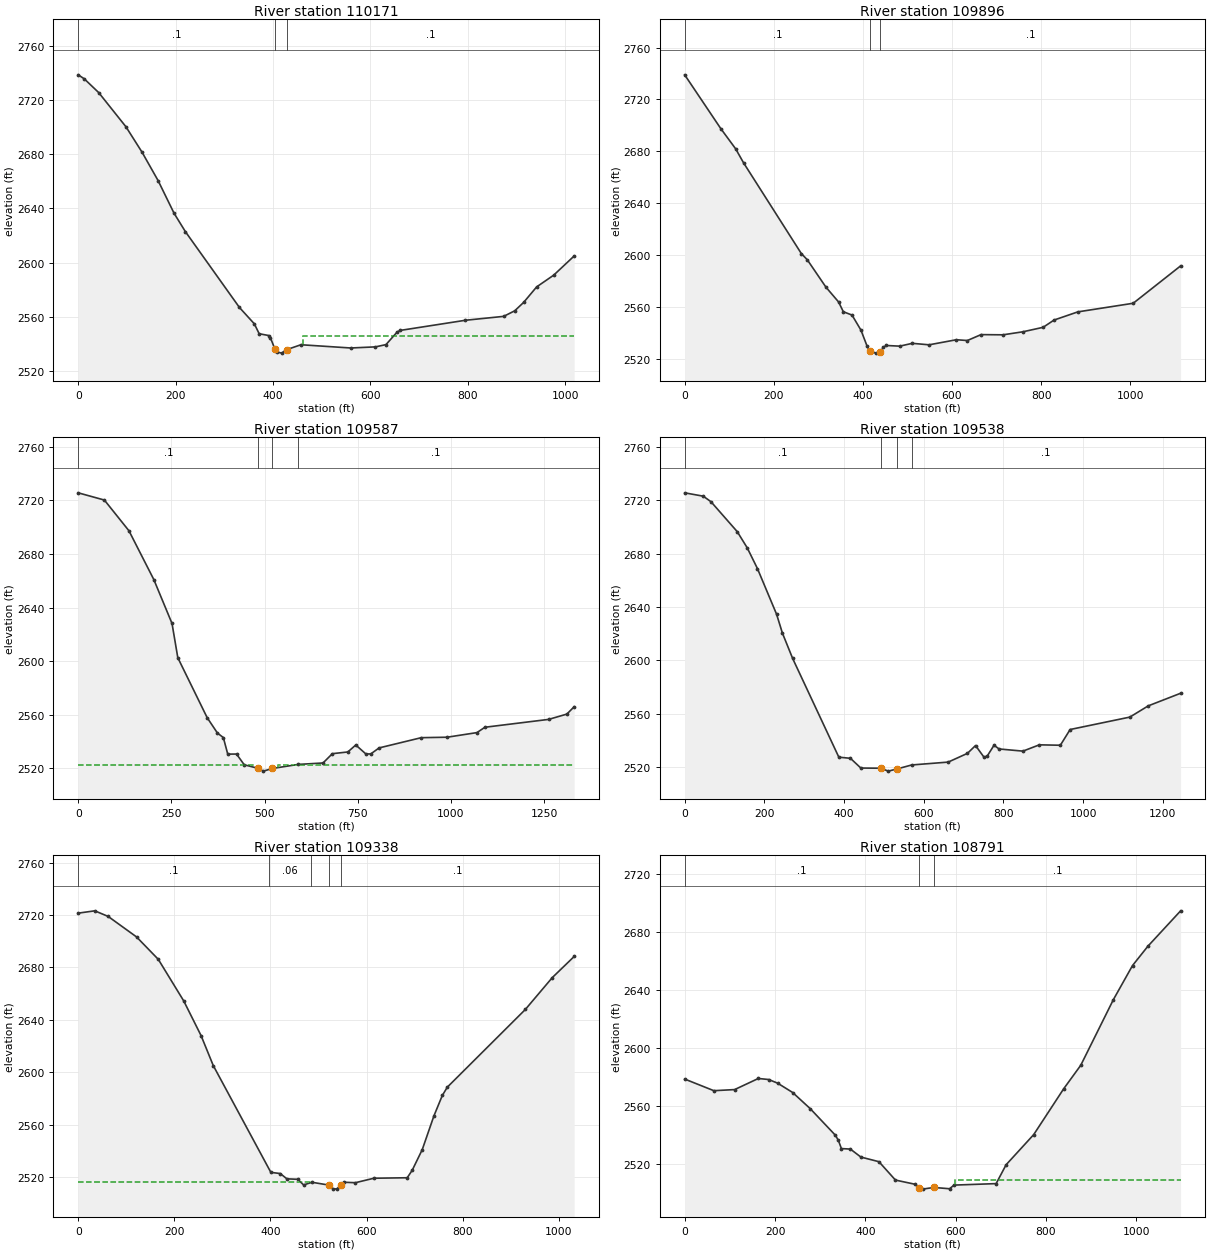
Type RM Length L Ch R = 1 ,110171  ,278.6,274.9,271.8
XS GIS Cut Line= 4
2130259.84109738388118.5197572262130325.32718688387438.380697563
 2130255.5356598387350.8808725632130094.07732131387196.714186147
#Sta/Elev= 30
       0 2738.78    12.4 2735.83      42 2725.68      98  2700.4     131 2681.65
     164 2660.64   196.9 2636.43     220 2622.94   331.1 2566.83   361.7 2554.74
   371.6 2547.44   391.4 2546.11   394.7 2544.48  404.11 2535.92   407.9 2534.02
   417.8 2533.11  428.282535.695   457.3 2539.31   559.5 2536.91   610.4 2537.73
     632 2539.41   655.1 2548.77   661.8 2549.93   795.2  2557.4   873.7 2560.28
   896.4  2564.4   914.6 2570.57   941.4 2582.06   976.4 2590.73  1018.4  2604.9
#Mann= 3 ,-1 , 0
       0      .1       0  404.11    .045       0  428.28      .1       0
#XS Ineff= 2 , 0
                          460.62         2545.99
Permanent Ineff=
       F       F
Bank Sta=404.11,428.28
XS Rating Curve= 0 ,0
Exp/Cntr=0.3,0.1

Type RM Length L Ch R = 1 ,109896  ,325.5,309,291.5
XS GIS Cut Line= 5
2130653.93479739388103.5315982252130561.48681955387647.802194729
 2130466.4348443387474.6253757332130259.40343422387319.677194804
2130117.47655272387190.770956561
#Sta/Elev= 30
       0 2738.98    80.9 2697.65   114.4 2682.02     132 2671.32   261.7 2601.45
   275.1 2596.64     317 2575.55   345.4 2564.14     356 2556.63   375.5 2554.07
   395.6 2542.44     409 2530.43   415.7  2526.2   429.1 2524.77   439.1 2525.79
   445.8 2529.25   452.5 2530.65   482.5 2530.14   510.9 2532.31   548.4 2531.17
   609.6 2535.07   634.4 2534.48     665 2539.02   714.2 2538.86   758.8 2541.18
   804.3 2544.64   828.9 2550.23   882.2 2556.52  1006.5 2563.15  1112.9 2591.92
#Mann= 3 , 0 , 0
       0      .1       0   415.7    .045       0   439.1      .1       0
Bank Sta=415.7,439.1
XS Rating Curve= 0 ,0
Exp/Cntr=0.5,0.3

Type RM Length L Ch R = 1 ,109587  ,54,49.4,51.3
XS GIS Cut Line= 6
2131166.41310313387968.9829828142130944.19077855387620.024691224
2130839.15621172387587.0385367272130633.42696439387501.969153062
2130479.78094622387414.2954438922130163.80880913387157.351075888
#Sta/Elev= 30
       0 2725.68    70.2 2720.28   136.1 2697.36   202.8 2660.96   251.7 2628.15
   267.2 2602.61     346 2557.83   373.5 2546.38   389.4 2542.96   401.2 2530.64
   424.8 2530.69   445.4 2522.68   483.3 2519.98     497 2517.94   521.1 2519.93
   590.4 2522.95   656.8 2524.02   681.9 2530.97   723.4 2532.25   744.7 2537.45
   771.8 2530.76     785 2530.79   807.3 2535.27   920.4 2542.91   989.6 2543.25
  1069.9  2546.7  1091.1 2550.69  1261.9 2556.55    1311 2560.51  1330.6    2566
#Mann= 4 ,-1 , 0
       0      .1       0   483.3    .045       0   521.1      .1       0
   590.4      .1       0
#XS Ineff= 2 , 0
           468.3  2522.3   536.1          2522.3
Permanent Ineff=
       F       F
Bank Sta=483.3,521.1
XS Rating Curve= 0 ,0
Exp/Cntr=0.5,0.3

Type RM Length L Ch R = 1 ,109538  ,179.6,199.6,212.1
XS GIS Cut Line= 6
2131190.71850072387954.2261225582131009.29497905387596.587074056
2130870.40614922 387553.184273722130696.79494789387487.211964726
2130549.22568922387310.1286574752130382.55902781387082.698338062
#Sta/Elev= 30
       0  2725.6    46.6 2723.09      66 2718.94   131.9 2696.52     157 2684.37
   182.7 2668.79   230.6 2634.67   245.3 2620.48     271 2601.48   386.9 2527.53
     416 2526.68   442.2 2519.37  491.572519.248   511.2 2517.07   533.62518.758
   569.8 2521.69   661.4 2523.84   709.7 2530.39     730 2536.24   751.2 2527.51
   759.3 2528.36   776.4 2536.46   789.2 2533.67     849 2532.06   890.1 2536.77
   942.9 2536.47   967.4 2548.25  1117.2 2557.55  1163.5 2565.98  1244.7 2575.42
#Mann= 4 ,-1 , 0
       0      .1       0  491.57    .045       0   533.6     .06       0
  569.98      .1       0
Bank Sta=491.57,533.6
XS Rating Curve= 0 ,0
Exp/Cntr=0.5,0.3

Type RM Length L Ch R = 1 ,109338  ,542.8,546.9,547
XS GIS Cut Line= 2
2131233.46152547387948.4594018162130892.42382172386974.664761484
#Sta/Elev= 30
       0 2721.36    34.5 2723.13    62.3 2718.85   121.4  2703.2   166.6 2686.11
   219.6 2654.33   255.6 2627.92     281 2605.03   400.8 2523.55   420.3 2522.66
   434.2 2518.61   456.5 2518.26     469 2513.96   486.4 2515.99  520.812513.886
   531.1 2510.76   538.8 2511.05  547.012514.219   552.4 2516.01   576.7 2515.66
     615 2519.07   684.5 2519.44   694.9 2525.16   715.8 2540.94   740.1 2566.69
   757.5 2582.22   767.9 2588.56   930.2 2647.84   986.4 2672.21  1031.8 2688.28
#Mann= 5 ,-1 , 0
       0      .1       0  396.22     .06       0  485.26      .1       0
  520.81    .045       0  547.01      .1       0
#XS Ineff= 2 , 0
          486.16 2516.16
Permanent Ineff=
       F       F
Bank Sta=520.81,547.01
XS Rating Curve= 0 ,0
Exp/Cntr=0.3,0.1

Type RM Length L Ch R = 1 ,108791  ,549.5,558.7,563.1
XS GIS Cut Line= 3
2131625.08771072387855.8322904712131611.19863088387504.443229482
2131487.58765763386768.332168892
#Sta/Elev= 30
       0 2578.41    64.6 2570.38   110.6 2571.14   163.1  2578.8   186.1 2578.08
   205.8 2575.57   239.1 2569.13     278 2557.99   333.9 2539.59   340.4 2536.04
     347 2530.46   366.9 2530.12   390.2  2524.6   430.1 2521.42   466.7 2508.74
   509.9 2505.87   519.8 2503.58   526.6  2502.5   551.8 2503.66   586.5 2502.76
   596.4 2505.28   689.6  2506.3   711.7 2519.31   772.8 2540.09   839.3 2571.75
     877 2587.91   949.1 2633.11   991.6 2656.68  1025.6 2669.99  1098.1 2694.41
#Mann= 3 , 0 , 0
       0      .1       0   519.8    .045       0   551.8      .1       0
#XS Ineff= 2 , 0
                          597.62         2508.54
Permanent Ineff=
       F       F
Bank Sta=519.8,551.8
XS Rating Curve= 0 ,0
Exp/Cntr=0.3,0.1

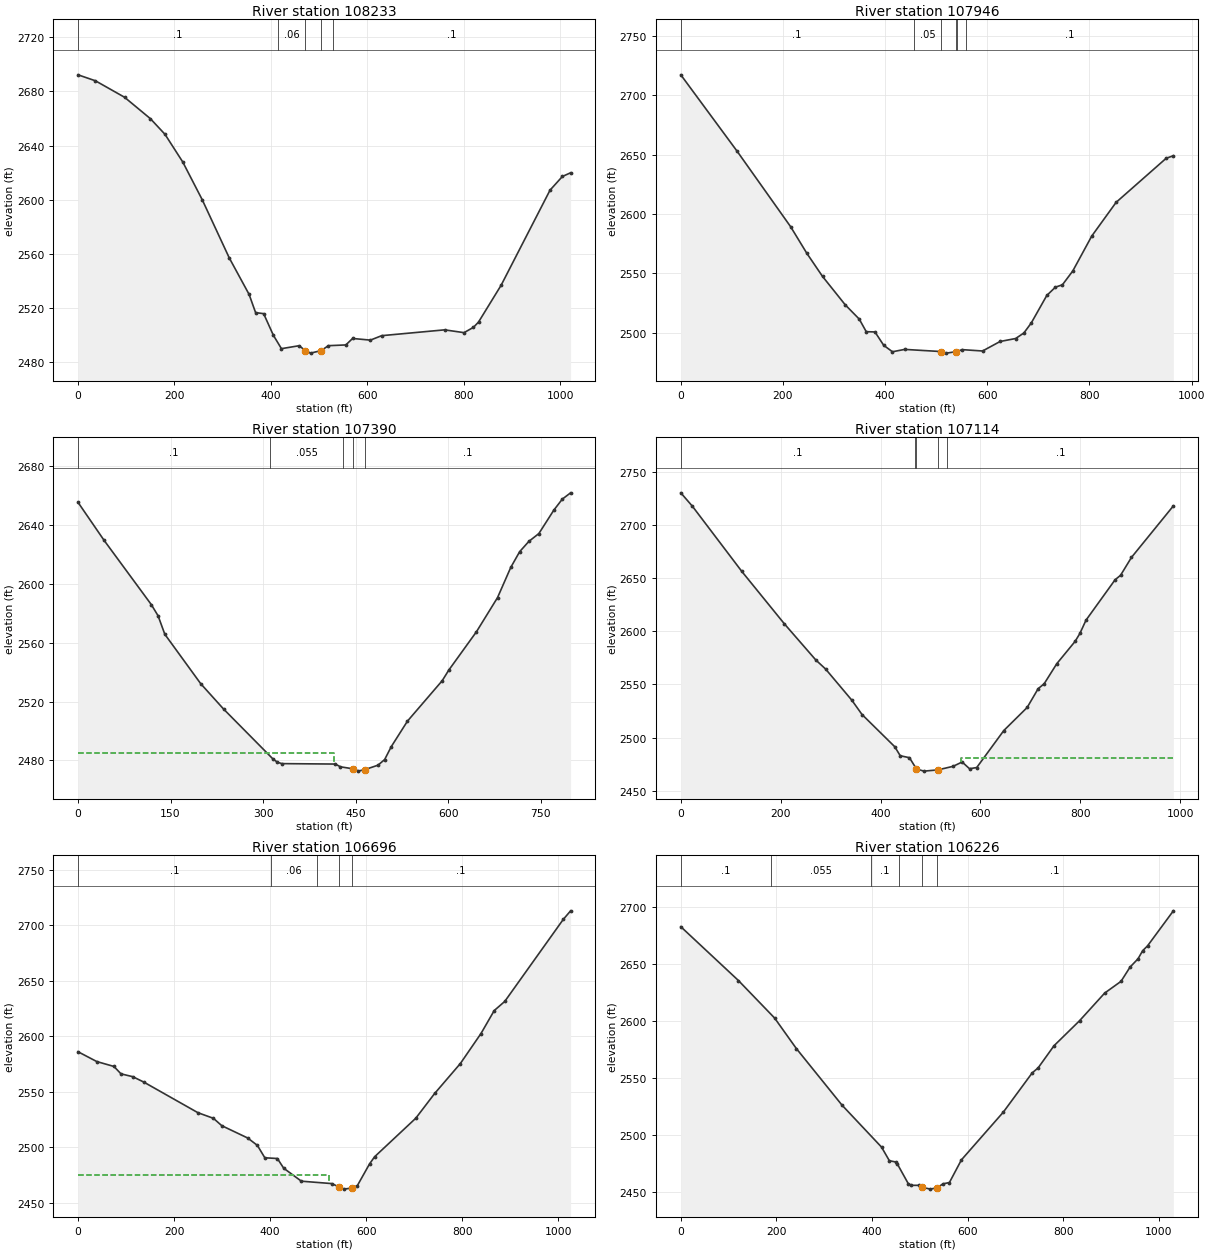
Type RM Length L Ch R = 1 ,108233  ,287.4,287.2,287.3
XS GIS Cut Line= 3
2132005.64305197387882.2210172272132122.30981338387337.776568055
 2132213.9766248386882.221048728
#Sta/Elev= 30
       0 2692.31      36 2687.91    96.4 2675.75   150.1 2659.89   180.3 2648.37
   217.2 2627.89   257.4 2600.12   313.7 2556.97   354.7 2530.11   368.2 2516.64
   384.9 2515.85   405.1 2499.86   421.8 2489.99   458.7 2492.18  471.65 2488.43
   482.2 2486.69   504.42488.574   519.1 2492.19   555.3 2492.74   569.4 2497.52
   606.3  2496.3   629.7 2499.59   760.2 2503.89   800.5 2501.82     820 2505.75
   830.5 2509.63   877.3 2536.78   978.8 2607.09  1004.5 2617.23  1021.5 2619.94
#Mann= 5 ,-1 , 0
       0      .1       0  415.15     .06       0  471.65    .045       0
   504.4     .06       0  528.68      .1       0
#XS Ineff= 2 , 0
             457 2491.47
Permanent Ineff=
       F       F
Bank Sta=471.65,504.4
XS Rating Curve= 0 ,0
Exp/Cntr=0.3,0.1

Type RM Length L Ch R = 1 ,107946  ,553.7,556,557
XS GIS Cut Line= 3
2132243.14323314387903.0543088912132380.64328621387439.165472895
2132500.08760114386973.887860149
#Sta/Elev= 30
       0 2717.17   109.8 2653.12     215 2589.33   246.6 2567.03   277.4 2547.52
   321.9 2523.58   349.3 2511.59     363 2500.99   380.1 2500.77   397.2 2489.51
   414.3 2484.09   438.3 2486.08  509.742484.262     520 2482.94  539.392484.189
   540.3 2484.21   550.5 2485.88   590.7 2484.74     625 2492.74   655.4 2495.23
   671.5 2499.86     686  2508.3   716.5 2531.52   733.4 2538.49     747 2540.45
   767.3 2552.09   804.5 2581.52   852.1 2609.83   950.2 2646.97   964.2 2649.05
#Mann= 6 ,-1 , 0
       0      .1       0  455.76     .05       0  509.74    .045       0
  539.39     .05       0   540.3     .06       0  558.43      .1       0
Bank Sta=509.74,539.39
XS Rating Curve= 0 ,0
Exp/Cntr=0.3,0.1

Type RM Length L Ch R = 1 ,107390  ,277.5,275.6,272.5
XS GIS Cut Line= 3
2132716.75416255387966.9432887292132901.47656214387587.776724234
2133054.25414371 387243.33220315
#Sta/Elev= 30
       0 2655.51    42.1 2629.76   118.8 2585.97   129.7 2578.42   140.7  2565.8
   198.9 2532.18     236 2514.92   315.8 2481.07   323.1 2478.79   330.4 2477.82
   417.3 2477.52   425.3 2475.66  445.542474.309     454 2472.71  465.542473.808
   486.3 2476.76   497.1 2480.57   507.8 2489.35   534.1 2506.73   590.4 2534.21
   601.1 2541.43     646 2567.55   680.1 2590.73   701.6  2611.3     716 2621.98
   730.9 2628.98   747.1 2634.29   771.4 2650.25   785.2 2657.76   798.6 2662.01
#Mann= 5 ,-1 , 0
       0      .1       0  311.05    .055       0  429.66      .1       0
  445.54    .045       0  465.54      .1       0
#XS Ineff= 2 , 0
          415.17 2485.18
Permanent Ineff=
       F       F
Bank Sta=445.54,465.54
XS Rating Curve= 0 ,0
Exp/Cntr=0.3,0.1

Type RM Length L Ch R = 1 ,107114  ,418.4,417.9,411.4
XS GIS Cut Line= 2
2132915.36531389388166.9432168162133345.92088322387279.443351388
#Sta/Elev= 30
       0 2730.63    23.3 2717.95   122.2 2656.55   207.4 2607.17   270.4 2573.07
   289.9  2564.6   342.5 2535.18   362.9 2521.71   428.5 2491.32   439.4 2482.85
   457.9 2480.99  471.912470.384   486.8 2468.34  514.512469.475   545.2 2472.85
   563.4 2476.94   578.2 2470.61   592.6 2471.72   646.9 2506.63   693.6 2528.32
   715.7 2546.11   727.5 2550.57     753 2569.62   789.5 2590.56   799.2 2598.07
   811.4 2610.59   869.7 2648.69   880.7 2652.95   902.5 2669.78   986.4 2718.32
#Mann= 5 ,-1 , 0
       0      .1       0  469.72     .06       0  471.91    .045       0
  514.51     .06       0  533.37      .1       0
#XS Ineff= 2 , 0
                           561.4          2480.9
Permanent Ineff=
       F       F
Bank Sta=471.91,514.51
XS Rating Curve= 0 ,0
Exp/Cntr=0.3,0.1

Type RM Length L Ch R = 1 ,106696  ,474.2,470,461.4
XS GIS Cut Line= 2
2133302.86552314 388322.499008062133707.09010839387380.282388553
#Sta/Elev= 30
       0 2585.87      39 2577.04    74.7 2572.63    89.4 2565.96     114 2563.39
   136.9 2558.53   249.6 2530.93   281.8 2525.88   299.2 2519.24   353.1 2508.15
   373.3 2501.48   388.8 2490.32   414.9 2489.66   428.1  2480.9   464.9 2469.21
   528.1 2467.06  543.692463.956   553.1 2462.06  569.962463.011   581.4 2465.23
   606.8  2484.8   617.3 2491.23     703 2525.96   742.3 2548.27   795.8 2575.26
   838.7 2602.28   866.3    2623   888.2 2631.23    1010 2705.16  1025.3 2712.89
#Mann= 5 ,-1 , 0
       0      .1       0  401.13     .06       0  496.49      .1       0
  543.69    .045       0  569.96      .1       0
#XS Ineff= 2 , 0
          521.56  2474.5
Permanent Ineff=
       F       F
Bank Sta=543.69,569.96
XS Rating Curve= 0 ,0
Exp/Cntr=0.3,0.1

Type RM Length L Ch R = 1 ,106226  ,497.3,500.4,497.6
XS GIS Cut Line= 5
2133906.46569389388449.5683077282133940.87179305 387949.47055465
2133937.46071064387929.7635730652133934.04995631387910.056591481
2133865.39753455387425.962743387
#Sta/Elev= 30
       0 2682.78   120.5 2635.64   196.2 2602.76   241.6 2576.07     337 2526.54
   419.8  2489.7   436.2 2477.77   449.4 2476.65   452.7 2475.06   475.7 2457.72
   482.3 2456.21   498.7  2456.2   505.3 2454.45     522 2452.87     536 2454.13
   548.6 2457.52   561.8 2458.65   586.9  2478.5   674.5 2520.31   734.9 2554.68
   747.4 2559.12   780.6 2578.51   833.9 2600.36   886.6 2624.66   920.7 2634.91
   939.6 2647.38   956.2 2654.62   966.1 2661.82   976.1 2665.94  1030.2 2696.69
#Mann= 6 ,-1 , 0
       0      .1       0  188.46    .055       0  397.52      .1       0
  455.69     .06       0   505.3    .045       0     536      .1       0
Bank Sta=505.3,536
XS Rating Curve= 0 ,0
Exp/Cntr=0.3,0.1