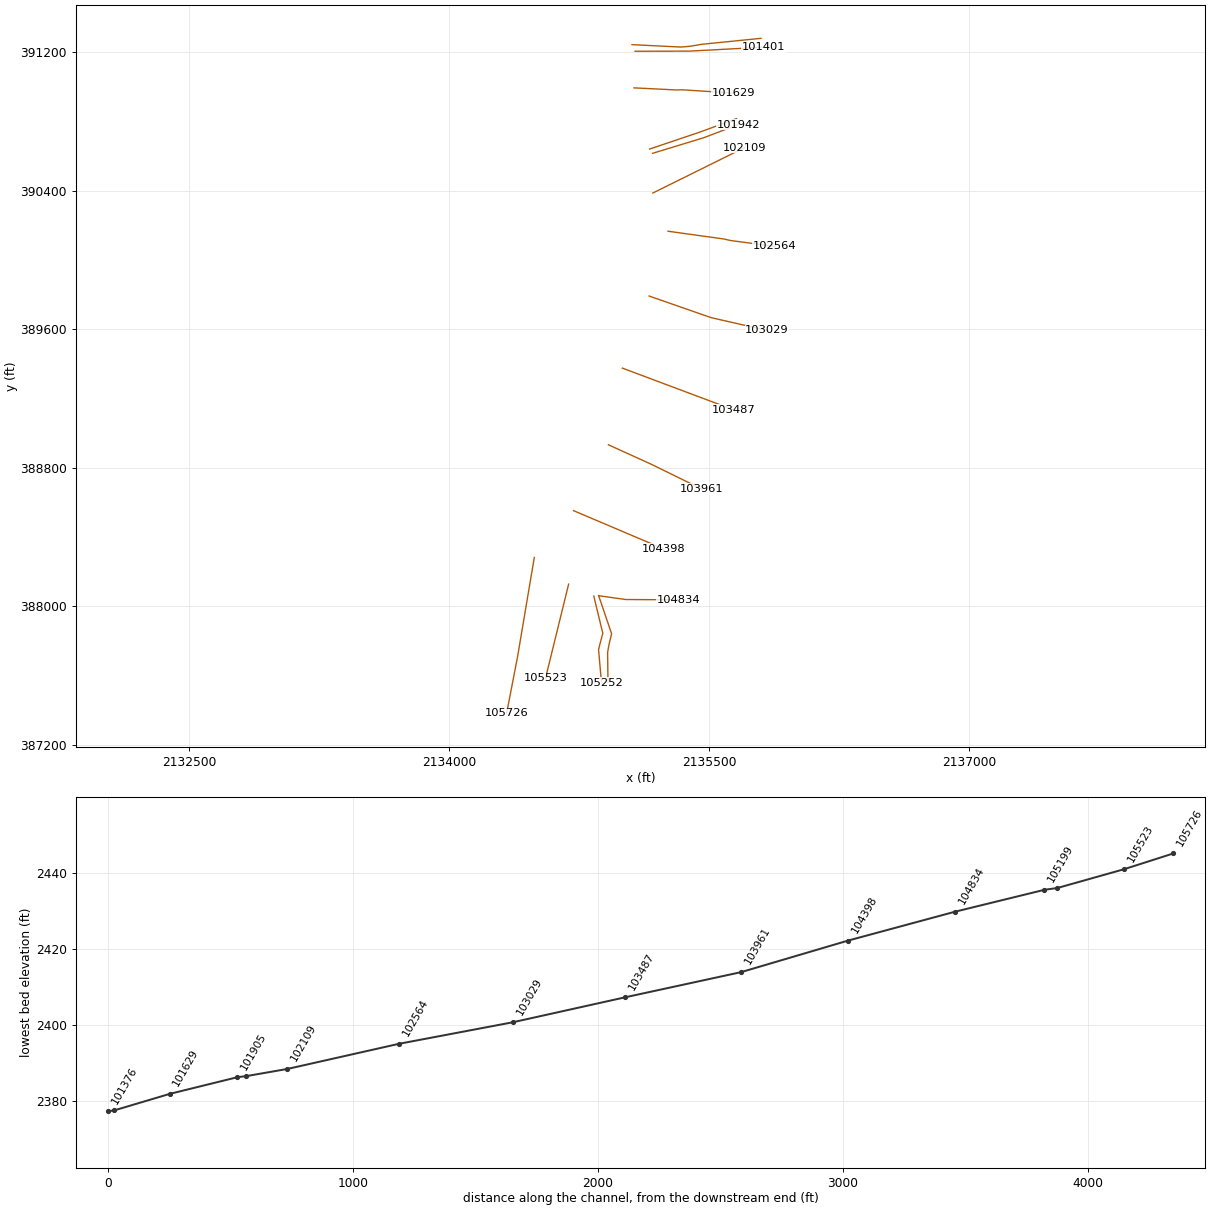
HEC-RAS study SPRINGCK.prj: SPRINGCK

--- SPRINGCK.g01 (geometry) --- (continued)

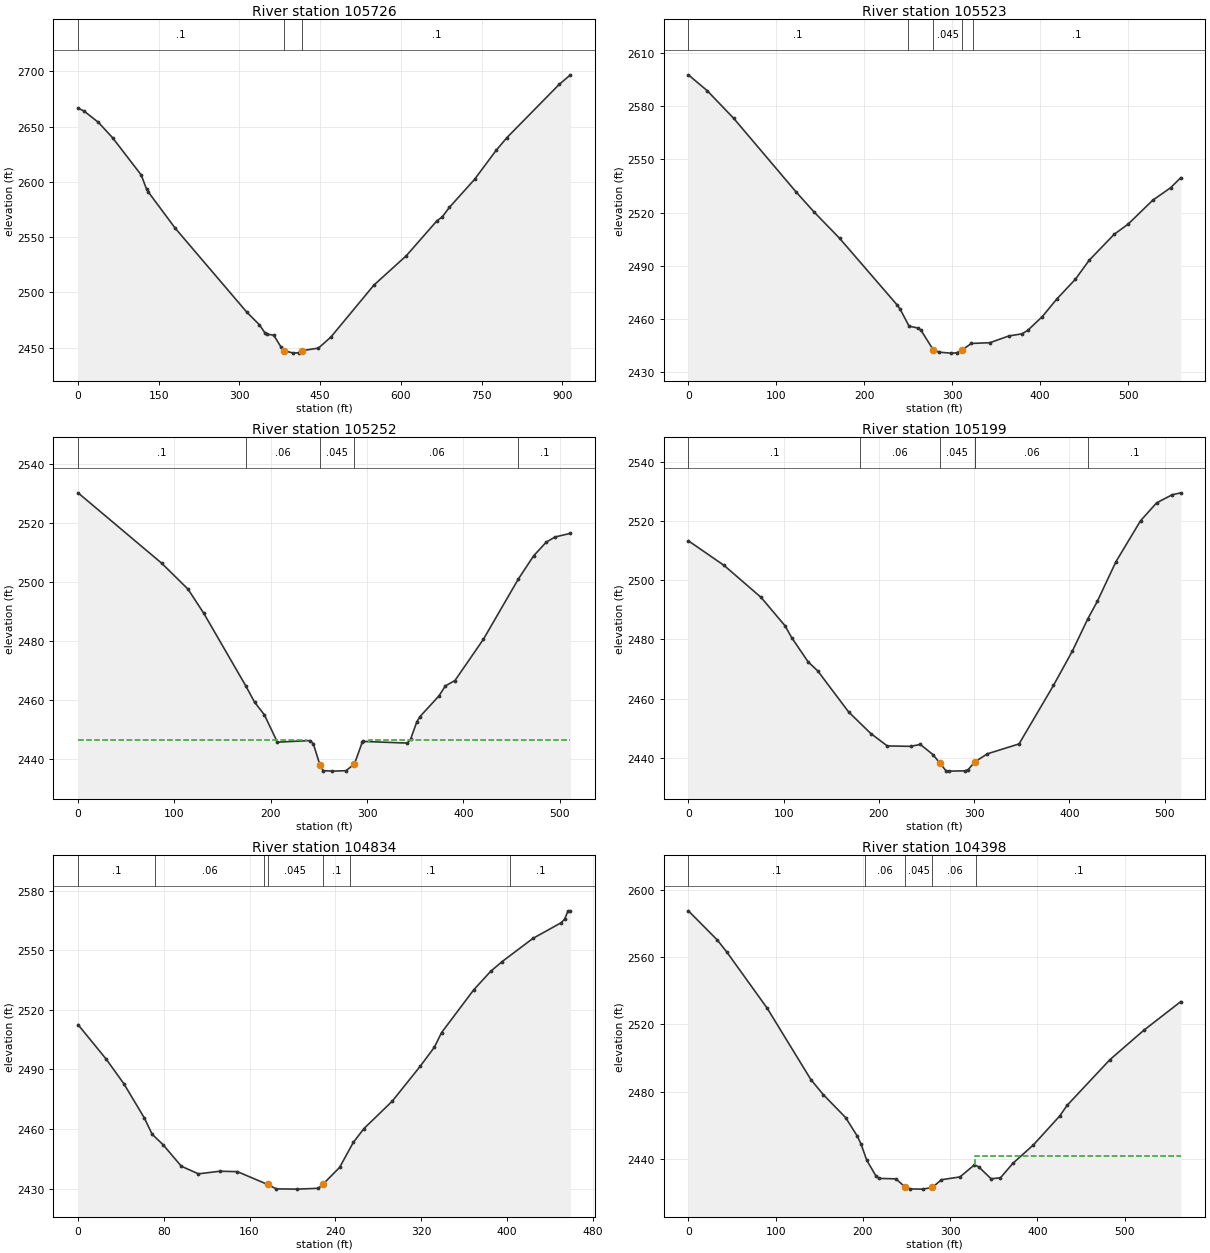
Type RM Length L Ch R = 1 ,105726  ,202.9,202.5,201
XS GIS Cut Line= 3
2134492.43007314 388281.088985892134396.24949121387709.561257556
2134332.70762356387380.047480896
#Sta/Elev= 30
       0  2666.8      11 2664.14    37.6 2653.99    64.2 2639.96   117.4 2606.27
   127.4 2593.37   130.7 2590.78   180.6  2558.1   313.7 2482.09     337 2470.78
     347 2463.67   350.3 2462.16   363.6  2461.4   376.9  2450.8   383.6 2447.27
   400.2 2445.06   410.2 2445.48   416.9 2447.38   446.8  2449.6   470.1 2459.72
   549.9 2506.65     610 2533.17   666.8 2564.71   676.8 2568.32   690.1 2576.93
   736.9 2602.29     777 2628.54   797.1  2640.1     894 2688.14   915.1 2696.89
#Mann= 3 , 0 , 0
       0      .1       0   383.6    .045       0   416.9      .1       0
Bank Sta=383.6,416.9
XS Rating Curve= 0 ,0
Exp/Cntr=0.3,0.1

Type RM Length L Ch R = 1 ,105523  ,265.4,271,264.8
XS GIS Cut Line= 2
2134690.47987388388126.8163285552134557.14680722387583.066431805
#Sta/Elev= 30
       0 2597.65    21.2 2588.81    51.6  2573.1   122.5 2531.66   142.8 2520.44
   171.9 2505.58   237.4    2468   240.8 2465.65   250.9 2456.11     261 2455.02
   264.4 2453.84  278.292442.863   284.7 2441.43   298.2 2440.88     305 2441.01
  311.032442.613   321.8 2446.34   342.8 2446.76   364.5 2450.57   379.3 2451.75
   385.8 2453.67   402.5  2461.5   418.7 2471.25   440.1 2482.54   455.7 2493.19
   484.2 2507.83   500.1 2513.59   527.9 2526.98   548.2 2534.01   559.9 2539.71
#Mann= 5 ,-1 , 0
       0      .1       0  249.51     .06       0  278.29    .045       0
  311.03     .06       0  323.62      .1       0
Bank Sta=278.29,311.03
XS Rating Curve= 0 ,0
Exp/Cntr=0.5,0.3

Type RM Length L Ch R = 1 ,105252  ,51.5,53.1,52.3
XS GIS Cut Line= 5
2134835.58424248388058.0454687332134887.66747163387842.420571893
2134869.95917372387776.3997065572134863.29252039387748.066429898
2134880.06348422387557.024489149
#Sta/Elev= 30
       0 2530.23      87 2506.34   114.2 2497.58   130.5 2489.43     174 2464.91
   183.3 2459.29   193.4 2455.05   206.9 2445.77   240.8 2446.31   244.2 2445.26
  251.122437.998   254.4 2436.13   264.1 2435.96   278.2 2436.11  286.932438.426
   295.1 2445.84   296.3 2446.02   341.8 2445.46   345.1 2446.71   351.7  2452.7
     355 2454.46   374.7 2461.47   381.3 2464.84   391.2 2466.64   420.8 2480.65
   457.1 2501.08     473 2508.94     486 2513.53   495.1 2515.27   511.1 2516.51
#Mann= 5 ,-1 , 0
       0      .1       0     174     .06       0  251.12    .045       0
  286.93     .06       0   457.1      .1       0
#XS Ineff= 2 , 0
           236.1  2446.6   301.9          2446.6
Permanent Ineff=
       F       F
Bank Sta=251.12,286.93
XS Rating Curve= 0 ,0
Exp/Cntr=0.5,0.3

Type RM Length L Ch R = 1 ,105199  ,336.3,365.2,405.5
XS GIS Cut Line= 5
2134863.39685088388061.1914598052134938.39670089387840.357911974
2134922.77173214387774.7330432242134915.48008005387732.024795309
2134917.56340922387559.107818305
#Sta/Elev= 30
       0 2513.27    37.5 2504.95    76.3 2494.16   101.4 2484.59   108.4  2480.6
   125.7 2472.38   135.8 2469.33   168.2 2455.47   191.5 2448.18   208.8 2443.99
   233.2 2443.85   243.5 2444.49   256.7 2441.08  263.752438.303   270.2 2435.69
   273.6 2435.48   290.4 2435.58   293.8 2436.02   300.5 2438.57   313.9 2441.33
   347.1 2444.67   383.2 2464.41   402.9 2475.91   419.3 2486.93   429.2 2492.78
   448.8  2506.2   474.6 2520.02   491.5 2526.09   507.9 2528.82   516.9 2529.47
#Mann= 6 ,-1 , 0
       0      .1       0  180.46     .06       0  263.75    .045       0
   300.5    .045       0  300.68     .06       0  419.98      .1       0
Bank Sta=263.75,300.5
XS Rating Curve= 0 ,0
Exp/Cntr=0.5,0.3

Type RM Length L Ch R = 1 ,104834  ,439.5,435.4,434
XS GIS Cut Line= 3
2134864.43851547388059.8023549772135020.20756088388038.033697724
2135322.29094622388036.297480732
#Sta/Elev= 30
       0 2512.53    26.2 2495.22    42.7 2482.83    61.8 2465.61    69.2 2457.29
    79.2 2452.16    96.4 2441.23   112.3 2437.41   132.2 2438.72   148.7 2438.51
  176.772432.085   184.9 2429.84   204.6 2429.71   224.3 2430.13  228.742432.297
     244 2440.63   256.9  2453.3   266.8 2460.23   293.1 2473.97   319.2 2491.55
   332.5  2501.2   339.1 2508.48   369.1 2530.02     385 2539.39   395.5 2544.21
   424.4 2555.96   450.6 2563.81   453.9  2565.6   457.2 2569.84   459.4 2569.82
#Mann= 7 ,-1 , 0
       0      .1       0   71.76     .06       0  173.32      .1       0
  176.77    .045       0  228.74      .1       0  254.02      .1       0
  403.32      .1       0
Bank Sta=176.77,228.74
XS Rating Curve= 0 ,0
Exp/Cntr=0.3,0.1

Type RM Length L Ch R = 1 ,104398  ,435.4,437.5,436.2
XS GIS Cut Line= 2
2134718.64517188388551.6330642252135238.08967106388330.799844474
#Sta/Elev= 30
       0 2587.34    33.3 2569.93      44 2562.91    90.3 2529.55   140.5 2487.09
   154.5  2478.3   180.3 2464.57   193.7 2453.51   197.9 2448.85   204.4 2439.33
   215.1 2429.82   218.7 2428.49   237.9 2428.24  247.962423.569   254.3 2422.24
   268.6 2422.13   279.72423.134     290 2427.71   311.3 2429.37   327.9 2436.57
   332.7 2435.36     347 2428.28   357.7 2428.84   371.9 2437.44   395.5 2448.41
   425.7 2465.61     434 2471.82     483 2498.91   521.7 2516.31   564.4 2533.46
#Mann= 5 ,-1 , 0
       0      .1       0   202.4     .06       0  247.96    .045       0
   279.7     .06       0  330.15      .1       0
#XS Ineff= 2 , 0
                          329.03         2441.71
Permanent Ineff=
       F       F
Bank Sta=247.96,279.7
XS Rating Curve= 0 ,0
Exp/Cntr=0.3,0.1

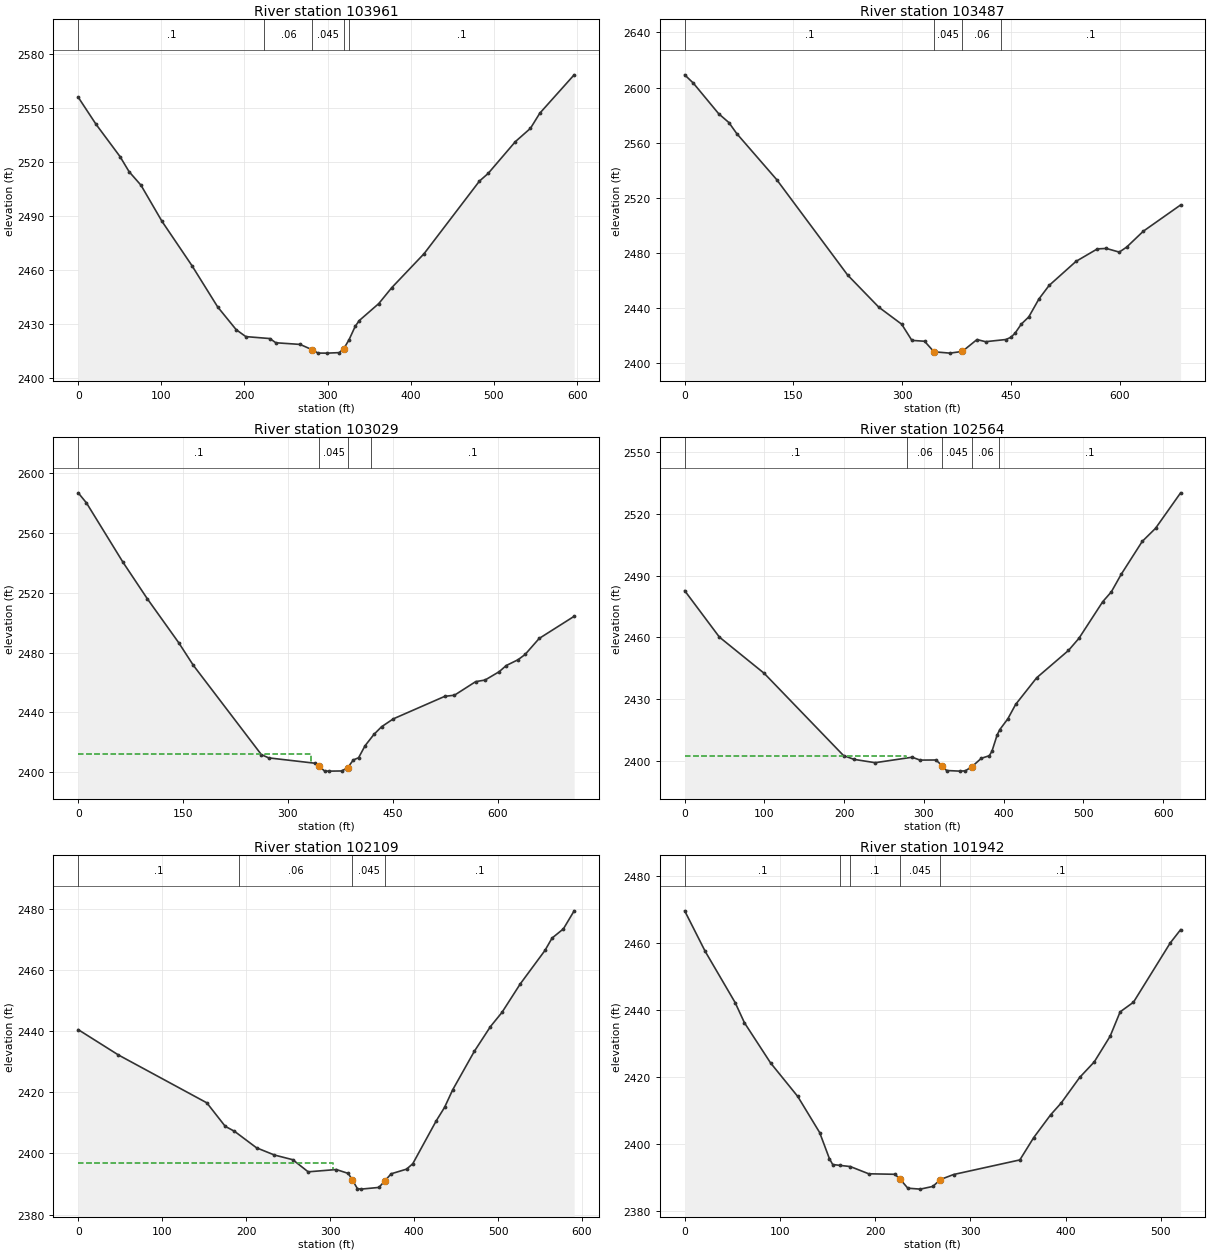
Type RM Length L Ch R = 1 ,103961  ,468.8,474.2,473
XS GIS Cut Line= 3
2134920.03420481388932.188733563 2135164.4785978388821.077407226
 2135458.9228908388676.633142307
#Sta/Elev= 30
       0 2556.02    21.4    2541    50.3 2523.03    61.2 2514.64    75.5 2507.12
   100.7  2487.1   136.8 2462.43   167.7 2439.51     190 2426.84   201.6 2422.99
   230.5 2421.91   237.7 2419.57   266.9 2418.65  281.632415.638   288.4 2413.84
   299.4 2413.81     314 2414.09  319.522416.374   325.7  2421.2   333.1 2428.63
     338  2431.9   361.5 2441.34   377.2 2450.23     416 2469.07   482.6 2509.42
     493 2513.63   525.9 2531.38   543.9 2538.71   555.2 2547.14   596.5 2568.46
#Mann= 5 ,-1 , 0
       0      .1       0  224.04     .06       0  281.63    .045       0
  319.52     .06       0  325.78      .1       0
Bank Sta=281.63,319.52
XS Rating Curve= 0 ,0
Exp/Cntr=0.3,0.1

Type RM Length L Ch R = 1 ,103487  ,454.9,457.7,456.5
XS GIS Cut Line= 2
2135000.58981797389375.244277895 2135640.8674088389134.966543227
#Sta/Elev= 30
       0 2609.23    11.9 2603.23    46.9 2580.98      61 2574.56    71.8 2566.57
   126.8  2533.2   224.7 2463.87   267.7 2440.53   299.2 2428.19   313.3 2416.43
   330.8 2415.79  343.762408.142   365.8 2407.17  382.842408.398   403.1 2417.03
   414.9 2415.47   442.9 2417.05   449.9 2418.67   455.7 2421.72   464.2 2428.25
   474.5 2433.45   488.5 2446.49   502.5 2456.28   539.7 2473.81   569.1 2482.85
   581.4 2483.18   599.3 2480.52   609.5 2484.15   632.4 2495.66   683.9 2514.75
#Mann= 4 ,-1 , 0
       0      .1       0  343.76    .045       0  382.84     .06       0
  435.91      .1       0
Bank Sta=343.76,382.84
XS Rating Curve= 0 ,0
Exp/Cntr=0.3,0.1

Type RM Length L Ch R = 1 ,103029  ,461.5,464.8,465.7
XS GIS Cut Line= 5
2135154.75617631389791.9107673912135477.71451989389679.115389317
 2135496.5901383389672.5041820562135515.59961472389666.275191888
2135834.75645672389593.403946564
#Sta/Elev= 30
       0 2586.98    11.8 2580.23      64 2540.53    98.7 2516.15   143.9 2486.52
   164.7 2471.47     262 2411.68   272.5 2409.48   338.5 2405.91  344.952403.799
   352.4  2400.7   359.4 2400.61   376.7 2400.72  385.372402.842   393.6  2408.1
   401.1 2409.57   410.4 2417.63     423 2425.17   433.9  2430.3   450.8 2435.62
   524.4 2450.69   538.3 2451.46   568.6 2460.54   582.1 2461.62   602.3 2467.21
   612.3 2471.31   629.2  2475.2   639.3 2478.72   659.5 2489.47   709.5 2504.29
#Mann= 4 ,-1 , 0
       0      .1       0  344.95    .045       0  385.37    .055       0
  418.32      .1       0
#XS Ineff= 2 , 0
          333.22 2411.81
Permanent Ineff=
       F       F
Bank Sta=344.95,385.37
XS Rating Curve= 0 ,0
Exp/Cntr=0.3,0.1

Type RM Length L Ch R = 1 ,102564  ,439.8,455.6,465.5
XS GIS Cut Line= 5
2135263.92295273390166.3204516472135586.96102056390121.376971975
 2135606.4442493390116.8533589842135625.98029947390112.569574893
 2135879.5480338390078.820626646
#Sta/Elev= 30
       0 2482.76    43.5 2460.18    99.8 2442.51   199.2 2402.52   212.4 2400.66
   238.9 2399.04   285.3 2401.71   295.2 2400.31   315.1 2400.36  322.892397.595
   328.4 2395.24     345 2394.94     352 2395.08  360.442397.167     372 2401.18
     382 2402.43   385.3 2404.53   391.9 2412.55   395.2 2415.14   405.3  2420.4
   415.1 2427.41   441.5 2440.39   481.3 2453.65   494.5 2459.58   524.3 2477.38
   535.1 2482.17   547.4 2490.67   573.9 2506.75   590.5 2513.08     622 2530.37
#Mann= 5 ,-1 , 0
       0      .1       0   278.5     .06       0  322.89    .045       0
  360.44     .06       0  394.69      .1       0
#XS Ineff= 2 , 0
           277.7 2402.31
Permanent Ineff=
       F       F
Bank Sta=322.89,360.44
XS Rating Curve= 0 ,0
Exp/Cntr=0.3,0.1

Type RM Length L Ch R = 1 ,102109  ,170.1,167,162.9
XS GIS Cut Line= 2
2135176.42312773390387.1539994782135705.58972031390649.653802559
#Sta/Elev= 30
       0  2440.5    47.9 2432.21   153.2 2416.55   175.1 2408.87   186.1 2407.25
   212.4 2401.84   233.7 2399.48   255.6 2397.94   273.9 2393.98   307.4 2394.73
   321.6 2393.46  326.352391.399   332.5 2388.51   336.8 2388.32   358.2 2388.88
  365.512391.124   372.8 2393.34   391.1 2394.86   398.5 2396.64   426.5  2410.7
   436.3 2415.05   446.1 2420.85   471.7 2433.36     491  2441.5   504.7 2446.13
   526.6  2455.5   555.9  2466.4   564.4 2470.46   577.9 2473.47   590.7 2479.37
#Mann= 4 ,-1 , 0
       0      .1       0  191.68     .06       0  326.35    .045       0
  365.51      .1       0
#XS Ineff= 2 , 0
          303.57 2396.71
Permanent Ineff=
       F       F
Bank Sta=326.35,365.51
XS Rating Curve= 0 ,0
Exp/Cntr=0.5,0.3

Type RM Length L Ch R = 1 ,101942  ,35.6,36.9,37.3
XS GIS Cut Line= 3
 2135174.7679473390616.552490816 2135469.0390123390706.396143138
2135668.25777397390781.916989475
#Sta/Elev= 30
       0 2469.52    21.6 2457.39      53 2442.12    62.8 2436.08    90.2 2424.11
   118.7 2414.11   141.7 2403.34     152 2395.51   155.4 2393.79   163.3 2393.52
   173.9 2393.18   193.2 2391.02   220.6 2390.87  225.852389.519   234.3 2386.72
   247.4 2386.44   260.6 2387.25   268.42389.292   282.3  2390.8   351.9 2395.16
   366.4  2401.8   384.2 2408.62   395.3 2412.15   414.7 2419.78     430 2424.41
   446.7 2432.09   457.2 2439.36   471.2 2442.24   509.8 2459.93   520.7  2463.9
#Mann= 5 ,-1 , 0
       0      .1       0   163.3     .06       0   173.9      .1       0
  225.85    .045       0   268.4      .1       0
#XS Ineff= 2 , 0
           210.5  2390.7   283.4          2390.7
Permanent Ineff=
       F       F
Bank Sta=225.85,268.4
XS Rating Curve= 0 ,0
Exp/Cntr=0.5,0.3

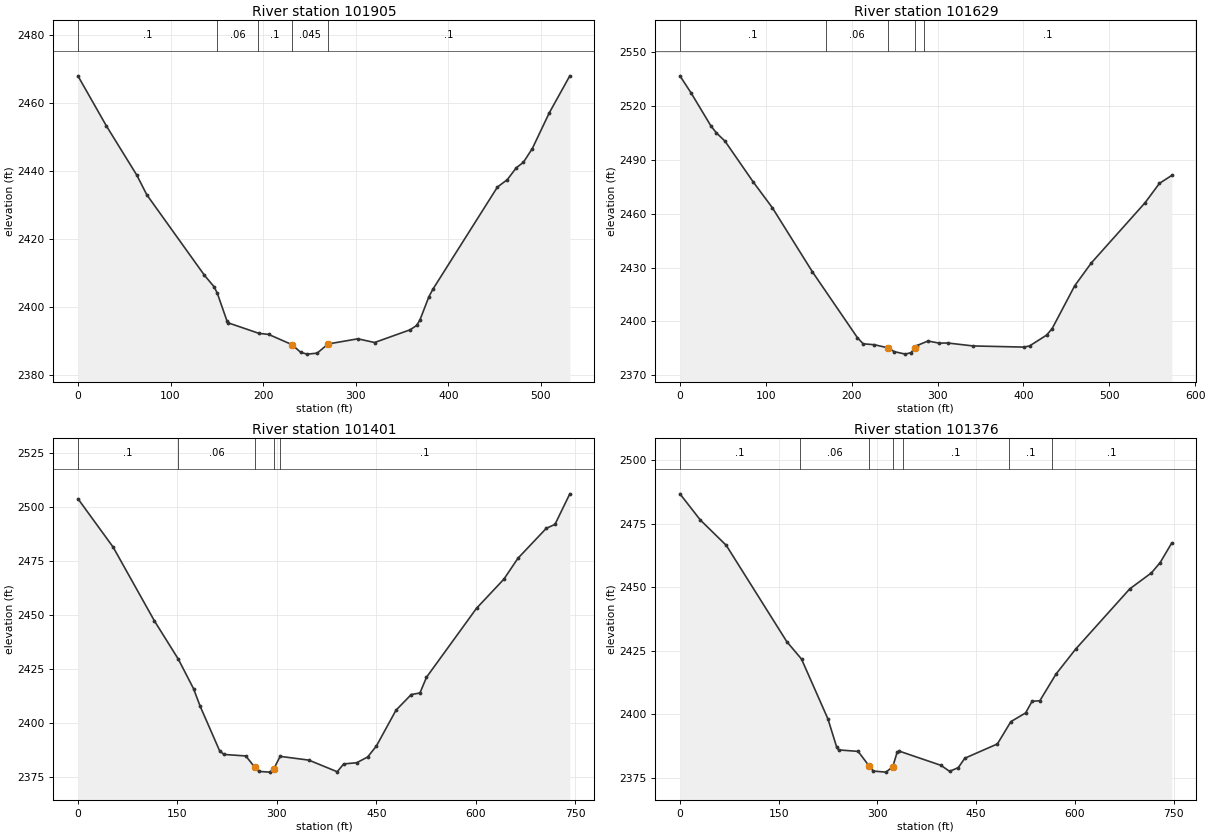
Type RM Length L Ch R = 1 ,101905  ,281.2,276.2,271.1
XS GIS Cut Line= 3
2135157.84114389390641.2919426412135450.80971806390740.250406146
 2135659.1429628390817.073087141
#Sta/Elev= 30
       0 2468.02    30.5 2453.41    63.6  2438.8    74.3 2433.07   136.6 2409.36
   147.1 2405.95   150.5 2404.06   160.9 2395.94   162.5 2395.34   195.5 2392.26
   205.9 2391.96  231.112388.949   240.6 2386.67   247.5 2386.15   258.3 2386.43
  270.172389.142   302.3 2390.66   320.4 2389.57   358.8 2393.32   365.8 2394.59
   369.3 2396.15     379    2403   383.3 2405.23   453.1 2435.34   463.7  2437.5
   473.5 2441.01   481.2 2442.64   490.8 2446.68   509.1 2457.18   531.3 2468.08
#Mann= 5 ,-1 , 0
       0      .1       0     150     .06       0  194.45      .1       0
  231.11    .045       0  270.17      .1       0
Bank Sta=231.11,270.17
XS Rating Curve= 0 ,0
Exp/Cntr=0.5,0.3

Type RM Length L Ch R = 1 ,101629  ,227.6,227.3,227
XS GIS Cut Line= 5
2135067.67301714390994.8624297232135309.59248081390982.806679562
2135329.58948806390983.1531355532135349.58485489390983.500575811
2135639.54785764390964.653828725
#Sta/Elev= 30
       0 2536.92      13 2527.38      36 2509.06    42.5 2505.09    52.4 2500.55
    85.2 2477.86   107.7 2463.34   154.2 2427.72   206.8 2390.87   213.4 2387.52
   226.6 2386.99  242.222385.271   249.5 2383.16   262.6 2381.76   269.2 2382.61
  273.652385.389   275.7 2386.47   288.9 2389.07     302 2387.89   311.9 2387.97
   341.5 2386.32   400.7 2385.68   407.2 2386.33     427 2392.35   433.5 2395.99
   459.8 2419.89   479.2 2432.64   541.6  2466.1   558.5 2476.99   572.8 2481.38
#Mann= 5 ,-1 , 0
       0      .1       0   169.7     .06       0  242.22    .045       0
  273.65     .06       0  284.27      .1       0
Bank Sta=242.22,273.65
XS Rating Curve= 0 ,0
Exp/Cntr=0.3,0.1

Type RM Length L Ch R = 1 ,101401  ,24.3,25.2,28.7
XS GIS Cut Line= 3
2135073.63986872391206.417124733 2135388.7438973391207.284905151
2135814.95925222391229.854413807
#Sta/Elev= 30
       0 2503.96      53 2481.59   115.3 2447.42   151.3 2429.73   174.3 2416.03
   184.2 2407.96   213.7 2387.23   220.2 2385.59   253.1 2384.89  266.382379.768
   272.7 2377.74   289.1  2377.4  295.612379.066   304.9  2384.7   348.2 2382.96
     391 2377.58   400.8 2381.19   420.5 2381.76     437 2384.43   450.1 2389.48
   479.7 2406.08   502.7 2413.33   515.8 2414.05   525.7 2421.33   601.2 2453.28
   642.4 2466.75   663.6 2476.41   706.4  2490.3   719.5 2492.11   741.9 2506.27
#Mann= 5 ,-1 , 0
       0      .1       0   151.3     .06       0  266.38    .045       0
  295.61     .06       0   304.9      .1       0
Bank Sta=266.38,295.61
XS Rating Curve= 0 ,0
Exp/Cntr=0.3,0.1

Type RM Length L Ch R = 1 ,101376  ,402.8,391.2,368.7
XS GIS Cut Line= 6
2135056.27868298391244.6116021422135336.66066813391230.722522303
2135391.34822281 391235.062736722135456.45209523391246.347491056
2135507.66754398391251.5558139832135800.20239197391281.069862559
#Sta/Elev= 30
       0  2486.8      31 2476.49    70.4 2466.51   162.3  2428.6   184.7 2421.73
   224.8 2398.18   237.9 2387.25     241 2385.94   270.7 2385.36  287.182379.692
   293.8  2377.6   313.1 2377.19   323.4 2379.34     330 2385.04   333.3 2385.45
   396.5 2379.87   409.7 2377.51   422.9 2378.96   432.8 2382.67   482.3 2388.29
   502.8 2397.08   525.2 2400.51     535 2405.09   546.8 2405.31   571.3 2415.79
     601 2425.58   683.4 2449.37   716.4 2455.68   729.6 2459.72   747.2 2467.44
#Mann= 7 ,-1 , 0
       0      .1       0  182.58     .06       0  287.18    .045       0
   323.4     .06       0  338.92      .1       0  499.61      .1       0
  565.87      .1       0
Bank Sta=287.18,323.4
XS Rating Curve= 0 ,0
Exp/Cntr=0.3,0.1