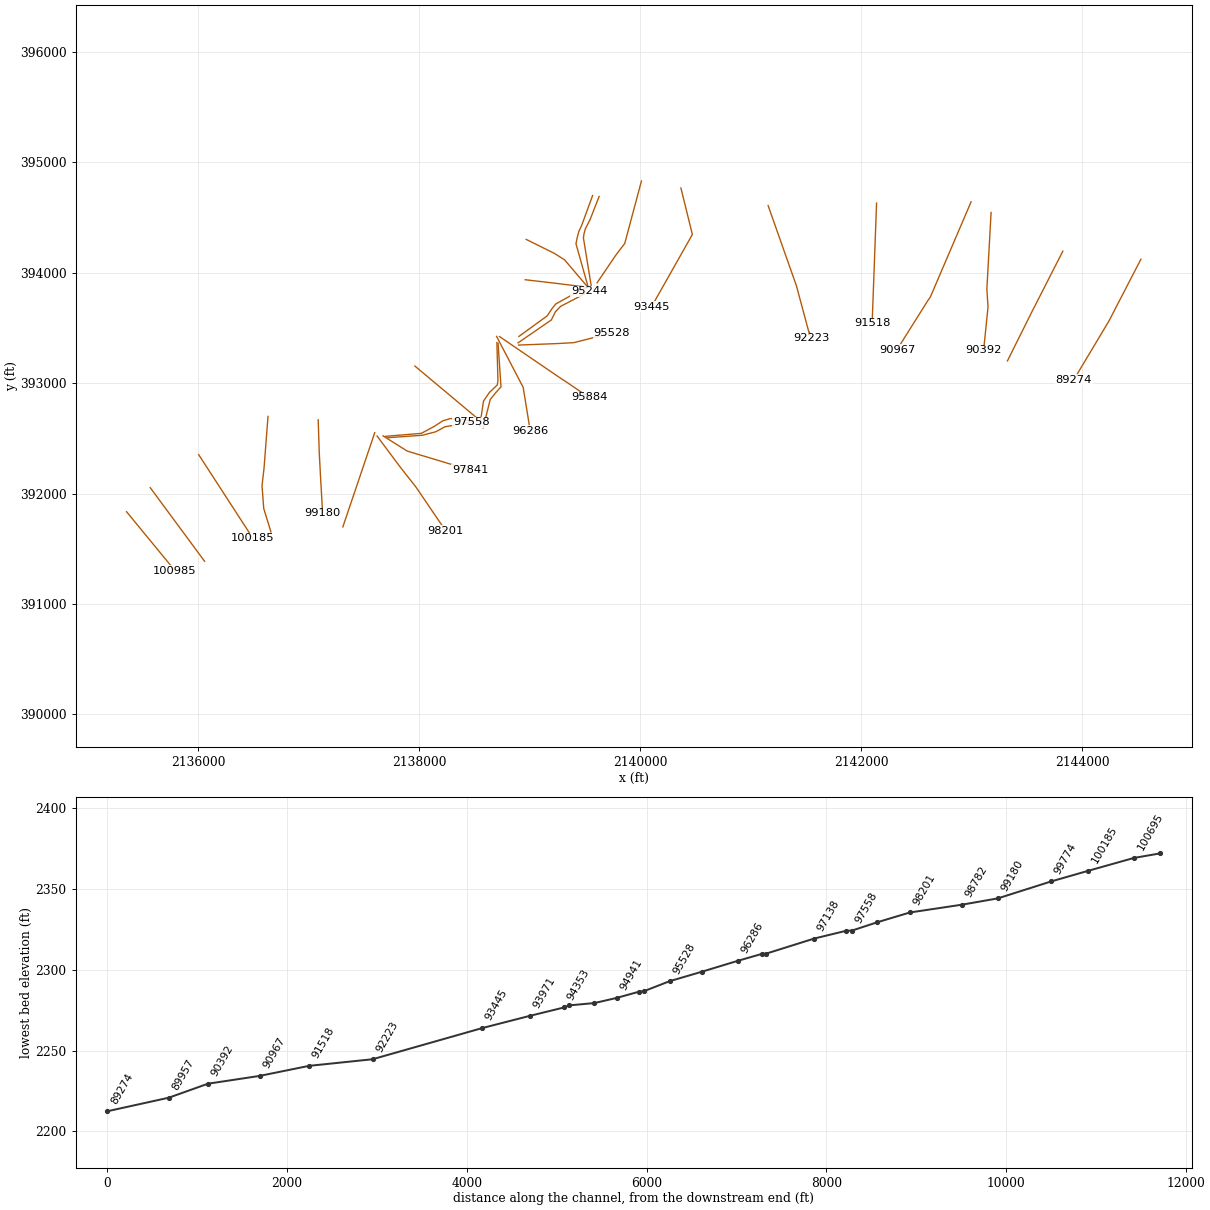
HEC-RAS study SPRINGCK.prj: SPRINGCK

--- SPRINGCK.g01 (geometry) --- (continued)

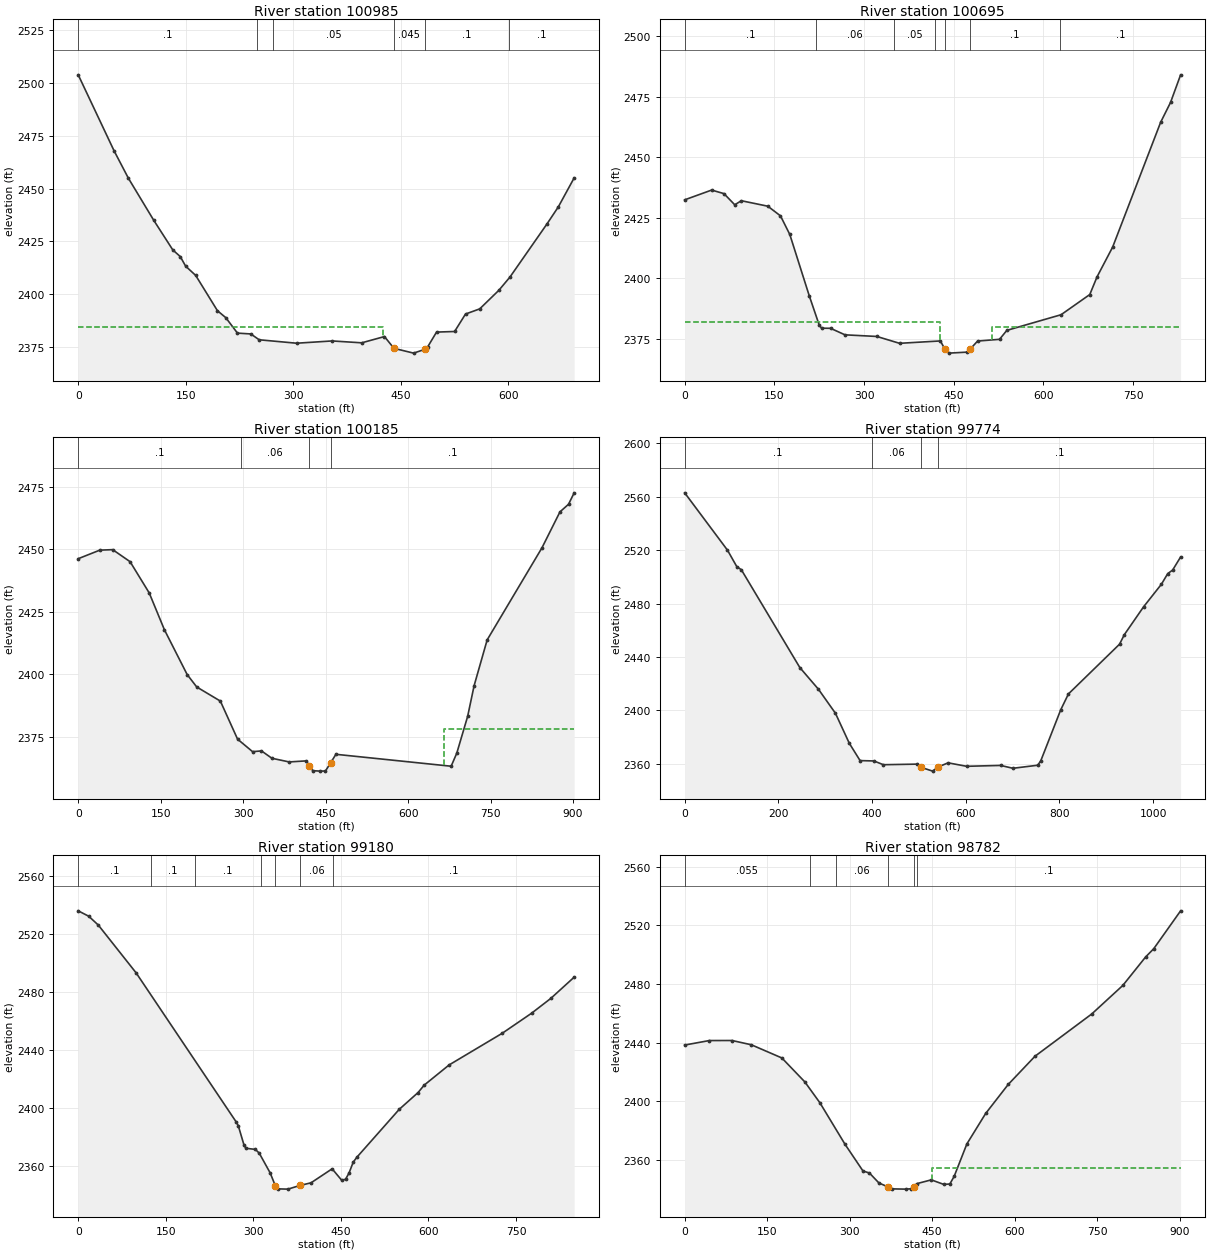
Type RM Length L Ch R = 1 ,100985  ,287.2,290.3,284.1
XS GIS Cut Line= 2
2135351.15703022391835.7862728092135790.39335647391301.063917056
#Sta/Elev= 30
       0 2503.95      50 2467.94      70 2454.91   105.2 2435.06     132 2420.89
   142.4 2417.74   149.9 2413.19   163.9 2408.81   194.3 2392.05   205.9 2388.77
   222.2 2381.43   240.8 2381.04   252.5 2378.27   304.7 2376.64   354.3 2377.72
   395.6 2376.83   427.3  2379.8   440.6 2374.21     468 2371.94   483.3  2373.7
   487.9 2375.07     500 2381.92   525.2  2382.2   540.4 2390.48   560.2 2392.92
   586.9 2401.73   602.4 2408.01   654.1 2433.23   669.9  2441.3     692 2455.06
#Mann= 6 ,-1 , 0
       0      .1       0     249     .06       0  271.39     .05       0
   440.6    .045       0   483.3      .1       0  601.57      .1       0
#XS Ineff= 2 , 0
          425.47 2384.12
Permanent Ineff=
       F       F
Bank Sta=440.6,483.3
XS Rating Curve= 0 ,0
Exp/Cntr=0.3,0.1

Type RM Length L Ch R = 1 ,100695  ,508.9,509.7,504.9
XS GIS Cut Line= 2
 2135565.6766143392053.427241728 2136058.2110623391386.181857064
#Sta/Elev= 30
       0 2432.41    45.1 2436.44    65.7 2434.97    83.7 2430.37    94.8 2432.04
     139 2429.78   160.2 2425.79   175.8  2418.1   208.4 2392.74   224.7 2380.92
   228.8 2379.43   243.9 2379.39   268.1 2376.69   321.3 2376.02   359.3 2373.19
   427.6 2374.17   434.6 2371.01   441.7 2369.14   472.2 2369.55   477.6 2370.85
   489.8 2374.12   526.5 2374.84   538.7 2378.53   629.4 2384.99   677.4 2393.32
   689.6 2400.65   715.7 2412.94   795.9 2464.42   812.4 2472.58   829.3    2484
#Mann= 7 ,-1 , 0
       0      .1       0  219.75     .06       0  349.78     .05       0
  418.93      .1       0   434.6    .045       0   477.6      .1       0
  627.73      .1       0
#XS Ineff= 2 , 0
          427.28 2381.98   513.3         2379.87
Permanent Ineff=
       F       F
Bank Sta=434.6,477.6
XS Rating Curve= 0 ,0
Exp/Cntr=0.3,0.1

Type RM Length L Ch R = 1 ,100185  ,425.7,411.3,401.3
XS GIS Cut Line= 2
 2136004.5655003392352.0381930622136494.84306306391595.093840808
#Sta/Elev= 30
       0 2446.18    39.2  2449.6    62.7  2449.8    94.3 2444.99   129.1 2432.49
   156.8 2417.72   198.1 2399.83   215.5 2394.85   258.5  2389.2   289.8 2373.97
   317.1 2368.96   333.3 2369.26   352.3 2366.31   383.6 2364.85   414.8 2365.27
  419.772363.381   426.6 2361.35   440.1 2361.17   449.6 2361.22  459.132364.504
   468.6  2367.9   678.2 2363.13   688.5 2368.39   708.2 2383.08     720 2395.39
   743.7 2413.69   843.4 2450.55   876.1 2464.92   891.7 2467.97   901.9 2472.54
#Mann= 4 ,-1 , 0
       0      .1       0  295.47     .06       0  419.77    .045       0
  459.13      .1       0
#XS Ineff= 2 , 0
                           664.4         2378.09
Permanent Ineff=
       F       F
Bank Sta=419.77,459.13
XS Rating Curve= 0 ,0
Exp/Cntr=0.3,0.1

Type RM Length L Ch R = 1 ,99774   ,585.4,593.8,591.6
XS GIS Cut Line= 5
2136631.81063689392698.6818567222136595.69948864392227.848480806
2136577.64407855392072.2926895622136592.92193514391865.348549649
2136658.19969173391652.848318473
#Sta/Elev= 30
       0 2562.87    91.4 2519.94   111.2 2507.66     121 2505.29   245.8 2432.11
   285.6 2415.85   321.8 2397.91   351.4 2375.44   374.4 2362.48     404 2362.21
     424  2359.4   496.2 2359.84  504.842357.418   529.3  2354.6  540.73 2357.68
   562.3  2360.8   601.9 2358.21   674.4 2358.87   700.7 2356.73   753.4    2359
   759.9 2362.14   802.7  2400.5   819.2  2412.4   928.2 2449.58   938.5 2456.74
   979.7 2477.64  1017.5 2494.41  1031.2 2502.46  1041.5 2505.04  1058.6 2514.86
#Mann= 4 ,-1 , 0
       0      .1       0  399.36     .06       0  504.84    .045       0
  540.73      .1       0
Bank Sta=504.84,540.73
XS Rating Curve= 0 ,0
Exp/Cntr=0.3,0.1

Type RM Length L Ch R = 1 ,99180   ,406.3,398.3,390.5
XS GIS Cut Line= 4
2137085.97737947 392668.126143562137095.69947289392369.515192226
2137108.19944789392133.4037878072137126.25518605391819.514979899
#Sta/Elev= 30
       0 2536.29      18 2532.56    34.4 2526.46    99.3  2493.4   270.7 2390.46
   274.2 2387.91   283.8 2374.86   287.1 2372.35   303.5 2371.53   310.1 2368.97
   328.8 2355.34  337.642346.478     343 2344.27   359.4 2344.11  379.742346.638
   398.8 2348.46     435 2358.14   451.4 2350.23     458 2350.93   464.1 2355.36
   471.1 2362.73   477.4 2366.15     550 2399.23   582.3 2410.83   592.6 2415.89
   635.4 2429.87   726.3 2451.71   776.7 2465.59   809.6 2475.81   849.6 2490.47
#Mann= 7 ,-1 , 0
       0      .1       0  124.02      .1       0  199.32      .1       0
  312.92     .06       0  337.64    .045       0  379.74     .06       0
  437.27      .1       0
Bank Sta=337.64,379.74
XS Rating Curve= 0 ,0
Exp/Cntr=0.3,0.1

Type RM Length L Ch R = 1 ,98782   ,570.4,580.2,603.7
XS GIS Cut Line= 2
2137597.92747106 392551.748751642137309.03861314391697.582152888
#Sta/Elev= 30
       0 2438.41      45 2441.48    86.1  2441.5   121.2  2438.6   176.7 2429.61
   218.4 2413.32   245.9 2399.04   291.6 2370.74   324.2 2352.58   335.9 2351.21
   353.3 2344.37  370.522341.618   377.5 2340.39   401.5 2340.22   412.2 2340.47
  416.422341.952   422.5 2343.99   448.4 2346.54     471 2343.45   482.1 2343.72
   489.9 2348.86   513.1 2371.04   547.2 2391.76   588.2 2411.54     637  2430.8
   740.1 2459.58   796.6 2479.03   838.1 2498.45   852.8 2504.05   901.7 2529.88
#Mann= 6 ,-1 , 0
       0    .055       0  227.27      .1       0  275.27     .06       0
  370.52    .045       0  416.42     .06       0  421.61      .1       0
#XS Ineff= 2 , 0
                          449.35         2354.65
Permanent Ineff=
       F       F
Bank Sta=370.52,416.42
XS Rating Curve= 0 ,0
Exp/Cntr=0.3,0.1

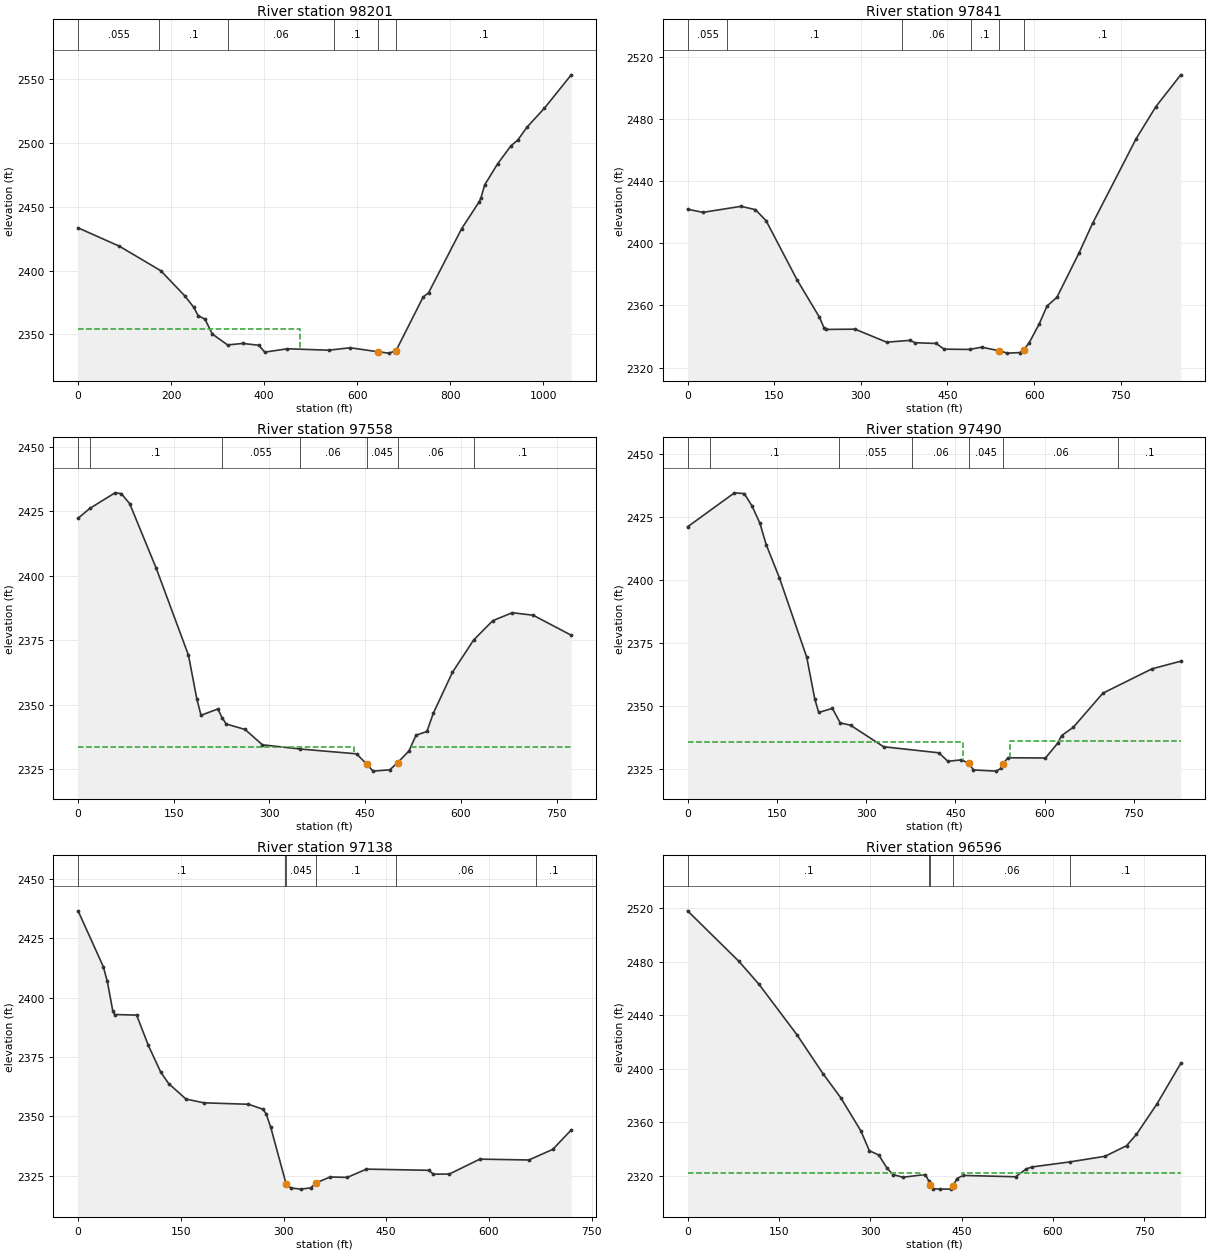
Type RM Length L Ch R = 1 ,98201   ,348.8,360.3,374.8
XS GIS Cut Line= 4
 2137618.7610908392521.1933665572137825.70555881392243.415378809
 2137972.9277053392055.9154257332138239.59416673391662.860109478
#Sta/Elev= 30
       0 2433.37    88.7 2419.02   177.8 2399.83   229.6 2380.05   248.3 2371.37
     258 2364.78   272.8 2361.88   288.5 2350.32   321.3  2341.8   354.1 2342.97
   388.2 2341.54   401.1 2336.17   449.9 2338.79   538.7 2337.69   584.8 2339.59
  645.082336.427   667.5 2335.39  683.052337.136   741.4 2379.21   753.2 2382.59
     824 2432.54   861.8 2453.69   865.7 2456.67   873.7 2466.94   901.4 2483.35
   930.3 2497.59   944.5 2501.85   964.9 2512.21  1002.2 2526.98  1059.8 2553.04
#Mann= 6 ,-1 , 0
       0    .055       0  174.74      .1       0  321.78     .06       0
  549.28      .1       0  645.08    .045       0  683.05      .1       0
#XS Ineff= 2 , 0
          476.74 2354.65
Permanent Ineff=
       F       F
Bank Sta=645.08,683.05
XS Rating Curve= 0 ,0
Exp/Cntr=0.3,0.1

Type RM Length L Ch R = 1 ,97841   ,264.7,282.9,301.4
XS GIS Cut Line= 3
2137672.92764914392522.5821433072137890.98331539392385.082090229
2138461.81649131392212.859993726
#Sta/Elev= 30
       0 2421.87    26.6 2419.85    92.6 2423.73   117.5 2421.58     136 2414.48
   189.5 2376.54   228.3 2352.48   236.1 2345.78     240 2344.62     290 2344.77
   344.8 2336.41   385.7 2337.61   393.6 2336.07   430.5 2335.59   444.2 2331.93
   488.4 2331.76   509.3 2333.21  539.532330.904   553.9 2329.38   575.3 2329.73
  582.12 2331.44   591.6 2336.09   608.7 2347.97   622.4 2359.64   639.6 2365.28
     678 2393.88   701.2  2412.7   776.6 2467.09   810.9  2487.8     854 2508.24
#Mann= 6 ,-1 , 0
       0    .055       0   68.85      .1       0  371.62     .06       0
  489.97      .1       0  539.53    .045       0  582.12      .1       0
Bank Sta=539.53,582.12
XS Rating Curve= 0 ,0
Exp/Cntr=0.5,0.3

Type RM Length L Ch R = 1 ,97558   ,52.4,68,60.1
XS GIS Cut Line= 5
2137716.46955681392505.9568484722138028.72647822392527.975833312
2138150.94867472392559.9203232232138233.58761705392605.059340566
2138469.59469096392645.540230721
#Sta/Elev= 30
       0 2422.24    18.4 2426.06    57.9  2432.1    67.7 2431.81    80.9  2427.9
   122.6 2402.79     173 2369.19   186.2 2352.11   192.7 2345.86     219 2348.31
   225.6 2344.99   232.2  2342.5   261.8 2340.36   288.9 2334.42   347.1 2332.82
   436.5 2330.93  452.352326.943   462.4 2324.22   488.6 2324.73  501.052327.547
   518.5    2332   529.7 2338.13   546.8 2339.61   556.7  2346.6   586.7  2362.5
     620 2375.05     650 2382.55   680.5 2385.62   713.2 2384.66     773  2376.9
#Mann= 7 ,-1 , 0
       0    .055       0    18.4      .1       0   225.6    .055       0
   347.1     .06       0  452.35    .045       0  501.05     .06       0
     620      .1       0
#XS Ineff= 2 , 0
           432.5  2333.7  521.05          2333.7
Permanent Ineff=
       F       F
Bank Sta=452.35,501.05
XS Rating Curve= 0 ,0
Exp/Cntr=0.5,0.3

Type RM Length L Ch R = 1 ,97490   ,383.9,352.2,324.8
XS GIS Cut Line= 6
2137695.63626514392518.4568234832138019.69860914392545.337019056
2138135.67081814392607.8372221442138214.38621189392659.081870317
2138285.21973164392679.9151619822138488.34465347392658.040205732
#Sta/Elev= 30
       0    2421    78.8 2434.49    95.3 2434.19   108.5 2429.21   121.6 2422.42
   132.1 2413.96   154.5 2400.67   200.3 2369.24   213.8 2352.69   220.4 2347.32
   243.4 2348.94   256.6 2343.18   273.9 2342.26   329.5 2333.71   422.4  2331.3
   437.6 2327.93   460.1  2328.5  473.112327.128   480.4  2324.5   518.9 2324.03
   526.7  2325.1   529.8 2326.81   538.4 2329.33   601.6 2329.25   622.1 2335.12
   628.8 2338.14   648.6 2341.49   698.1 2354.97   780.6 2364.63     829 2367.67
#Mann= 7 ,-1 , 0
       0    .055       0    38.4      .1       0  254.05    .055       0
  378.01     .06       0  473.11    .045       0   529.8     .06       0
  724.22      .1       0
#XS Ineff= 2 ,-1
       0  462.37 2335.68  542.73  828.98 2335.83
Permanent Ineff=
       F       F
Bank Sta=473.11,529.8
XS Rating Curve= 0 ,0
Exp/Cntr=0.5,0.3

Type RM Length L Ch R = 1 ,97138   ,565.4,541.9,499.7
XS GIS Cut Line= 2
2137961.26139006393154.9151962252138513.34460346392692.415136978
#Sta/Elev= 30
       0 2436.65    36.9 2413.06    42.7 2406.87    50.8  2394.3    53.2 2392.92
    85.5 2392.67   102.6 2379.91   120.7 2368.62   132.3 2363.78   157.6 2357.27
   183.6 2355.68   248.8 2355.07     270 2352.96   274.4 2351.17   281.4  2345.3
   303.8 2321.48   310.8 2319.76   325.2 2319.28   339.6  2319.8  347.272321.877
     368  2324.4   393.2 2324.23   421.1 2327.72     512 2327.22   518.9 2325.58
   542.2 2325.64   586.7 2331.93   658.3 2331.57   693.3 2336.06   720.2 2344.26
#Mann= 6 ,-1 , 0
       0      .1       0  302.27    .045       0   303.8    .045       0
  347.27      .1       0  464.02     .06       0  668.41      .1       0
Bank Sta=303.8,347.27
XS Rating Curve= 0 ,0
Exp/Cntr=0.5,0.3

Type RM Length L Ch R = 1 ,96596   ,38.7,38,38
XS GIS Cut Line= 6
2138703.37932839393367.6234322342138712.92786571393023.873463556
2138706.85143431392983.9430972342138634.38635613392914.533459142
 2138581.8516843 392836.373510482138547.99742131392608.075082555
#Sta/Elev= 30
       0 2518.12    84.3 2480.32   117.1 2463.24   179.5 2425.44   222.4 2396.21
   251.7  2378.1   284.5 2353.43   298.5 2338.56     314 2335.33   327.1 2325.76
   337.2 2320.69   353.5 2318.73   390.4  2320.7   396.5 2315.65  398.622312.892
   402.9 2310.17   414.4 2309.81   432.4 2309.88  436.062312.333   442.3 2317.69
   452.1 2320.05   538.5 2319.07   556.5 2325.03   566.1 2326.44   627.6 2330.19
   685.6  2334.4   720.8  2342.3     737 2350.79   770.5 2373.41   809.8 2403.94
#Mann= 5 ,-1 , 0
       0      .1       0   396.5     .06       0  398.62    .045       0
  436.06     .06       0   627.6      .1       0
#XS Ineff= 2 , 0
           385.6  2321.6     451          2321.6
Permanent Ineff=
       F       F
Bank Sta=398.62,436.06
XS Rating Curve= 0 ,0
Exp/Cntr=0.5,0.3

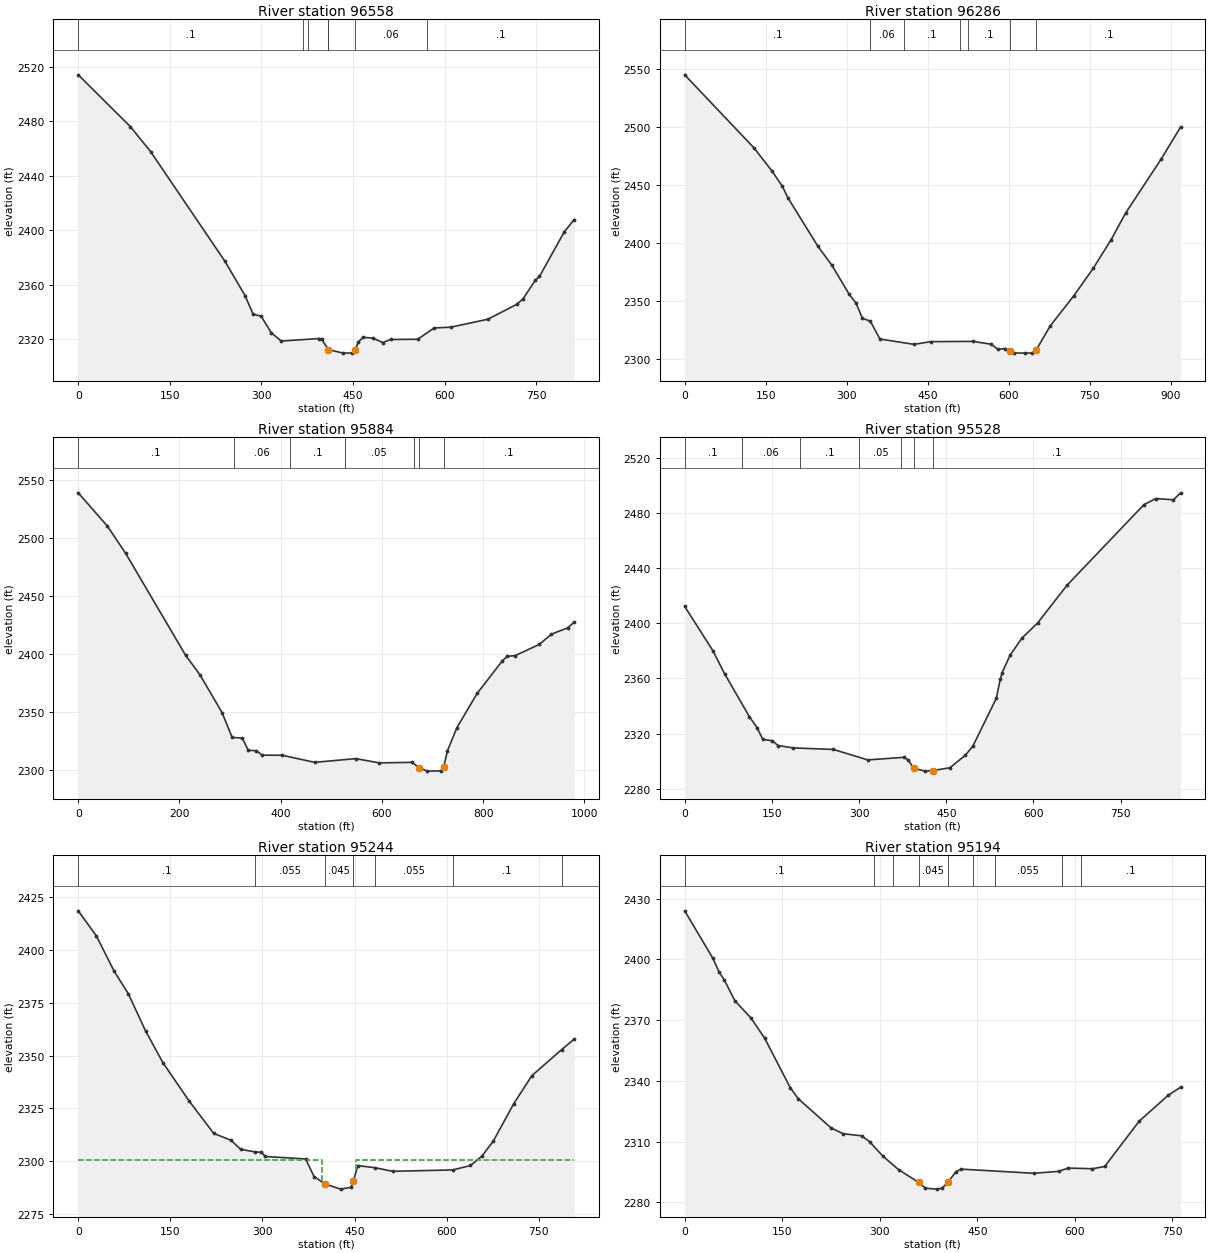
Type RM Length L Ch R = 1 ,96558   ,240,271.9,283.8
XS GIS Cut Line= 5
2138713.79597422393362.415109307 2138740.7056973392966.581911474
2138692.96268256392913.630573809 2138642.6153423392851.130698815
 2138579.2473588392595.054111227
#Sta/Elev= 30
       0 2514.06    85.3 2476.11   118.7 2457.62   240.3 2377.19   273.2 2352.04
   286.4 2338.39   299.5 2336.94   316.2 2324.75   332.4 2318.68   394.9 2320.53
   398.7 2319.91  409.712312.385     434 2309.81   448.6  2309.9  453.792312.047
   458.4 2317.85   466.5 2321.38   481.9  2320.9   498.8 2317.57   511.4 2319.82
   555.9 2319.99   582.9 2328.28     610 2328.84   670.8 2334.69   718.1 2345.62
   728.3 2349.58   748.6  2363.4   755.3 2366.06   795.9  2398.8   812.1 2407.83
#Mann= 7 ,-1 , 0
       0      .1       0  368.64     .06       0  375.66    .055       0
  408.51     .06       0  409.71    .045       0  453.79     .06       0
  571.31      .1       0
Bank Sta=409.71,453.79
XS Rating Curve= 0 ,0
Exp/Cntr=0.5,0.3

Type RM Length L Ch R = 1 ,96286   ,372.9,401.8,415.5
XS GIS Cut Line= 3
2138700.77500288393423.4848690632138941.05273755392962.373914644
2139004.94138931392569.318270311
#Sta/Elev= 30
       0 2545.15   128.4 2482.18   161.7 2462.28   180.7 2449.28   191.3 2439.08
   246.8 2397.39   272.7 2381.04   304.7 2356.04   317.1 2348.68     329 2335.49
   343.6 2333.02   361.5 2317.62   424.4 2313.04   455.5 2315.36   533.8 2315.58
     567 2313.19   580.3 2308.74   593.6 2309.44  601.562307.681   610.2 2305.62
   630.2 2305.47   643.5 2305.57  650.52 2307.95   676.7 2328.89   719.9 2354.53
   756.5 2378.57   789.7 2403.29   816.3 2426.06   882.8 2473.07   918.2 2500.21
#Mann= 7 ,-1 , 0
       0      .1       0  343.62     .06       0  406.44      .1       0
  509.67     .05       0  525.37      .1       0  601.56    .045       0
  650.52      .1       0
Bank Sta=601.56,650.52
XS Rating Curve= 0 ,0
Exp/Cntr=0.3,0.1

Type RM Length L Ch R = 1 ,95884   ,337.7,356.2,367.1
XS GIS Cut Line= 5
2138727.16372964393422.0960923142139286.37520964393040.103746057
2139303.33514947393029.5037016422139320.29541738393018.903657228
2139536.88586347392870.707103223
#Sta/Elev= 30
       0 2539.14    57.7 2510.39    93.5 2487.01     212 2398.88   240.5 2381.92
   284.2 2349.23   304.1 2327.78     324  2327.3   335.9 2316.74   351.8 2316.31
   363.7 2312.51     403  2312.4     467 2306.28   548.4 2309.49   594.9 2305.82
   658.9 2306.27  673.952301.692     689 2298.69   716.2 2298.95  721.852301.844
   729.3  2316.2   748.2 2336.37   788.4 2366.06   837.9 2394.02   847.4 2397.85
   863.3 2398.51     911  2408.2   934.9 2417.04   966.7 2422.44   979.7 2427.34
#Mann= 7 ,-1 , 0
       0      .1       0  307.71     .06       0  417.41      .1       0
  527.12     .05       0   662.4      .1       0  673.95    .045       0
  721.85      .1       0
Bank Sta=673.95,721.85
XS Rating Curve= 0 ,0
Exp/Cntr=0.3,0.1

Type RM Length L Ch R = 1 ,95528   ,263.3,284,304.5
XS GIS Cut Line= 4
2138899.80413239393345.0073357222139248.76242398393358.548975304
2139399.80411664393366.8822919732139741.47075614393454.382116973
#Sta/Elev= 30
       0  2412.2      49  2379.8    68.7  2363.4   111.3 2332.35   124.5 2324.42
   134.3 2315.91   150.7 2314.91   160.6 2311.44   186.8 2309.69   255.8  2308.6
   314.9    2301   377.3 2302.88   383.9 2301.24  394.282294.883   414.1 2292.88
  426.472293.264   456.2 2295.32   482.5 2304.25   495.6 2310.86   536.1 2345.57
   542.9 2359.47   546.3 2364.31   559.8 2376.84   580.1 2389.17   607.2 2400.22
     658 2427.63   790.1 2485.91   810.4 2490.28   840.9 2489.45   853.2 2494.46
#Mann= 7 ,-1 , 0
       0      .1       0   97.79     .06       0  199.13      .1       0
  300.47     .05       0  372.73      .1       0  394.28    .045       0
  426.47      .1       0
Bank Sta=394.28,426.47
XS Rating Curve= 0 ,0
Exp/Cntr=0.5,0.3

Type RM Length L Ch R = 1 ,95244   ,50.5,50.6,43.9
XS GIS Cut Line= 5
2138894.82513972393365.0141854732139196.04041655393572.479321733
2139232.49867697393646.2642791422139280.24169172393695.743510887
2139538.05416822393830.292126313
#Sta/Elev= 30
       0 2418.61    29.6 2406.72    58.5 2389.99    81.4 2379.41   109.8 2361.66
   138.1 2346.57     181 2328.34   220.8  2313.1   248.7 2309.88   264.6 2305.58
   288.5 2304.32   298.4 2304.17   304.5  2302.2   370.3 2301.02   384.1 2292.66
  401.792289.179   427.5 2286.72   444.4  2287.6  448.052290.488   455.2 2297.87
   482.6 2296.91   511.9 2295.18   609.9 2295.81   638.8 2297.92   657.3 2302.36
   675.8 2309.41   709.1 2327.15   738.7 2340.48   787.4 2352.89   807.6 2357.82
#Mann= 7 ,-1 , 0
       0      .1       0   288.5    .055       0  401.79    .045       0
  448.05      .1       0   482.6    .055       0   609.9      .1       0
   787.4      .1       0
#XS Ineff= 2 , 0
           396.8  2300.6  453.05          2300.6
Permanent Ineff=
       F       F
Bank Sta=401.79,448.05
XS Rating Curve= 0 ,0
Exp/Cntr=0.5,0.3

Type RM Length L Ch R = 1 ,95194   ,273.9,252.9,232
XS GIS Cut Line= 6
2138902.63746005393423.1738460662139157.84593914393608.937910229
2139203.85273689393677.5142166472139236.83889139393717.444911063
2139428.67905889393824.2156948892139513.74877064393862.410172313
#Sta/Elev= 30
       0 2424.05    43.3 2400.63      53 2393.81    61.1 2389.78    77.3 2379.55
     102 2371.07   123.2 2360.98   162.5 2336.55   174.8 2331.13   225.2 2316.72
   243.7 2313.86   272.1 2312.84   284.3 2309.96   304.5 2302.89     329  2296.1
  360.122289.767   370.1 2286.94   387.9 2286.47   396.1 2286.99  404.712289.779
   417.1 2295.06   425.2 2296.36   537.1 2294.31   575.2 2295.25   589.7 2296.88
   627.2 2296.55     646 2297.66     699 2320.04   744.1 2332.97   762.8 2336.87
#Mann= 9 ,-1 , 0
       0      .1       0  291.12    .055       0  320.34      .1       0
  360.12    .045       0  404.71      .1       0  443.77     .06       0
  477.39    .055       0  579.94      .1       0  610.18      .1       0
Bank Sta=360.12,404.71
XS Rating Curve= 0 ,0
Exp/Cntr=0.5,0.3

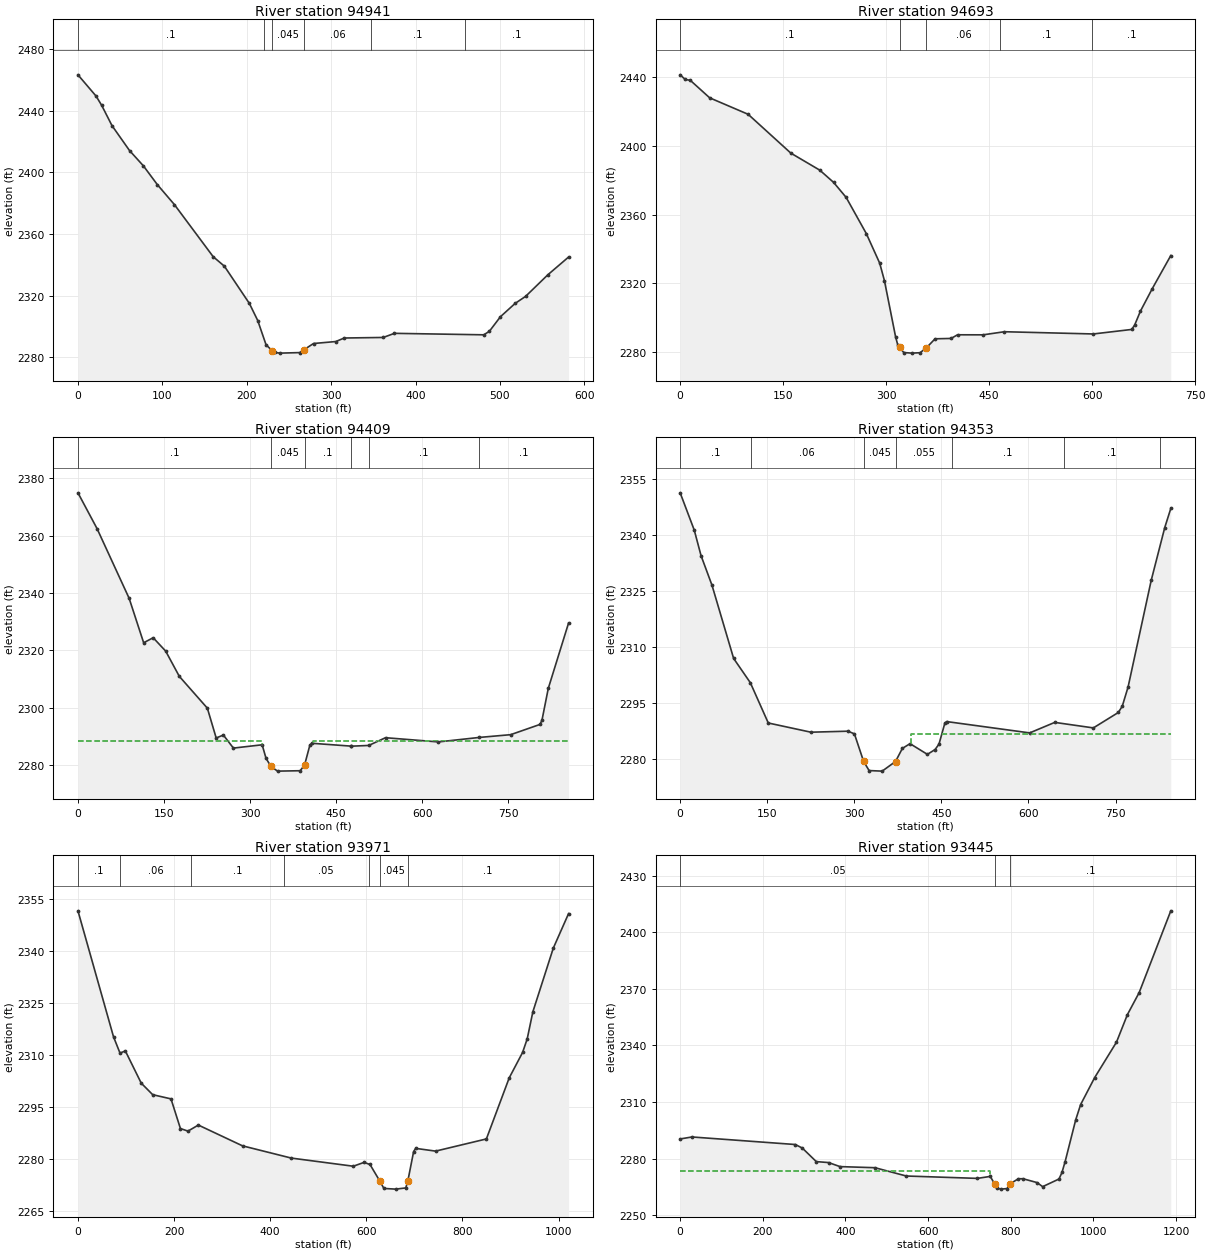
Type RM Length L Ch R = 1 ,94941   ,257.4,248,240.2
XS GIS Cut Line= 4
 2138960.2210063393936.6738033152139166.47092189393912.715517893
2139255.01241148393902.2988720542139537.30416971393866.882276222
#Sta/Elev= 30
       0 2463.38    21.5 2449.55    28.1 2443.57    40.3 2430.41    61.1 2414.19
    77.6  2404.2    94.1 2392.01   114.3 2379.06   160.2 2345.23   173.5 2339.04
   203.1 2314.84     213 2303.75   222.9 2287.94  229.922284.267   233.1 2282.97
   239.5 2282.56   262.6  2282.9  268.132284.884   279.1 2288.81   305.5 2290.09
   315.5 2292.38   361.7 2292.74     375 2295.42   480.8 2294.46   487.4 2296.71
   500.6 2306.24     518 2314.87   530.4 2319.45   556.8  2333.5   581.3 2344.99
#Mann= 6 ,-1 , 0
       0      .1       0  220.19     .06       0  229.92    .045       0
  268.13     .06       0  347.14      .1       0   458.2      .1       0
Bank Sta=229.92,268.13
XS Rating Curve= 0 ,0
Exp/Cntr=0.3,0.1

Type RM Length L Ch R = 1 ,94693   ,306.5,283.5,244.7
XS GIS Cut Line= 4
 2138968.3272893394302.200959399 2139222.4941038394176.159544811
 2139316.2439163394116.7843354792139523.53582455393873.034494892
#Sta/Elev= 30
       0 2441.41     7.4  2438.7    14.7 2438.23      43 2428.01      99 2418.43
   161.2 2395.82   203.4 2385.89   223.5 2378.77   241.8 2370.01   271.1 2348.99
   290.6 2331.77   297.5  2321.6   313.8  2288.8   316.9  2284.2  319.612282.689
   325.7 2279.69   337.6 2279.36   349.5  2279.6  358.77 2282.52   371.3  2287.7
   394.6 2287.91     404 2290.04   441.2 2290.01   472.3 2291.82   601.8 2290.52
   657.5 2293.14   661.8 2295.55   670.4 2303.83   687.6  2316.9   714.6 2336.18
#Mann= 5 ,-1 , 0
       0      .1       0  319.61    .045       0  358.77     .06       0
  466.22      .1       0  600.46      .1       0
Bank Sta=319.61,358.77
XS Rating Curve= 0 ,0
Exp/Cntr=0.5,0.3

Type RM Length L Ch R = 1 ,94409   ,58,56.3,61.2
XS GIS Cut Line= 6
 2139569.5957718394699.1739187242139468.55430722394423.132147983
 2139446.8460173394379.2467370632139430.59572172394319.663522899
2139419.12002289 394262.788636642139525.23988938393885.075809389
#Sta/Elev= 30
       0 2374.93    33.3 2362.45    89.2 2338.16   114.5 2322.66   131.1 2324.41
   152.9 2319.75   176.6 2310.96   225.5 2299.86   240.9 2289.46   253.4 2290.49
   270.9 2285.94     321 2287.09   327.8 2282.35  336.392279.532   347.8 2277.91
   387.2 2278.05  394.922280.035   404.2    2287   407.6 2287.62   476.4 2286.62
   476.4 2286.61   506.7 2286.86     536 2289.56   628.1 2288.09   699.6 2289.66
   754.1 2290.62   805.3  2294.2   808.7 2295.73   819.6 2306.73     855 2329.56
#Mann= 6 ,-1 , 0
       0      .1       0  336.39    .045       0  394.92      .1       0
   476.4     .06       0   506.7      .1       0   699.6      .1       0
#XS Ineff= 2 , 0
           321.4  2288.5   409.9          2288.5
Permanent Ineff=
       F       F
Bank Sta=336.39,394.92
XS Rating Curve= 0 ,0
Exp/Cntr=0.5,0.3

Type RM Length L Ch R = 1 ,94353   ,388.5,381.8,366.6
XS GIS Cut Line= 6
 2139628.8279368394691.6801673172139546.89207706394481.940757394
2139503.82785872394398.2775388962139491.67499588394351.402632639
2139486.46667297394315.8121526392139557.25688572393880.048260391
#Sta/Elev= 30
       0 2351.32    24.3  2341.3      36 2334.45    54.8 2326.53    92.1 2306.87
   120.9 2300.35   151.8 2289.54   225.2 2287.07   289.1 2287.34   300.2 2286.62
  316.052279.211   325.5 2276.77     348 2276.62  370.992279.203   382.8 2282.72
     396 2283.99   425.9 2281.12   439.2 2282.42   445.9 2283.88   455.8 2289.41
   459.1 2289.92   602.1 2286.88   645.3  2289.7   711.8 2288.22   754.8 2292.36
   761.6 2294.04   771.6 2299.19   811.5 2327.85   834.8    2342   845.2 2347.12
#Mann= 7 ,-1 , 0
       0      .1       0  121.58     .06       0  316.05    .045       0
  370.99    .055       0  469.12      .1       0  660.96      .1       0
  826.37      .1       0
#XS Ineff= 1 ,-1
  397.85  845.16 2286.62
Permanent Ineff=
       F
Bank Sta=316.05,370.99
XS Rating Curve= 0 ,0
Exp/Cntr=0.5,0.3

Type RM Length L Ch R = 1 ,93971   ,520.4,525.6,534.3
XS GIS Cut Line= 4
2140011.75335206394831.2058068962139860.48003255394265.117700234
2139782.70230097394163.7287953942139610.48020448393909.562308982
#Sta/Elev= 30
       0 2351.59      74  2315.3    87.5  2310.6    98.6 2311.23   131.7 2301.94
   155.5 2298.62   193.6 2297.41   213.2 2288.87   228.9 2288.12   250.5 2289.87
   342.4 2283.88   444.1 2280.35   572.9 2278.01   595.2 2279.11   607.6 2278.51
   627.4 2273.89   636.5 2271.61   660.9 2271.41     682 2271.75   686.2 2273.64
   698.4 2282.24   702.7 2283.15   744.1 2282.36   849.8 2285.87   897.3 2303.47
   925.1 2310.79   934.7 2314.69   946.5 2322.51     989 2340.84  1020.8  2350.8
#Mann= 7 ,-1 , 0
       0      .1       0   87.42     .06       0  235.01      .1       0
  428.25     .05       0  605.16      .1       0   627.4    .045       0
   686.2      .1       0
Bank Sta=627.4,686.2
XS Rating Curve= 0 ,0
Exp/Cntr=0.3,0.1

Type RM Length L Ch R = 1 ,93445   ,1205.8,1222,1240
XS GIS Cut Line= 3
2140368.81333347394767.8955660612140472.44960913394346.652970225
2140102.03105864393690.580791563
#Sta/Elev= 30
       0 2290.49    28.7 2291.54   278.7 2287.54   295.6 2285.66   329.4 2278.49
   359.2 2277.98   386.8 2275.84   471.2 2275.26   547.2 2270.86   719.2  2269.6
   750.3 2270.65  761.382266.514   765.7 2264.43     777 2263.91   791.4 2264.23
  797.412266.589   818.4 2269.41   829.7  2269.4   863.6 2267.38   877.1 2265.22
   916.7 2269.27   923.9 2272.77   931.5 2278.47   957.2  2300.7   969.1 2308.74
    1003    2323  1055.8 2341.77  1082.2 2356.35  1110.7 2368.04  1187.2 2411.34
#Mann= 3 ,-1 , 0
       0     .05       0  761.38    .045       0  797.41      .1       0
#XS Ineff= 2 , 0
          749.07 2273.27
Permanent Ineff=
       F       F
Bank Sta=761.38,797.41
XS Rating Curve= 0 ,0
Exp/Cntr=0.3,0.1

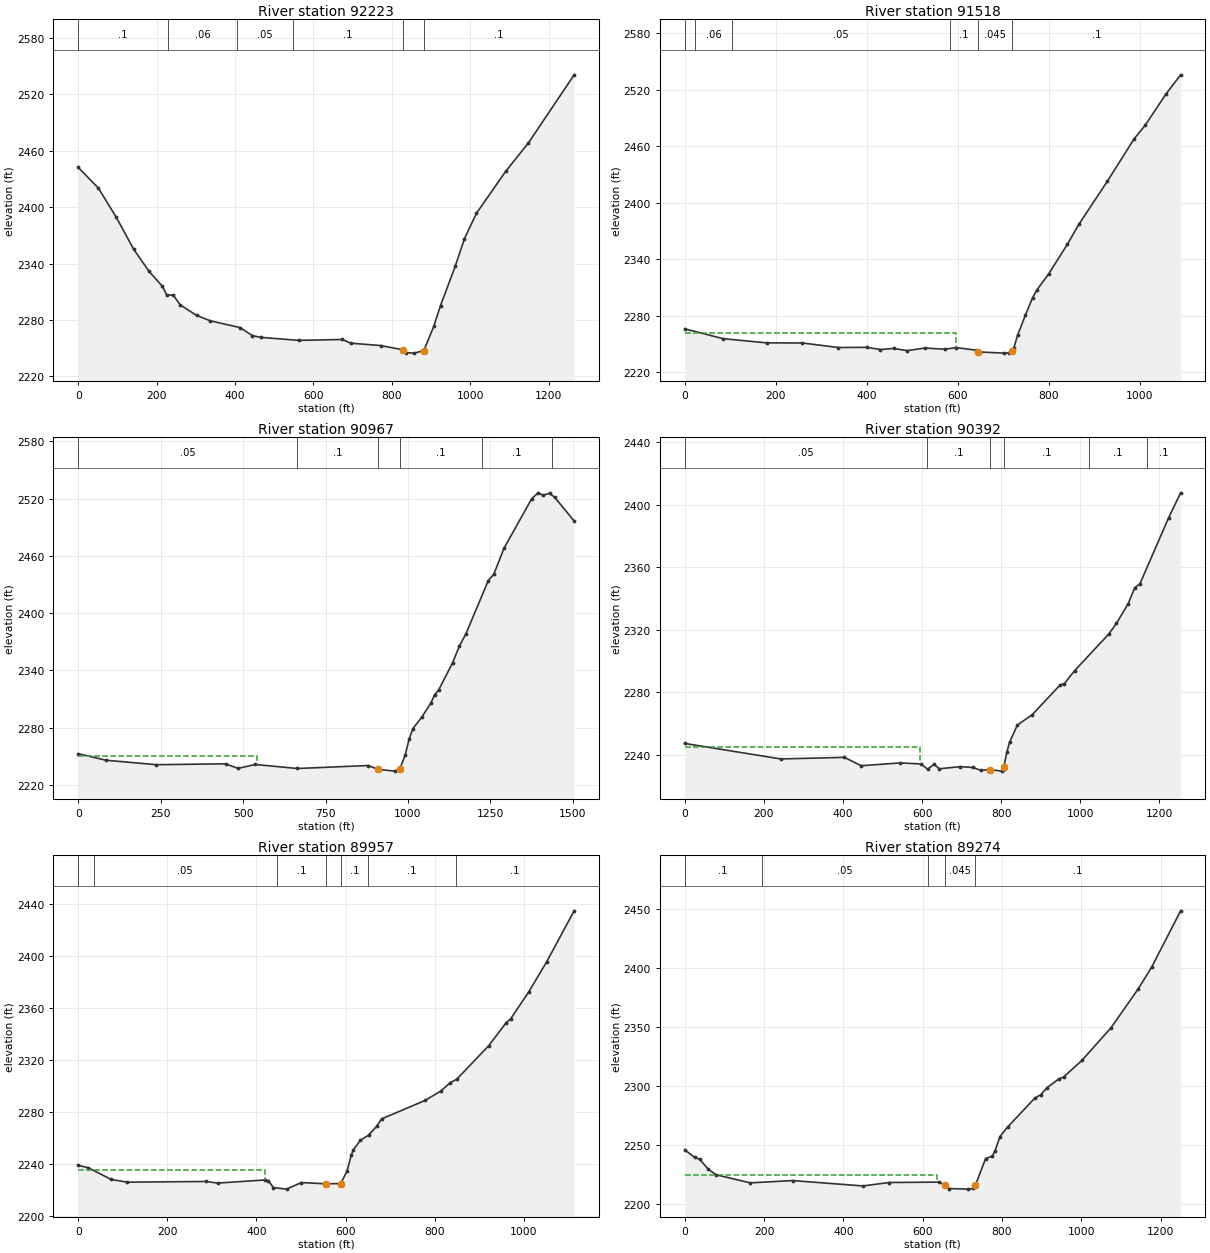
Type RM Length L Ch R = 1 ,92223   ,713.4,705.3,690.8
XS GIS Cut Line= 5
2141158.27238446394608.1632739752141414.52252814393881.079754397
2141527.02230313 393462.329935732141531.18896148 393462.32993573
 2141547.8555948 393408.16304931
#Sta/Elev= 30
       0 2442.29    51.5 2420.25    96.7 2389.49   141.9 2354.93   180.9 2331.57
     215 2315.66   225.4 2306.75   242.8  2306.2   260.2 2295.95   301.9 2284.83
   336.7 2279.04   412.4 2271.84   444.5 2263.25   465.4  2261.4   562.8  2258.2
   674.1 2259.12     695  2255.2   771.5 2252.69   829.62248.069   836.8  2245.1
   856.5  2244.6  881.762247.218   907.4 2273.39   924.4  2295.2   961.8 2336.91
   985.5 2366.45  1016.1 2393.46  1091.2 2438.39  1148.6 2468.32  1265.4 2540.85
#Mann= 6 ,-1 , 0
       0      .1       0  227.91     .06       0  405.51     .05       0
  548.16      .1       0   829.6    .045       0  881.76      .1       0
Bank Sta=829.6,881.76
XS Rating Curve= 0 ,0
Exp/Cntr=0.3,0.1

Type RM Length L Ch R = 1 ,91518   ,565.1,551.3,530.5
XS GIS Cut Line= 2
2142139.63820389394631.0510234832142099.70750947393542.509237304
#Sta/Elev= 30
       0 2266.34    84.6 2255.86   179.8 2251.43   258.6 2251.28   337.4 2246.48
   399.8 2246.66     430 2244.32   458.9  2245.5   488.4 2243.18   527.8 2245.91
   571.2 2244.72   596.8 2246.39   639.4 2243.67  644.412241.824   701.8 2240.52
   711.7 2240.81  719.642243.239   723.2 2246.31   731.4 2259.77   748.5 2281.02
   764.2  2299.4     774 2307.85   799.2 2324.42   840.4 2355.91     866 2377.38
   928.3 2422.91   987.4 2468.12  1011.4 2482.35  1056.4 2515.07  1089.3 2535.94
#Mann= 6 ,-1 , 0
       0     .06       0   22.56     .06       0  103.45     .05       0
  583.16      .1       0  644.41    .045       0  719.64      .1       0
#XS Ineff= 2 , 0
          596.26 2261.56
Permanent Ineff=
       F       F
Bank Sta=644.41,719.64
XS Rating Curve= 0 ,0
Exp/Cntr=0.3,0.1

Type RM Length L Ch R = 1 ,90967   ,545.8,574.8,585.1
XS GIS Cut Line= 5
2142995.54101963394643.2035582212142626.19825439 393780.11178048
2142614.75044264393763.7122069752142603.30230281 393747.31263347
2142324.09157513393302.320413232
#Sta/Elev= 30
       0 2252.55    83.8 2245.74   237.2 2241.03   447.2 2241.95   484.7 2237.15
   537.2 2241.25   664.6 2237.05   879.6 2240.16  909.362236.106   960.7 2234.29
  975.942236.923     992 2251.42  1003.6 2267.91  1015.2 2278.95  1041.4 2290.57
  1069.5 2305.62  1081.1 2314.56  1092.7 2319.11  1135.3 2347.76  1155.7 2365.22
  1175.8 2378.28  1243.7 2434.12  1260.4 2440.73  1291.3 2467.98  1375.4 2519.99
  1394.8  2526.1  1410.3 2523.64  1429.7 2525.67  1445.2  2521.3  1504.1 2496.55
#Mann= 6 ,-1 , 0
       0     .05       0  663.54      .1       0  909.36    .045       0
  975.94      .1       0 1223.69      .1       0 1437.53      .1       0
#XS Ineff= 2 , 0
          542.39 2250.13
Permanent Ineff=
       F       F
Bank Sta=909.36,975.94
XS Rating Curve= 0 ,0
Exp/Cntr=0.3,0.1

Type RM Length L Ch R = 1 ,90392   ,444.9,435.4,427.7
XS GIS Cut Line= 4
2143176.09643281394545.9816398172143137.90195538393851.537162557
2143148.31860122393688.3426070662143108.38823488393295.981515139
#Sta/Elev= 30
       0  2247.2   242.6 2237.27   403.6 2238.27   446.2 2232.91   544.9 2234.72
   597.5 2234.06   613.9  2230.7   630.4 2233.81   643.5 2230.98   696.1 2232.32
   728.9  2231.8   748.7 2229.92  770.712230.479     801 2229.46   804.6 2229.96
  806.692232.381   814.4 2241.76     821 2247.92   840.7 2258.95   878.4 2265.63
   949.5 2284.83   959.4 2285.44   985.3 2293.76  1071.5 2317.17  1091.3 2324.13
    1121 2336.75  1137.5 2346.98  1150.7 2349.53  1223.2 2391.84  1253.4 2407.73
#Mann= 6 ,-1 , 0
       0     .05       0  612.15      .1       0  770.71    .045       0
  806.69      .1       0 1021.21      .1       0  1168.2      .1       0
#XS Ineff= 2 , 0
          595.02 2244.91
Permanent Ineff=
       F       F
Bank Sta=770.71,806.69
XS Rating Curve= 0 ,0
Exp/Cntr=0.3,0.1

Type RM Length L Ch R = 1 ,89957   ,690.8,683.1,676.6
XS GIS Cut Line= 5
2143825.40189272 394195.287131222143574.25016405393702.297631651
2143565.01100931393684.5594781492143555.77218264393666.821324646
2143324.06923397393201.728094727
#Sta/Elev= 30
       0 2239.06    21.9 2237.39    74.1 2228.23   110.3 2226.16     287 2226.68
   312.8 2225.47   419.6 2227.87   426.9 2227.17     438 2222.02   467.4 2220.81
   500.6 2225.85   555.8 2224.92   589.1 2225.09   603.3 2234.81   613.1 2247.34
     617 2250.81   633.1 2258.39   651.5 2262.29   669.4 2269.02   680.8 2274.84
   778.9 2289.11   813.7  2296.3   834.7 2302.69   849.4 2305.34   921.4 2331.25
   959.4 2348.41   970.3 2351.77  1010.7 2372.39  1050.9  2395.5  1112.9  2434.9
#Mann= 7 ,-1 , 0
       0      .1       0   34.44     .05       0   445.4      .1       0
   555.8    .045       0   589.1      .1       0  650.96      .1       0
  847.68      .1       0
#XS Ineff= 2 , 0
          419.69  2235.8
Permanent Ineff=
       F       F
Bank Sta=555.8,589.1
XS Rating Curve= 0 ,0
Exp/Cntr=0.3,0.1

Type RM Length L Ch R = 1 ,89274   ,352,354.4,353.4
XS GIS Cut Line= 3
 2144531.9992328394122.370282307 2144242.0687103393561.606640056
2143924.36035623393030.356390223
#Sta/Elev= 30
       0 2245.85    24.8  2239.4    37.8 2237.73    59.7 2229.28    79.1 2224.65
   165.2 2217.76   272.3 2219.69   449.6 2215.14   514.9 2218.04   641.4 2218.39
  657.482215.725   665.9 2212.95   715.5 2212.44   727.5 2213.01  732.812215.631
   758.6 2238.37   775.8 2240.43   782.5  2244.9   794.9 2257.06     814 2265.06
   882.8 2289.66   897.3 2292.41   913.4 2298.44     944 2306.06   955.5 2307.57
  1001.3 2321.54    1075 2349.36  1142.8 2381.96  1177.3  2400.7  1250.3 2448.46
#Mann= 5 ,-1 , 0
       0      .1       0  194.08     .05       0  613.83      .1       0
  657.48    .045       0  732.81      .1       0
#XS Ineff= 2 , 0
          637.01 2224.18
Permanent Ineff=
       F       F
Bank Sta=657.48,732.81
XS Rating Curve= 0 ,0
Exp/Cntr=0.3,0.1