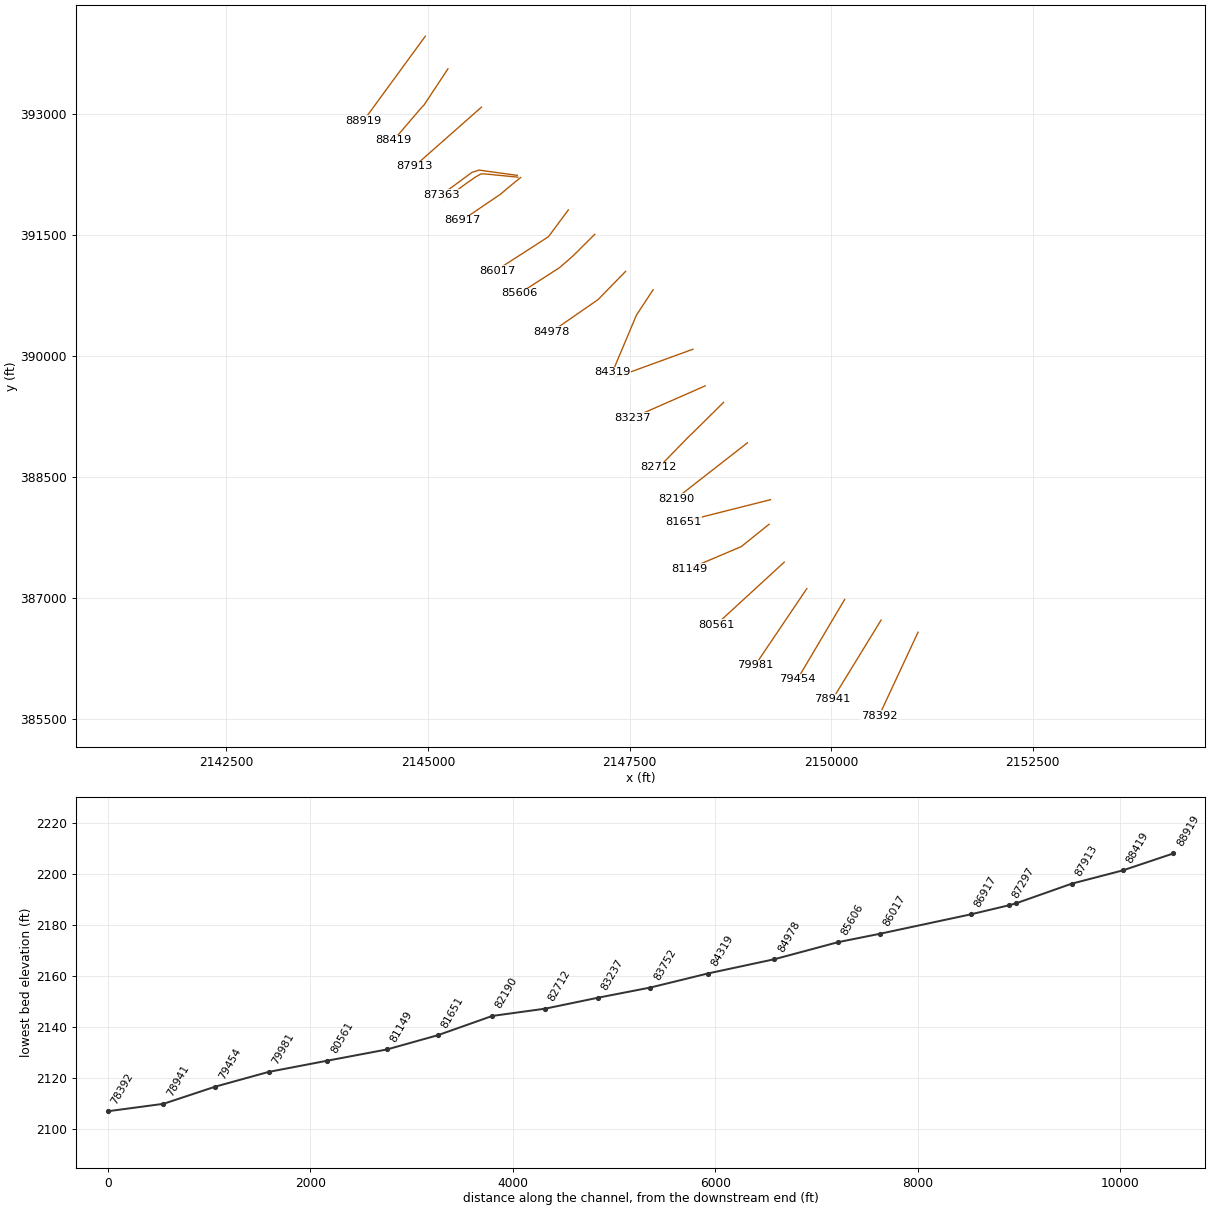
HEC-RAS study SPRINGCK.prj: SPRINGCK

--- SPRINGCK.g01 (geometry) --- (continued)

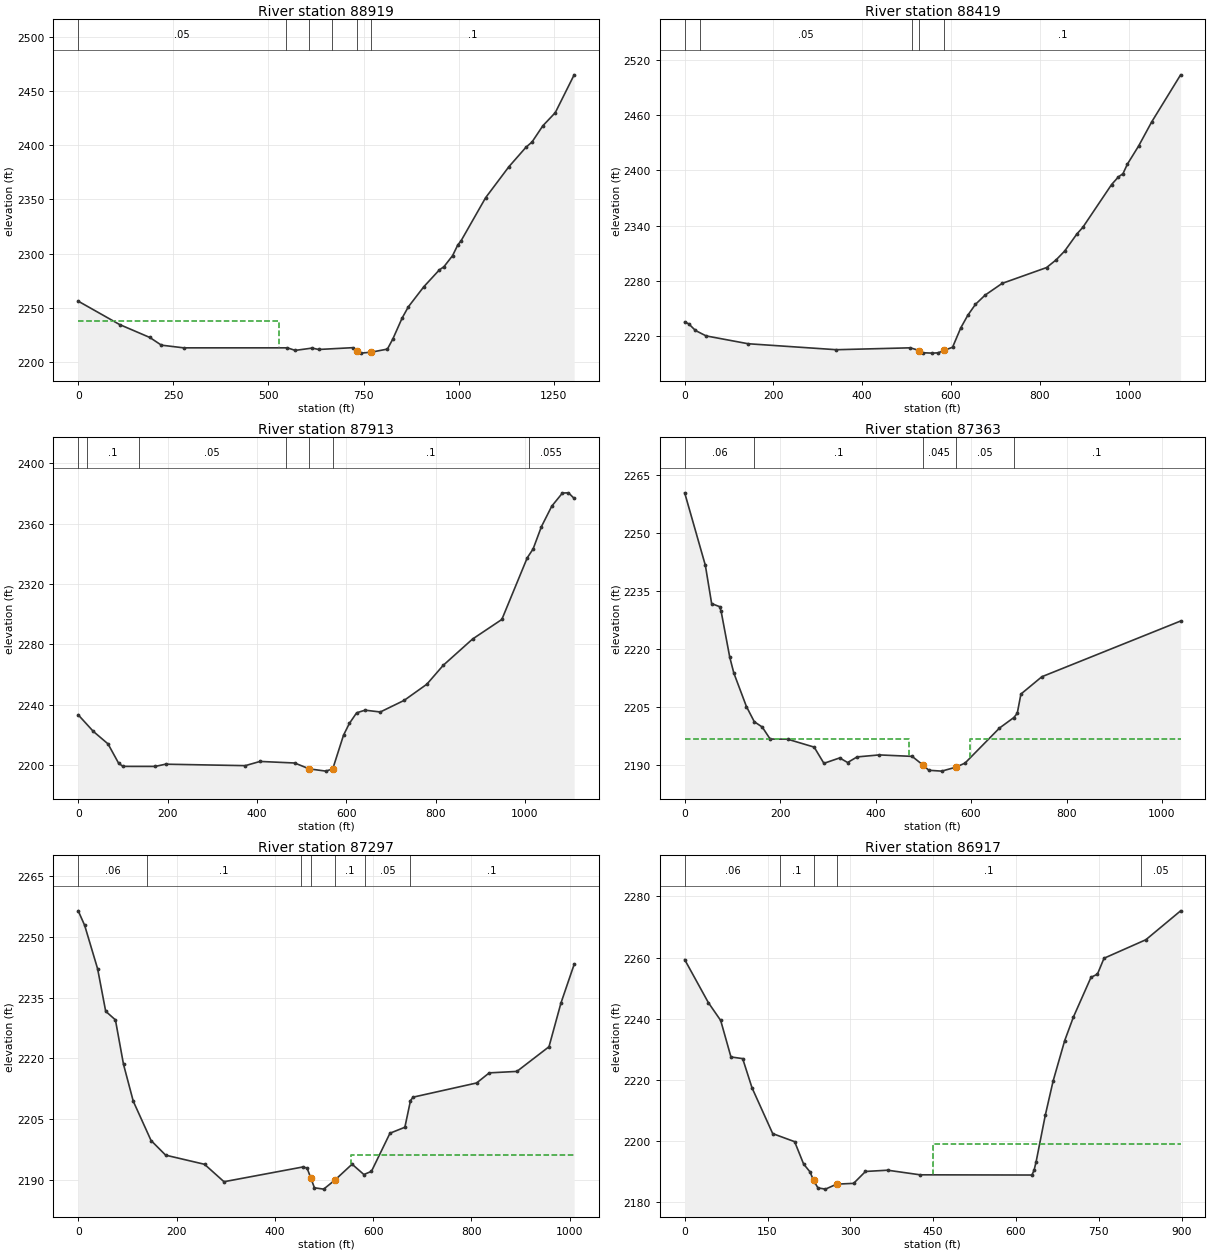
Type RM Length L Ch R = 1 ,88919   ,501.9,499.9,494.3
XS GIS Cut Line= 2
2144967.76312505393960.9119438082144198.58782613392908.640426308
#Sta/Elev= 30
       0 2256.04     109 2234.39   188.1 2222.49   218.6 2215.38   277.3 2212.89
   549.6  2212.9   570.4 2210.54   614.9 2212.68   631.8 2211.38   721.4 2213.05
  733.582210.029   742.8 2208.01  769.612208.853   812.6 2211.74     827 2221.19
   851.4 2240.51   867.7 2250.83   908.3 2269.36     949 2284.89   961.2 2287.86
     984 2298.16   997.7 2308.07  1005.9 2311.63  1070.8 2351.67  1131.8 2380.23
  1176.5 2398.14  1192.8 2403.18  1221.2 2418.13  1253.8 2430.23  1303.4 2465.18
#Mann= 6 ,-1 , 0
       0     .05       0  546.81      .1       0  607.43     .05       0
  667.45      .1       0  733.58    .045       0  769.61      .1       0
#XS Ineff= 2 , 0
          527.67 2237.31
Permanent Ineff=
       F       F
Bank Sta=733.58,769.61
XS Rating Curve= 0 ,0
Exp/Cntr=0.3,0.1

Type RM Length L Ch R = 1 ,88419   ,508.9,506.2,503.7
XS GIS Cut Line= 5
2145248.23303655393556.7257443072144951.52103156393107.740093723
2144937.35111238393093.625292555 2144923.2701038393079.422565058
2144572.95649996392669.659605056
#Sta/Elev= 30
       0 2235.28     9.1  2233.2    24.3 2225.97    48.3 2220.08   142.8 2211.56
   341.9 2205.06   508.5 2207.12  528.392204.184   536.1 2201.75   558.2 2201.35
   570.9 2201.67   584.72204.356   603.5 2207.75   622.1  2228.9   637.9 2242.57
   655.1 2254.39   676.7 2264.37   715.2 2277.17   815.2 2294.36   836.4 2302.56
   856.1 2312.36   883.9  2331.1   896.9 2338.07   961.8 2384.67   977.2    2393
   987.4 2396.46   997.4 2406.86  1022.7 2426.58  1052.2 2452.82  1117.3 2503.95
#Mann= 5 ,-1 , 0
       0      .1       0   34.31     .05       0  512.57      .1       0
  528.39    .045       0   584.7      .1       0
Bank Sta=528.39,584.7
XS Rating Curve= 0 ,0
Exp/Cntr=0.3,0.1

Type RM Length L Ch R = 1 ,87913   ,562.2,550.2,534
XS GIS Cut Line= 2
2145663.72203498393081.4340439742144831.30703314392346.527705386
#Sta/Elev= 30
       0  2233.4    33.8 2222.44    66.7 2214.16    90.7 2201.23   100.4 2199.26
   172.4 2199.24   195.5 2200.71     374 2199.75   407.2 2202.54   484.6  2201.5
  517.532197.594   554.6 2196.12  569.94 2197.64     594  2219.9     607 2227.66
   623.4 2234.73   642.2 2236.48   676.4 2235.29   729.7 2242.96   780.5 2253.65
   817.2 2266.17   882.9 2283.58   948.5 2296.56  1005.4  2337.4  1018.5 2343.24
  1037.1 2358.01  1060.3 2371.59  1084.2 2380.29  1097.7 2380.41  1110.4 2376.73
#Mann= 7 ,-1 , 0
       0     .06       0   19.15      .1       0  135.02     .05       0
  465.37      .1       0  517.53    .045       0  569.94      .1       0
 1008.35    .055       0
Bank Sta=517.53,569.94
XS Rating Curve= 0 ,0
Exp/Cntr=0.5,0.3

Type RM Length L Ch R = 1 ,87363   ,57.3,65.6,75
XS GIS Cut Line= 5
2146107.71950655392235.1237287222145635.67090997392300.545513898
2145545.39320339392272.7676823142145416.92101939392177.281652808
2145168.65708022391994.989694566
#Sta/Elev= 30
       0 2260.49    43.3 2241.72    56.5  2231.8    73.1 2231.01    76.4 2229.79
    94.4 2217.94   102.9 2213.85   129.4 2205.13   145.9  2201.2   162.5 2199.83
   179.1 2196.72   215.5 2196.69   271.3 2194.63   291.7 2190.43   324.8 2191.83
   341.4 2190.64   361.2 2192.09   407.6 2192.61   476.6 2192.23  499.362189.987
   511.5 2188.63   538.5 2188.41  567.762189.418   587.3 2190.48   659.6 2199.57
   689.7 2202.29   696.8 2203.38   704.5 2208.37   748.4 2212.86  1039.1 2227.29
#Mann= 5 ,-1 , 0
       0     .06       0   145.9      .1       0  499.36    .045       0
  567.76     .05       0   689.7      .1       0
#XS Ineff= 2 , 0
           469.3  2196.8   597.7          2196.8
Permanent Ineff=
       F       F
Bank Sta=499.36,567.76
XS Rating Curve= 0 ,0
Exp/Cntr=0.5,0.3

Type RM Length L Ch R = 1 ,87297   ,378.3,380.3,389.5
XS GIS Cut Line= 6
2146113.96949406392213.248444393 2145702.1779948392253.832024649
2145658.84474814392253.8320246492145590.53189264392215.475802138
2145475.94878846  392135.61474142145206.67800155391938.248666316
#Sta/Elev= 30
       0 2256.51    13.1 2252.92    39.5 2242.16    55.9 2231.67    75.7 2229.54
    92.2 2218.52     112 2209.43   148.2 2199.71   177.9 2196.09     257 2193.83
   296.6 2189.52   457.1 2193.17   465.6  2192.9  473.442190.371   480.6 2188.02
   499.4 2187.69  522.412189.946   557.2 2193.86   581.2  2191.3   596.6 2192.09
   634.3 2201.52   664.6 2202.99     676 2209.56   681.2 2210.43   810.5 2213.94
   836.3 2216.44   892.5  2216.8   957.8  2222.9   982.2 2233.73    1009 2243.27
#Mann= 7 ,-1 , 0
       0     .06       0  140.31      .1       0  452.93      .1       0
  473.44    .045       0  522.41      .1       0  583.42     .05       0
  675.49      .1       0
#XS Ineff= 1 ,-1
  555.52 1008.99 2196.18
Permanent Ineff=
       F
Bank Sta=473.44,522.41
XS Rating Curve= 0 ,0
Exp/Cntr=0.5,0.3

Type RM Length L Ch R = 1 ,86917   ,898,900,892.8
XS GIS Cut Line= 4
2146149.61706056392208.9882823082146003.40245797392090.194556639
2145898.19433506392000.6110743882145425.27762997391679.777726561
#Sta/Elev= 30
       0 2259.32    42.8 2245.24    65.2 2239.37    83.8 2227.41     105 2226.87
   121.9 2217.32   159.4 2202.29   199.1 2199.65   215.3 2192.35     227 2189.73
  233.382186.953   241.3  2184.5   254.9  2184.1  275.152185.728   305.9 2185.99
   327.4 2189.89   367.5  2190.3   426.3 2188.79   628.7 2188.72   632.6 2190.25
   636.4 2193.11     653 2208.35   667.2 2219.58   688.1 2232.77     704 2240.55
   735.7  2253.5   747.4 2254.56   759.3 2259.76   835.1 2265.83     898  2275.3
#Mann= 5 ,-1 , 0
       0     .06       0  173.09      .1       0  233.38    .045       0
  275.15      .1       0  825.99     .05       0
#XS Ineff= 2 , 0
                          450.48         2198.97
Permanent Ineff=
       F       F
Bank Sta=233.38,275.15
XS Rating Curve= 0 ,0
Exp/Cntr=0.3,0.1

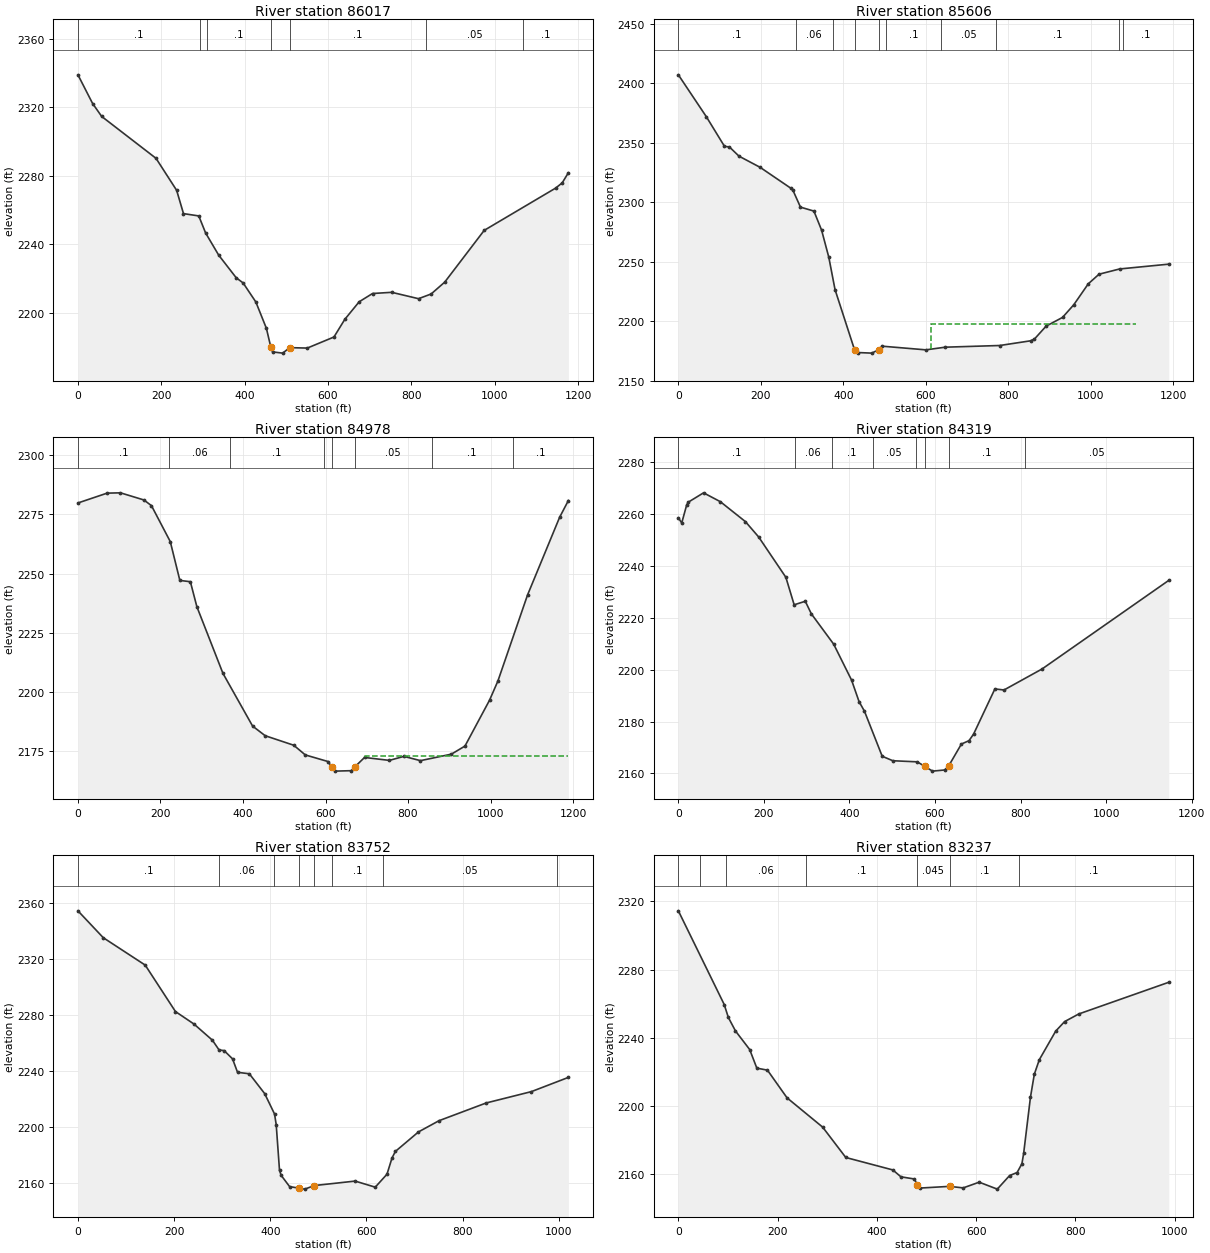
Type RM Length L Ch R = 1 ,86017   ,406.5,410.9,410.8
XS GIS Cut Line= 5
2146740.90262339391806.8611338142146494.02746098391474.569475561
2146226.31933497391301.6528266372145884.65269548391081.861271471
2145856.91817088391055.732714817
#Sta/Elev= 30
       0 2338.84    35.2 2322.11      57 2314.56   187.4 2290.12   236.9 2271.44
   253.3 2257.86     290 2256.51   306.4 2246.57   337.7 2233.67   379.9 2220.41
   396.4 2217.42     427 2206.29   452.3 2190.91  462.742180.113   467.3 2177.17
   491.3 2176.46  508.272179.654   550.4 2179.41   614.4 2185.86   640.5 2196.18
   674.9 2206.42     707 2211.25     753 2211.94   817.4 2208.22   847.7 2210.98
   880.3  2217.9     975 2248.09  1146.5 2272.76  1162.2 2275.81    1177  2281.7
#Mann= 7 ,-1 , 0
       0      .1       0  294.04     .06       0  310.35      .1       0
  462.74    .045       0  508.27      .1       0  834.65     .05       0
 1068.14      .1       0
Bank Sta=462.74,508.27
XS Rating Curve= 0 ,0
Exp/Cntr=0.3,0.1

Type RM Length L Ch R = 1 ,85606   ,633.6,628.6,626.4
XS GIS Cut Line= 4
2147067.55190447391503.8230259722146796.71845664 391234.72579515
2146633.52422921391092.3645313082146136.99635088390772.920288309
#Sta/Elev= 30
       0 2407.17    67.9 2371.92   111.8 2347.06   123.8 2346.51     147 2338.79
   198.2  2329.4   272.7 2311.82   277.4 2310.37     296 2295.93   328.6 2292.61
   347.2 2276.59   364.7 2253.77   379.8 2226.58  427.042176.025   434.4 2173.69
   469.2 2173.19  485.222176.097   494.4 2179.02     600 2175.94     647 2178.19
   779.1  2179.6   853.6 2183.54   863.1 2185.02   891.5  2195.9   931.2 2203.21
   958.5 2213.86   993.6 2231.45  1019.7 2239.54  1069.6 2243.95  1188.8    2248
#Mann= 10 ,-1 , 0
       0      .1       0  284.28     .06       0  374.35      .1       0
  427.04    .045       0  485.22      .1       0  503.99      .1       0
  636.41     .05       0  769.65      .1       0 1068.96      .1       0
 1076.94      .1       0
#XS Ineff= 1 ,-1
  613.24 1109.982197.868
Permanent Ineff=
       F
Bank Sta=427.04,485.22
XS Rating Curve= 0 ,0
Exp/Cntr=0.3,0.1

Type RM Length L Ch R = 1 ,84978   ,644,658.8,674.3
XS GIS Cut Line= 3
2147451.23256755391045.489625067 2147109.2184878390694.795116484
2146534.56576572390297.225701645
#Sta/Elev= 30
       0 2279.86    70.7 2284.02   103.1 2284.15   159.9 2281.13   178.2 2278.72
   223.8 2263.53     247 2247.12   272.5 2246.57   288.2 2236.03   351.4 2207.84
   423.3 2185.54   453.8 2181.47   523.1 2177.44     551 2173.35   606.8 2170.52
  614.522168.188   622.8  2166.5   662.7 2166.69  670.292168.172   694.6 2172.28
   754.7 2171.04   790.1 2172.74   830.1 2170.93     905 2173.67     938  2177.1
   997.6 2196.51  1017.8  2204.6  1089.6 2240.95  1167.4 2273.82  1188.6  2280.9
#Mann= 8 ,-1 , 0
       0      .1       0  221.15     .06       0     368      .1       0
   597.3      .1       0  614.52    .045       0  670.29     .05       0
  857.41      .1       0 1053.58      .1       0
#XS Ineff= 2 , 0
                          695.42         2172.84
Permanent Ineff=
       F       F
Bank Sta=614.52,670.29
XS Rating Curve= 0 ,0
Exp/Cntr=0.3,0.1

Type RM Length L Ch R = 1 ,84319   ,581.2,566.7,543.2
XS GIS Cut Line= 3
2147791.42348821390816.1928395632147584.82613239390501.956591398
2147286.21518105  389791.8871454
#Sta/Elev= 30
       0  2258.5     7.9 2256.53    19.6 2263.55    23.6 2264.58    58.9 2268.14
    98.2 2264.72   156.8 2257.04   187.8 2251.11   251.3 2235.59   270.7 2224.99
   296.7 2226.35   310.9  2221.5   363.1 2209.81   404.9 2195.96   422.4 2187.68
     435 2183.99   476.5 2166.62   501.4 2164.89   558.4 2164.47  576.022162.732
     594 2160.89   622.4 2161.33  631.742162.851   661.6 2171.33   679.4 2172.63
   690.1 2175.16   739.9 2192.57   761.2 2192.16   850.2 2200.26  1146.4 2234.41
#Mann= 8 ,-1 , 0
       0      .1       0  271.67     .06       0  358.63      .1       0
   454.3     .05       0  554.78      .1       0  576.02    .045       0
  631.74      .1       0  810.91     .05       0
Bank Sta=576.02,631.74
XS Rating Curve= 0 ,0
Exp/Cntr=0.3,0.1

Type RM Length L Ch R = 1 ,83752   ,512.7,515.7,520.1
XS GIS Cut Line= 2
2148286.21514955390080.0814508942147327.88176438389731.123159304
#Sta/Elev= 30
       0 2354.09    52.6 2334.92   139.9 2315.34   202.8 2282.17   241.2 2273.29
   279.6 2261.74   293.5 2254.75     304 2254.29   321.5 2248.41   331.9 2238.79
   356.4 2237.76   388.3 2223.61   408.8 2209.07   412.3 2201.52   419.2 2168.74
   422.7 2165.19   440.2 2157.18  459.252156.111   471.6 2155.39  491.912157.954
   576.4 2161.13   618.3 2156.79   642.7 2166.05   653.2  2177.7   660.2 2182.33
   708.2 2196.25   750.9 2204.25     849 2216.91     943 2225.01  1019.9 2235.16
#Mann= 8 ,-1 , 0
       0      .1       0   293.5     .06       0  407.31      .1       0
  459.25    .045       0  491.91      .1       0  527.47      .1       0
  634.94     .05       0  996.45      .1       0
Bank Sta=459.25,491.91
XS Rating Curve= 0 ,0
Exp/Cntr=0.3,0.1

Type RM Length L Ch R = 1 ,83237   ,516.1,524.8,535.1
XS GIS Cut Line= 2
2148437.25684223389625.2204839742147532.74290322389227.651069149
#Sta/Elev= 30
       0 2314.51    92.4 2259.59   100.7 2252.01   115.1  2244.1   143.7 2233.22
   158.1 2222.32   179.5 2221.13     219 2204.89   290.7 2187.74   337.3 2169.95
   432.1 2162.65   448.4 2158.62   475.7 2157.34  480.932154.065   487.8 2152.05
  546.362153.027   573.8 2152.13     606 2155.48   642.5 2151.41   667.4 2159.39
   682.4 2161.13   692.1 2166.28   695.6 2172.34   709.3 2205.23   717.1 2218.74
   727.2 2227.27   760.1 2243.98   778.1 2249.59   806.7 2254.07     988 2272.64
#Mann= 7 ,-1 , 0
       0      .1       0   43.57      .1       0   96.24     .06       0
   256.3      .1       0  480.93    .045       0  546.36      .1       0
  686.82      .1       0
Bank Sta=480.93,546.36
XS Rating Curve= 0 ,0
Exp/Cntr=0.3,0.1

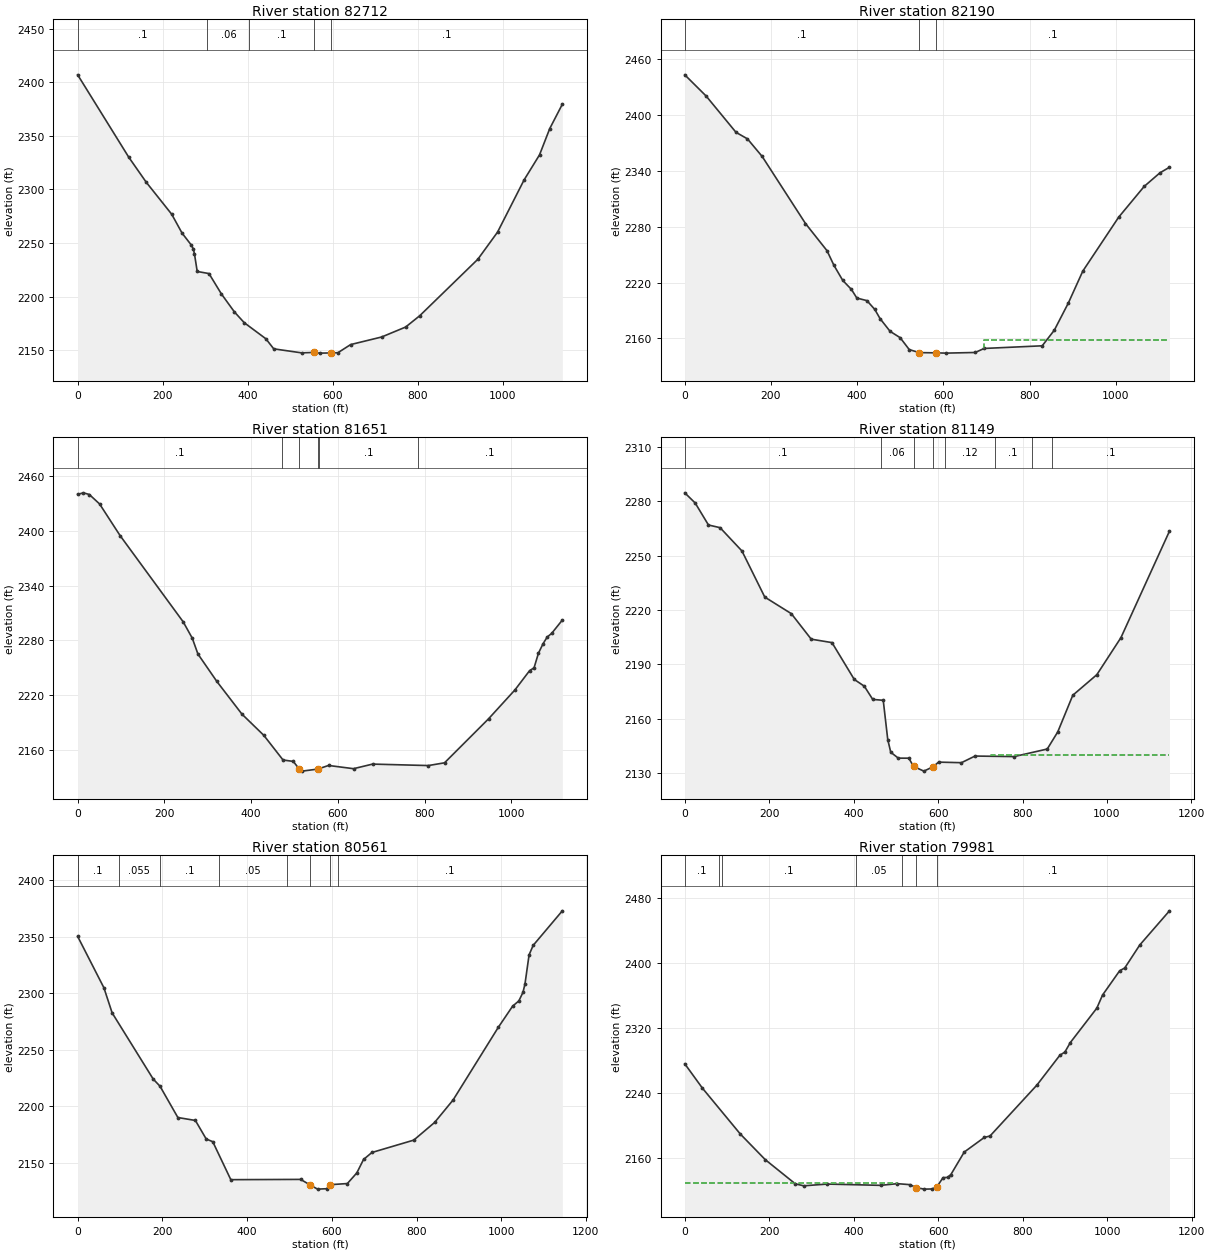
Type RM Length L Ch R = 1 ,82712   ,523.7,521.9,520.1
XS GIS Cut Line= 5
2148666.53197423389421.580143228 2148274.8441093389034.272518888
2148259.92058273389020.9575848882148244.99738422389007.642322809
2147861.33771847388613.696588397
#Sta/Elev= 30
       0 2407.13   120.4 2330.08   161.4 2306.78   221.4 2276.84   245.7 2259.25
   267.6 2248.02   272.2 2244.44   274.9 2239.86   281.4 2223.39   309.1 2221.43
   338.5 2202.28   369.1 2185.51   392.1 2175.51   442.9 2160.53   461.5 2151.09
   526.9 2147.36  556.562147.733   569.9 2147.09  597.39 2147.28   612.6 2147.49
   642.5 2155.08   715.5 2162.17   771.9 2171.46   804.9 2181.96   941.8 2234.78
   988.2 2260.14  1050.8 2309.01    1087 2332.32  1111.1 2356.93  1140.7 2379.64
#Mann= 5 ,-1 , 0
       0      .1       0  305.11     .06       0   404.3      .1       0
  556.56    .045       0  597.39      .1       0
Bank Sta=556.56,597.39
XS Rating Curve= 0 ,0
Exp/Cntr=0.3,0.1

Type RM Length L Ch R = 1 ,82190   ,545.5,538.5,528.6
XS GIS Cut Line= 2
2148961.64457297388919.4981421382148074.94588706388227.629447147
#Sta/Elev= 30
       0 2442.92    49.7 2420.09   118.8 2381.23   145.4 2374.21   179.6  2355.3
   280.1 2283.33   330.1 2254.14   346.1 2238.47   366.6 2222.26   386.8 2212.55
   399.3 2203.34   422.7 2200.57   440.9 2191.14   453.1 2181.31   476.4 2167.64
   499.8 2160.81   520.9 2148.03  544.312144.776  583.662144.554     605 2144.24
   673.9 2144.94   694.7 2149.26   829.4  2152.1   857.5 2168.86   890.2 2198.15
   923.6 2232.26  1006.8 2290.11    1066 2323.13  1102.5 2337.71  1124.7  2343.7
#Mann= 3 ,-1 , 0
       0      .1       0  544.31    .045       0  583.66      .1       0
#XS Ineff= 2 , 0
                          693.38         2158.04
Permanent Ineff=
       F       F
Bank Sta=544.31,583.66
XS Rating Curve= 0 ,0
Exp/Cntr=0.3,0.1

Type RM Length L Ch R = 1 ,81651   ,499.3,502.3,506.7
XS GIS Cut Line= 2
2149247.07149555388214.0979781452148163.73836039387940.486648723
#Sta/Elev= 30
       0    2440    13.3 2441.69    26.9 2439.85    50.6 2429.48    97.9 2394.77
   243.4 2300.23   264.3 2282.33   277.3 2265.01     321 2234.91   378.8 2199.13
   429.1 2175.94   473.5 2148.87   497.2 2147.32  511.162138.746   517.5 2136.67
  553.762138.916   578.4 2142.88     636 2139.34     680 2144.38   808.5 2142.77
   845.8 2145.78   947.3 2194.01  1008.2 2225.71    1042 2246.83  1052.2 2249.86
  1062.3  2265.9  1073.2 2276.51  1082.6 2283.67  1092.8 2287.64  1117.4 2302.25
#Mann= 6 ,-1 , 0
       0      .1       0  470.75     .06       0  511.16    .045       0
  553.76     .06       0  555.83      .1       0  784.48      .1       0
Bank Sta=511.16,553.76
XS Rating Curve= 0 ,0
Exp/Cntr=0.3,0.1

Type RM Length L Ch R = 1 ,81149   ,577.3,587.9,594.2
XS GIS Cut Line= 3
2149230.40486223387909.9312636412148884.57156439387632.153275892
 2148235.9603288387357.153497815
#Sta/Elev= 30
       0 2284.71    24.7 2279.08    56.1 2266.95    83.6 2265.48   135.4 2252.62
   189.5 2227.16   252.4 2218.01   299.5 2203.93   348.7 2202.03   401.5  2181.7
   425.3 2177.96   445.2 2170.68   470.1 2170.18   480.8  2148.5   487.9 2141.51
   505.8 2138.26   530.7 2138.24  541.882133.688   566.3 2131.09  587.762133.443
   601.1 2136.06   655.4 2135.75   687.5 2139.41   780.2 2139.12   858.6 2143.29
   883.5 2152.74   919.1 2172.97   976.1 2184.33  1033.2 2204.79  1148.1 2263.55
#Mann= 8 ,-1 , 0
       0      .1       0  464.51     .06       0  541.88    .045       0
  587.76     .06       0  616.35     .12       0  733.72      .1       0
  821.31     .12       0  869.09      .1       0
#XS Ineff= 1 ,-1
  726.05 1148.08 2140.07
Permanent Ineff=
       F
Bank Sta=541.88,587.76
XS Rating Curve= 0 ,0
Exp/Cntr=0.3,0.1

Type RM Length L Ch R = 1 ,80561   ,574.4,580.6,585.7
XS GIS Cut Line= 2
2149417.63250613387439.5247241412148575.01378456386665.353372231
#Sta/Elev= 30
       0 2350.16      62 2304.73    81.4 2282.55   178.4    2224   194.4 2217.71
   236.6 2190.01     278  2187.4   303.5 2171.02     319 2168.62   361.6 2135.05
   526.4 2135.29  547.542130.679   566.3 2126.69   587.8 2127.05  596.722130.646
   636.8 2131.62   659.1 2141.04     675 2152.93   694.7 2159.08   793.5 2170.02
   842.7 2185.63   886.4 2205.52   993.1 2269.74    1027 2288.51  1041.6  2293.1
  1051.3 2300.62  1056.1 2308.07  1065.8 2333.84  1075.5 2342.25  1144.3 2372.77
#Mann= 9 ,-1 , 0
       0      .1       0     .41      .1       0    96.7    .055       0
  193.79      .1       0  334.02     .05       0  494.61    .055       0
  547.54    .045       0  596.72     .06       0  614.37      .1       0
#XS Ineff= 2 , 0
          504.02 2134.19
Permanent Ineff=
       F       F
Bank Sta=547.54,596.72
XS Rating Curve= 0 ,0
Exp/Cntr=0.3,0.1

Type RM Length L Ch R = 1 ,79981   ,521.9,526.3,533.3
XS GIS Cut Line= 2
2149698.41344063 387112.743225472149057.04333231386161.480364233
#Sta/Elev= 30
       0 2276.21    41.8 2246.28   131.6 2189.89   190.4 2158.52   261.9 2128.67
   281.7 2126.37   337.2  2128.5   463.7 2126.92   503.3 2128.99   533.4 2127.75
  547.422124.225   566.5 2122.28   585.4 2122.48  596.592125.051   611.4 2136.42
     622 2136.67   629.9 2140.21   661.5 2167.82     709 2185.76   722.5 2187.53
   833.6 2250.13   887.9 2286.78   899.7 2290.63   912.6  2302.3   975.4 2344.63
   988.9  2360.7  1029.5 2390.59  1041.4  2393.9    1077 2422.17  1147.3 2464.15
#Mann= 7 ,-1 , 0
       0      .1       0   81.73    .055       0   87.61      .1       0
  406.45     .05       0  514.16     .06       0  547.42    .045       0
  596.59      .1       0
#XS Ineff= 2 , 0
          503.35 2129.61
Permanent Ineff=
       F       F
Bank Sta=547.42,596.59
XS Rating Curve= 0 ,0
Exp/Cntr=0.3,0.1

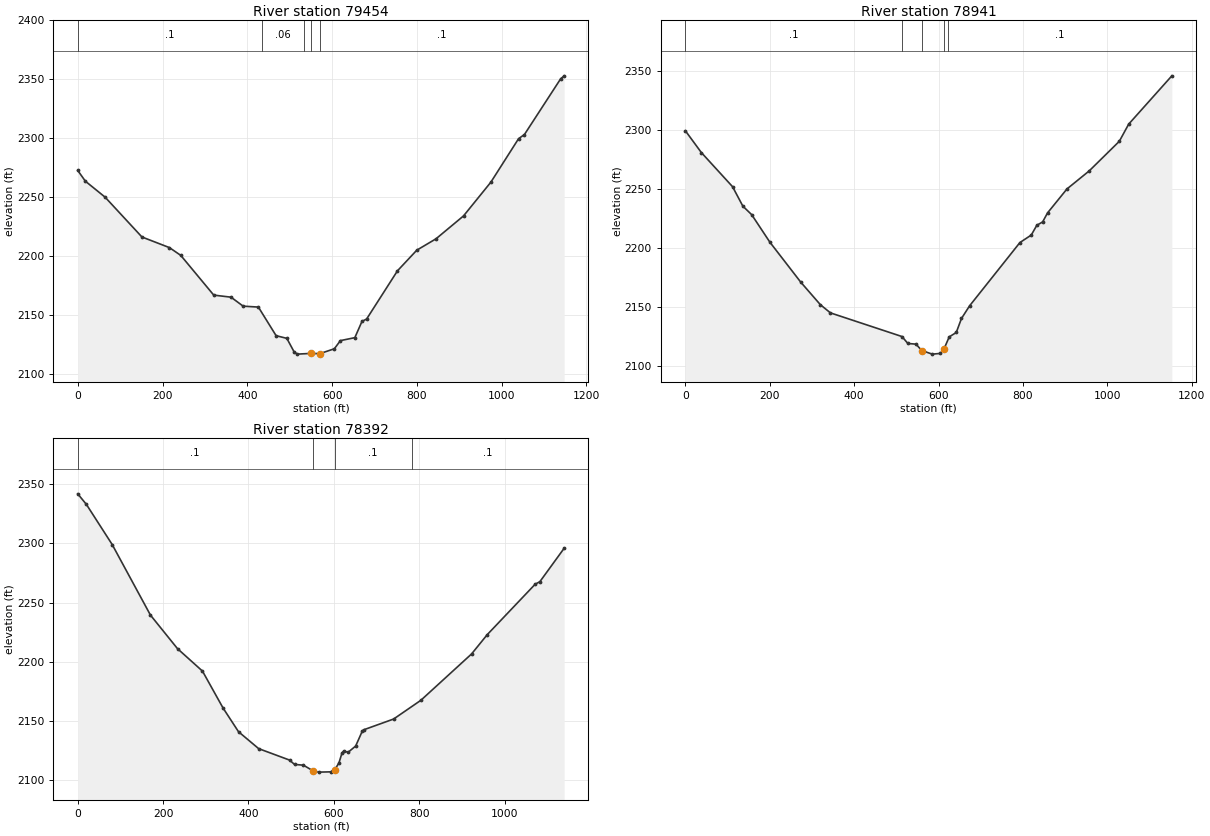
Type RM Length L Ch R = 1 ,79454   ,512.9,512.9,513.2
XS GIS Cut Line= 2
2150166.62543072386976.703143224 2149582.0540933385989.481692478
#Sta/Elev= 30
       0 2272.53      18 2263.41    64.5 2249.86   151.4 2216.02   216.3 2206.99
     243  2200.4   320.8 2166.64   361.5 2164.89   390.2 2157.25   426.1 2156.47
   467.9 2132.18   493.2 2129.91   509.9 2118.71   517.5 2116.51  551.052117.134
  571.082116.936   605.2 2121.05   619.6 2127.99   653.6  2130.5   670.4 2144.29
   681.4 2146.34   754.2  2187.3   799.7  2204.8     845 2214.46   909.9 2233.89
   974.5  2262.6  1039.8 2299.52  1053.6 2303.04    1139 2350.36  1147.3 2352.91
#Mann= 5 ,-1 , 0
       0      .1       0  434.12     .06       0  533.86      .1       0
  551.05    .045       0  571.08      .1       0
Bank Sta=551.05,571.08
XS Rating Curve= 0 ,0
Exp/Cntr=0.3,0.1

Type RM Length L Ch R = 1 ,78941   ,547.1,549.1,552.9
XS GIS Cut Line= 2
 2150618.6740673386721.8447290662150016.30814606385738.826681972
#Sta/Elev= 30
       0 2299.35    37.7 2280.93   111.7 2251.92   136.1 2235.41     157 2228.19
   200.2 2204.79   273.3 2170.89   319.8 2151.74   343.7 2144.78   513.1 2124.71
   527.3 2118.79   546.5 2118.25  560.072112.815     585 2109.76   604.3 2110.35
  612.482113.831   625.2  2124.4   641.9 2128.13   654.3 2140.05   673.5 2150.77
   792.8 2204.51   819.7 2210.87   832.8 2219.14   846.7 2222.05   858.2 2229.64
   904.3 2250.02   956.8 2265.27  1028.4 2290.49  1050.6 2305.05  1152.9 2346.07
#Mann= 5 ,-1 , 0
       0      .1       0  514.22     .06       0  560.07    .045       0
  612.48     .06       0  622.44      .1       0
Bank Sta=560.07,612.48
XS Rating Curve= 0 ,0
Exp/Cntr=0.3,0.1

Type RM Length L Ch R = 1 ,78392   ,531.1,532.1,534.9
XS GIS Cut Line= 2
2151076.75550023386570.9523143172150595.32011139385538.260810137
#Sta/Elev= 30
       0 2341.74    20.4 2332.75    80.7 2298.94   170.3  2239.4   233.7 2211.06
   292.2 2192.11   340.4 2160.96   376.6 2140.95   423.8 2126.68   496.1 2117.02
   507.8 2113.36   528.7 2112.71  550.052108.177   564.6 2106.85   592.8 2107.09
  602.442109.066   611.9 2114.67   619.2 2123.17   622.8 2124.53   633.7 2123.69
     651 2128.85   666.2 2141.17   669.8 2142.57   739.9 2151.66   803.8 2167.49
   922.6 2206.62   959.4 2222.95  1071.6 2265.48  1082.5 2267.58  1139.4 2295.79
#Mann= 4 ,-1 , 0
       0      .1       0  550.05    .045       0  602.44      .1       0
  781.84      .1       0
Bank Sta=550.05,602.44
XS Rating Curve= 0 ,0
Exp/Cntr=0.3,0.1