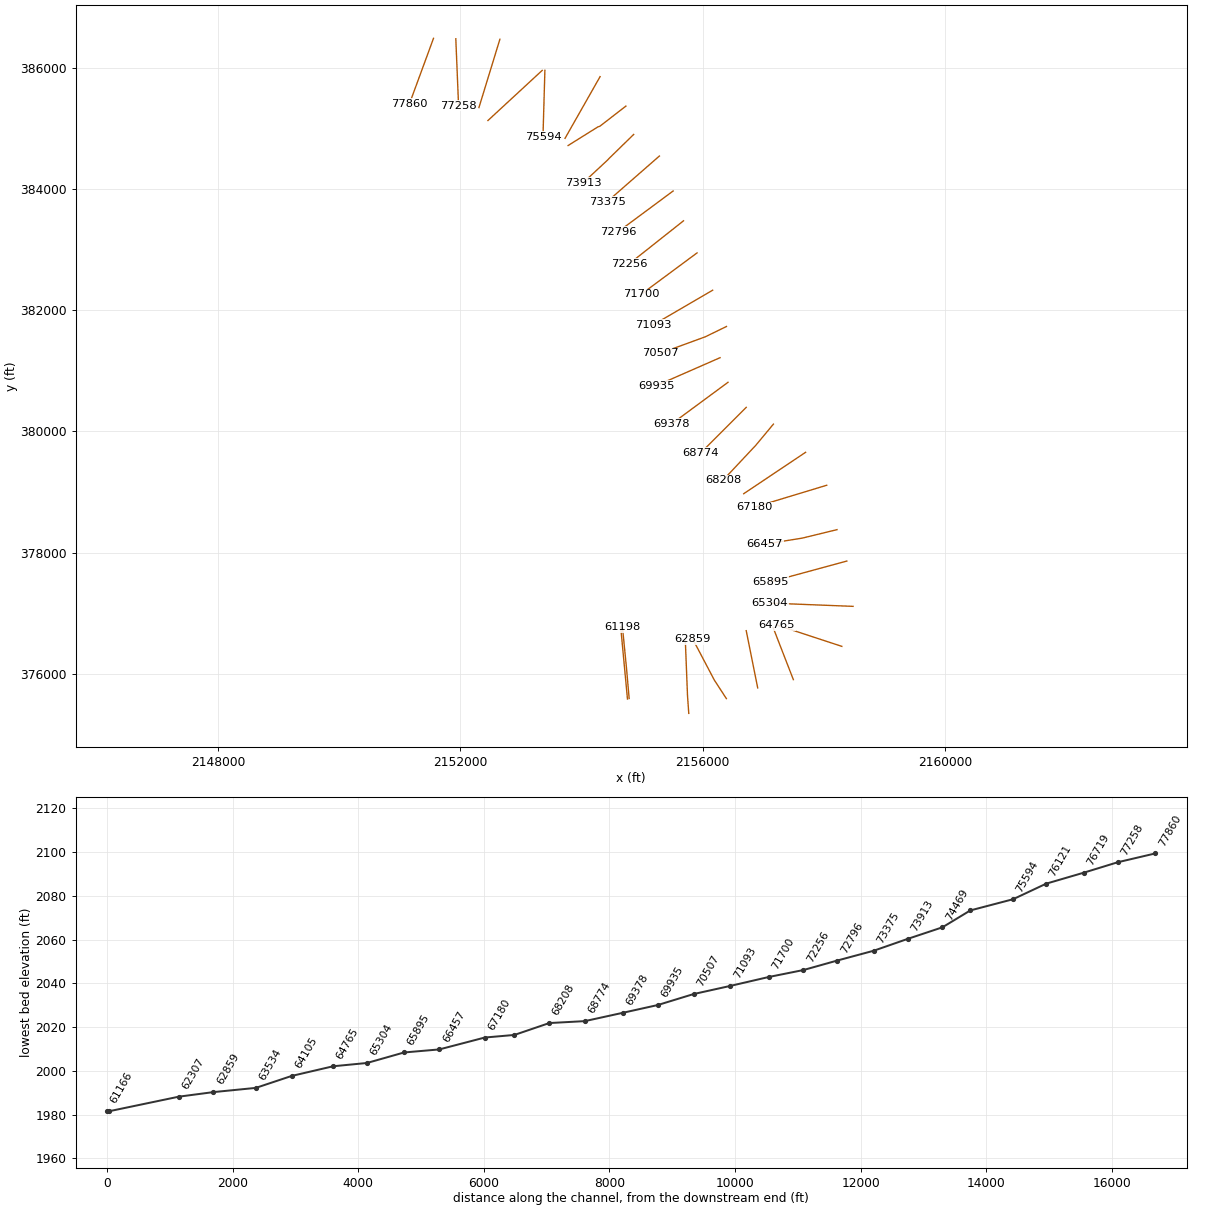
HEC-RAS study SPRINGCK.prj: SPRINGCK

--- SPRINGCK.g01 (geometry) --- (continued)

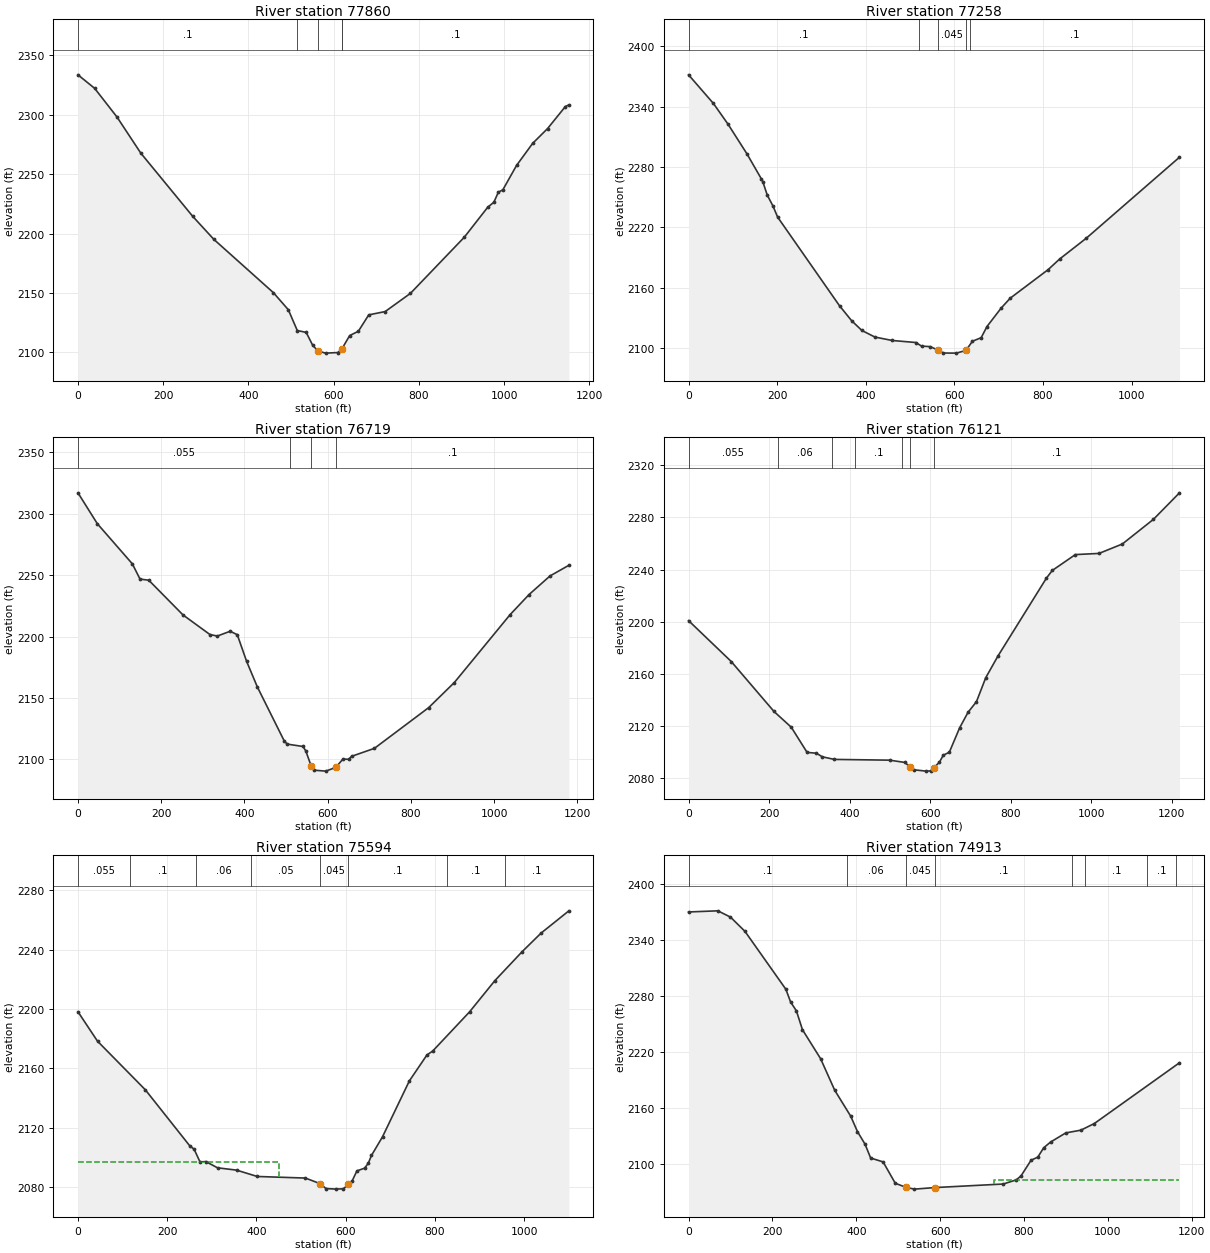
Type RM Length L Ch R = 1 ,77860   ,589.1,602.3,611.8
XS GIS Cut Line= 2
2151557.59476164386489.4728184792151160.29667172385408.249915317
#Sta/Elev= 30
       0 2333.67    39.2 2322.28    91.6 2298.13   147.5 2267.71   269.4 2214.46
   318.8 2195.14   458.6 2150.24   493.6 2135.87   514.6 2118.37   535.5 2116.81
   550.6 2106.06  562.862101.187     581 2099.34   609.4 2099.81   618.52102.422
   637.5 2114.11   657.9 2117.74   682.3 2131.56   720.8 2134.33   780.2 2149.69
   906.4 2196.89   961.6 2222.24   975.9 2226.39   986.4 2234.86   996.9 2236.83
  1029.1 2257.37  1066.9 2275.96  1101.8 2288.39  1143.7 2306.98  1151.9 2308.35
#Mann= 5 ,-1 , 0
       0      .1       0  514.17     .06       0  562.86    .045       0
   618.5     .06       0  618.68      .1       0
Bank Sta=562.86,618.5
XS Rating Curve= 0 ,0
Exp/Cntr=0.3,0.1

Type RM Length L Ch R = 1 ,77258   ,547,538.7,527
XS GIS Cut Line= 2
2151925.65012789386482.5282785592151971.48369764385375.583970144
#Sta/Elev= 30
       0  2371.5    56.1 2343.07      89 2322.56   131.7 2293.11   164.5 2268.07
   167.8  2265.1   177.6 2252.11   190.8 2241.02   200.9 2230.35   340.7 2142.25
     368 2127.46   391.1 2117.77   420.6 2111.22   459.5 2107.84   513.1 2105.81
   525.7 2102.25   545.4 2101.74  563.782098.114     575 2095.39   604.5 2095.28
  626.062097.973   640.6 2107.06   660.3  2110.6   673.5  2121.7   705.4 2139.96
     726 2149.84   811.4 2178.13   837.6 2188.74   897.8 2209.41  1107.9 2289.74
#Mann= 5 ,-1 , 0
       0      .1       0  520.96     .06       0  563.78    .045       0
  626.06     .06       0  634.34      .1       0
Bank Sta=563.78,626.06
XS Rating Curve= 0 ,0
Exp/Cntr=0.3,0.1

Type RM Length L Ch R = 1 ,76719   ,611.6,597.8,581.6
XS GIS Cut Line= 2
2152653.42819989386474.1949618912152307.59457397385346.417361811
#Sta/Elev= 30
       0 2316.95    46.5 2291.84   130.7 2259.15   149.1 2246.76   170.1 2245.87
   252.4 2217.61   317.1 2201.66   334.8 2200.43   365.7 2204.32   382.8 2201.54
   405.1 2179.97   430.9 2159.11   495.7 2115.04   502.9  2112.5   540.7 2110.59
   547.5 2106.93  560.32 2094.78   568.1 2091.28   595.6 2090.53   619.32093.537
   636.8 2100.38   650.5 2100.14   657.3 2102.55   712.3 2109.06   842.7  2142.2
   904.4 2162.63  1038.3 2217.82    1084 2234.23  1134.3 2249.34  1179.6    2258
#Mann= 4 ,-1 , 0
       0    .055       0  510.08     .06       0  560.32    .045       0
   619.3      .1       0
Bank Sta=560.32,619.3
XS Rating Curve= 0 ,0
Exp/Cntr=0.3,0.1

Type RM Length L Ch R = 1 ,76121   ,498.3,527.6,545.6
XS GIS Cut Line= 2
2153352.03900738385960.306225896 2152456.2058253  385132.5283539
#Sta/Elev= 30
       0 2200.88     106 2169.55   212.3 2131.23   255.2 2119.17   294.5 2099.87
   317.8 2099.25   332.1 2096.51   362.3  2094.5   499.3 2093.93   536.5 2092.23
  550.842088.813     559 2086.58   589.9 2085.52   601.5 2085.68  609.862088.263
   623.2 2092.35   632.9 2097.72   647.9 2100.02   673.4 2118.65   694.3 2130.58
   715.3 2138.77   738.4 2157.15   768.6 2173.71   889.1 2233.45   903.6 2239.32
     961  2251.5  1019.7 2252.39  1077.7 2259.61    1155 2278.53  1219.7 2298.84
#Mann= 7 ,-1 , 0
       0    .055       0  221.83     .06       0  356.38     .06       0
  413.25      .1       0   530.4      .1       0  550.84    .045       0
  609.86      .1       0
Bank Sta=550.84,609.86
XS Rating Curve= 0 ,0
Exp/Cntr=0.3,0.1

Type RM Length L Ch R = 1 ,75594   ,692.1,681.1,657.7
XS GIS Cut Line= 2
 2153396.4834723385961.6950026452153364.53931047384861.694906056
#Sta/Elev= 30
       0 2198.14    43.8 2178.29     151 2145.47   250.6 2107.64   260.4 2105.35
   273.6 2096.77   286.7    2097   312.9  2092.8   355.6 2091.23     402 2086.95
   509.9 2085.88  543.682082.006   555.8 2078.81   578.8 2078.41   595.2 2078.68
  605.912081.571   614.9 2084.12   625.3 2090.71   642.4 2092.55   650.8 2095.83
     658 2101.16   682.7 2113.73   742.9 2151.47   782.3 2168.97   795.4 2171.67
   877.8 2198.05   934.6 2219.16   995.6 2238.66  1038.3 2251.27  1100.5 2266.27
#Mann= 8 ,-1 , 0
       0    .055       0  115.88      .1       0  265.04     .06       0
  388.05     .05       0  543.68    .045       0  605.91      .1       0
  827.49      .1       0  956.66      .1       0
#XS Ineff= 2 , 0
          451.61 2096.48
Permanent Ineff=
       F       F
Bank Sta=543.68,605.91
XS Rating Curve= 0 ,0
Exp/Cntr=0.3,0.1

Type RM Length L Ch R = 1 ,74913   ,460.6,444.1,418.1
XS GIS Cut Line= 2
2154307.50658464385857.2683742342153729.33680922384839.092917144
#Sta/Elev= 30
       0 2370.46    69.9 2371.67     100 2364.92   134.5 2349.67   232.1 2287.56
   243.4 2273.91   257.2 2264.42   271.6 2244.26     315 2213.07   348.6 2179.29
   386.8 2151.45   402.9 2134.91     421 2121.41   434.3 2106.63     464 2102.49
     493  2079.6   518.22075.245   538.7 2073.29  587.082074.946   750.5 2078.76
   781.8 2083.24   793.1 2087.58   816.9 2104.28   832.9 2107.56   847.1 2117.67
   863.6 2123.81   899.7 2133.57   935.8 2136.52   967.8 2143.63  1170.9 2208.78
#Mann= 8 ,-1 , 0
       0      .1       0  377.34     .06       0   518.2    .045       0
  587.08      .1       0  915.71      .1       0     946      .1       0
 1094.28      .1       0 1163.65      .1       0
#XS Ineff= 2 , 0
                          729.12         2083.12
Permanent Ineff=
       F       F
Bank Sta=518.2,587.08
XS Rating Curve= 0 ,0
Exp/Cntr=0.3,0.1

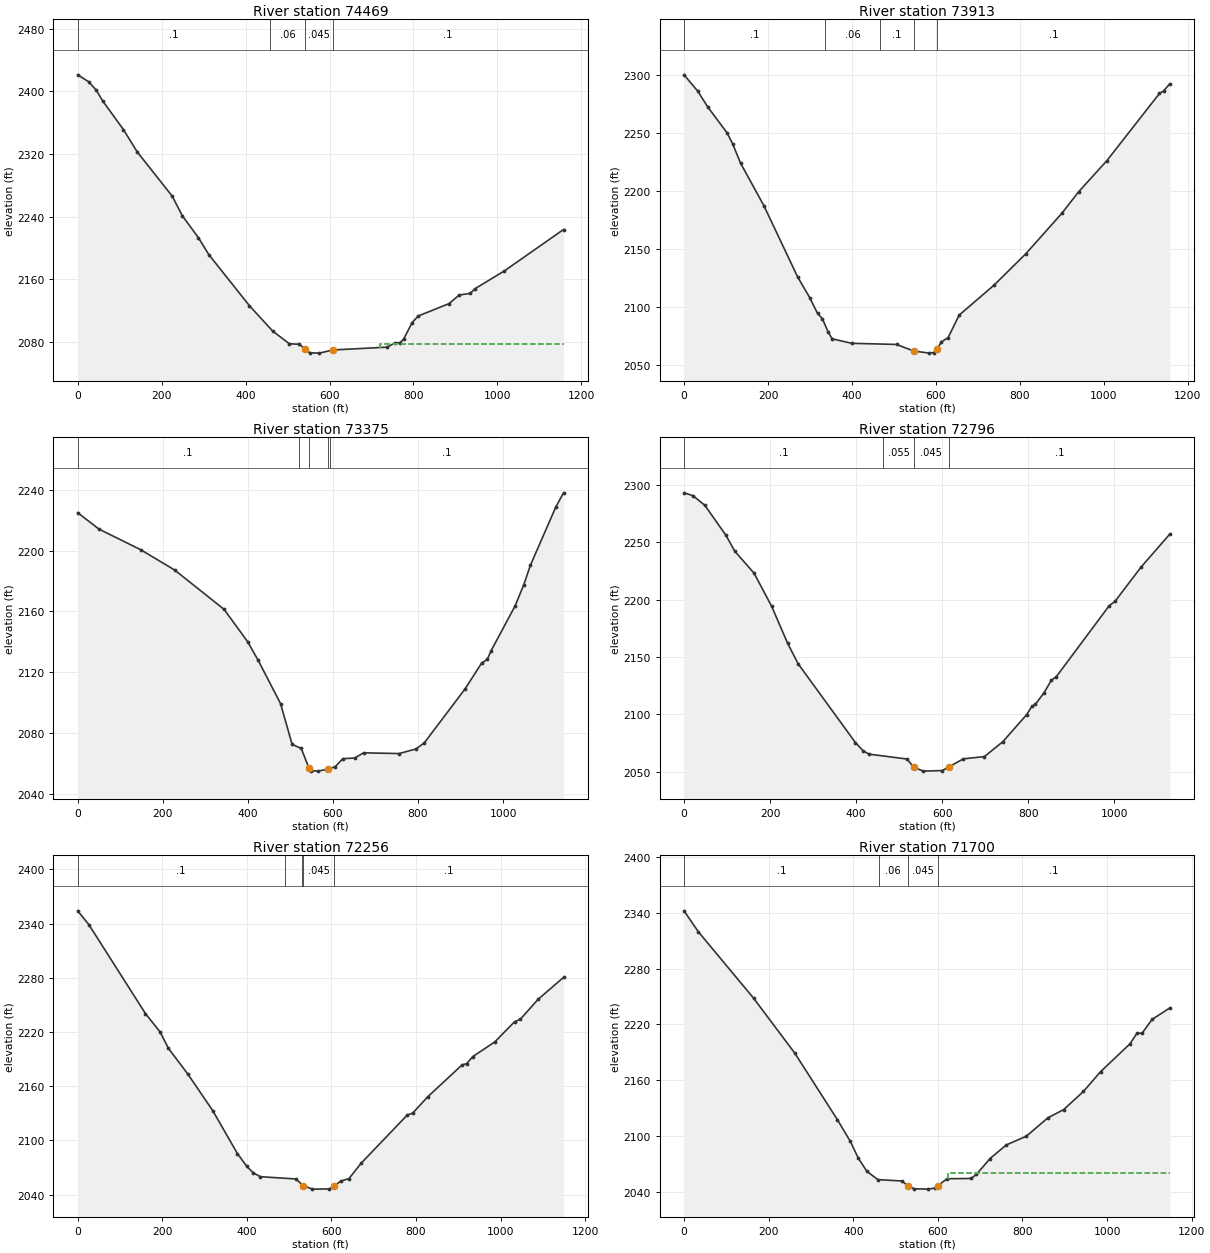
Type RM Length L Ch R = 1 ,74469   ,545.2,555.6,563.7
XS GIS Cut Line= 5
2154733.85481331385370.9386382252154305.95540664385039.677817807
2154287.24415797385032.6158240592154268.53323738385025.551861808
2153779.81702322 384720.02852273
#Sta/Elev= 30
       0 2421.01    26.2 2412.14    44.4 2401.24    59.4 2387.77     109 2351.06
   141.7 2322.64   225.4  2265.9   249.3 2240.96   287.6 2213.02   312.4 2191.39
   408.8 2126.35   464.4 2093.83   504.2 2077.56   528.2 2076.86  541.142070.963
   553.3    2066   575.8 2065.58  607.342069.593   737.1 2073.21   756.1 2078.63
     768 2078.98   776.5 2083.45   796.6  2104.4   811.3 2113.02   884.7 2128.81
   909.2 2139.84   935.1 2141.85   946.7 2147.85  1016.4 2170.52  1157.5 2223.47
#Mann= 4 ,-1 , 0
       0      .1       0  459.15     .06       0  541.14    .045       0
  607.34      .1       0
#XS Ineff= 2 , 0
                          720.71         2076.98
Permanent Ineff=
       F       F
Bank Sta=541.14,607.34
XS Rating Curve= 0 ,0
Exp/Cntr=0.3,0.1

Type RM Length L Ch R = 1 ,73913   ,538.5,537.6,532.6
XS GIS Cut Line= 5
2154862.22594763384902.7784853132154459.11848614384509.764835641
2154445.46168931384495.1533163042154431.86165088384480.489303648
2154025.89034997384103.245635554
#Sta/Elev= 30
       0 2300.54    32.6 2286.45      57 2272.56   102.2 2250.58   115.6 2241.12
   134.6 2224.33   190.3 2187.49   270.6 2126.04   299.4 2108.19   317.9 2094.62
   329.5 2089.97   343.4 2078.42   352.7 2072.63   399.1 2068.75   506.1 2067.77
  546.622062.135   584.5 2060.27   594.6  2060.8  602.992063.906   613.1 2070.02
   628.9 2073.62   655.4 2093.11     738 2118.83   814.6 2146.24   900.5 2181.24
   939.9 2199.56  1007.3 2226.48  1132.5 2284.49  1142.2 2286.64  1157.2 2292.82
#Mann= 5 ,-1 , 0
       0      .1       0  336.26     .06       0   467.9      .1       0
  546.62    .045       0  602.99      .1       0
Bank Sta=546.62,602.99
XS Rating Curve= 0 ,0
Exp/Cntr=0.3,0.1

Type RM Length L Ch R = 1 ,73375   ,576.7,579.3,583.8
XS GIS Cut Line= 2
2155287.09616089 384546.724407392154427.12543988383795.493298307
#Sta/Elev= 30
       0 2224.93    50.2 2214.12   147.9 2200.61   227.9 2187.22   343.9 2161.39
   399.3 2140.12   424.2  2127.8   476.7 2099.35     504 2072.51   525.5 2069.81
  543.132057.174   548.7  2055.2   563.8 2054.89  588.942056.171   605.3 2057.86
   623.2 2063.08   651.1 2063.52     672 2066.94   755.7 2066.45   795.2 2069.49
   814.4 2073.42   910.2 2108.87   949.4 2125.97   962.8  2128.4   971.2 2133.89
  1027.9  2163.5  1048.7 2177.66  1063.9 2190.26  1123.7 2228.63  1141.9 2238.02
#Mann= 5 ,-1 , 0
       0      .1       0  519.58     .06       0  543.13    .045       0
  588.94     .06       0  591.97      .1       0
Bank Sta=543.13,588.94
XS Rating Curve= 0 ,0
Exp/Cntr=0.3,0.1

Type RM Length L Ch R = 1 ,72796   ,538.1,540.6,537.6
XS GIS Cut Line= 2
2155513.24433064383968.9683450612154606.47416255383296.867327064
#Sta/Elev= 30
       0 2293.32    20.7 2290.83    48.5 2282.36    97.5 2256.17   117.9 2242.34
   162.8 2223.15   203.7 2194.13   240.4 2162.23   264.9  2144.2   398.3 2075.29
     416  2068.2   429.5 2065.25   518.1 2060.99  533.272053.953   555.5 2050.42
     600 2050.91  615.062053.995   648.8 2061.13   697.8 2063.11   740.8 2076.15
   795.8 2099.63   808.1  2106.9   816.2 2108.71   836.7    2119   853.3  2129.7
   865.1 2132.94   987.8  2194.8  1001.1 2198.52  1062.1 2228.62  1128.7 2257.34
#Mann= 4 ,-1 , 0
       0      .1       0  463.04    .055       0  533.27    .045       0
  615.06      .1       0
Bank Sta=533.27,615.06
XS Rating Curve= 0 ,0
Exp/Cntr=0.3,0.1

Type RM Length L Ch R = 1 ,72256   ,557.3,555.2,555.1
XS GIS Cut Line= 2
2155685.23644072383477.0693944842154784.40556522 382763.94418031
#Sta/Elev= 30
       0 2354.05    26.6 2338.63   160.2 2240.37   194.6 2220.15   214.6 2201.83
   260.7 2173.24   319.3 2132.95   377.8 2085.33   400.1 2071.17   415.5 2063.97
   432.2 2059.84   515.9 2057.32  533.552049.848   555.2 2046.07   595.4  2046.3
  605.562049.225     622 2054.99   641.5  2057.7   670.7 2074.95   779.5 2128.13
   792.1 2130.17   827.5 2148.13     909 2183.57   919.9 2184.96   934.4  2192.8
   986.4 2208.97  1033.1  2231.3  1046.8 2234.09    1089 2256.21  1148.9 2280.37
#Mann= 5 ,-1 , 0
       0      .1       0  489.33     .06       0  530.03      .1       0
  533.55    .045       0  605.56      .1       0
Bank Sta=533.55,605.56
XS Rating Curve= 0 ,0
Exp/Cntr=0.3,0.1

Type RM Length L Ch R = 1 ,71700   ,612,607.3,601.7
XS GIS Cut Line= 2
2155908.06539139382946.8322659732154985.21848381382263.517359644
#Sta/Elev= 30
       0  2342.1    33.5 2319.77   164.2 2248.26   261.8 2189.08   362.7 2117.37
   392.8 2094.41   411.9 2076.18   432.3 2061.93   458.1 2053.12   515.2  2051.6
  528.21 2046.63   543.8 2043.24   576.1 2042.87   592.6 2043.95  600.392046.677
   621.4 2054.03   678.5 2054.33   691.1 2058.71   723.4 2075.78   761.4 2090.29
   809.2  2099.8   859.9 2119.49   897.5 2128.43   943.9 2147.85   984.7 2169.19
  1054.1 2199.15  1070.4 2210.36  1082.8 2210.62  1106.2 2225.29  1148.3 2237.74
#Mann= 4 ,-1 , 0
       0      .1       0  460.96     .06       0  528.21    .045       0
  600.39      .1       0
#XS Ineff= 2 , 0
                          624.79         2060.24
Permanent Ineff=
       F       F
Bank Sta=528.21,600.39
XS Rating Curve= 0 ,0
Exp/Cntr=0.3,0.1

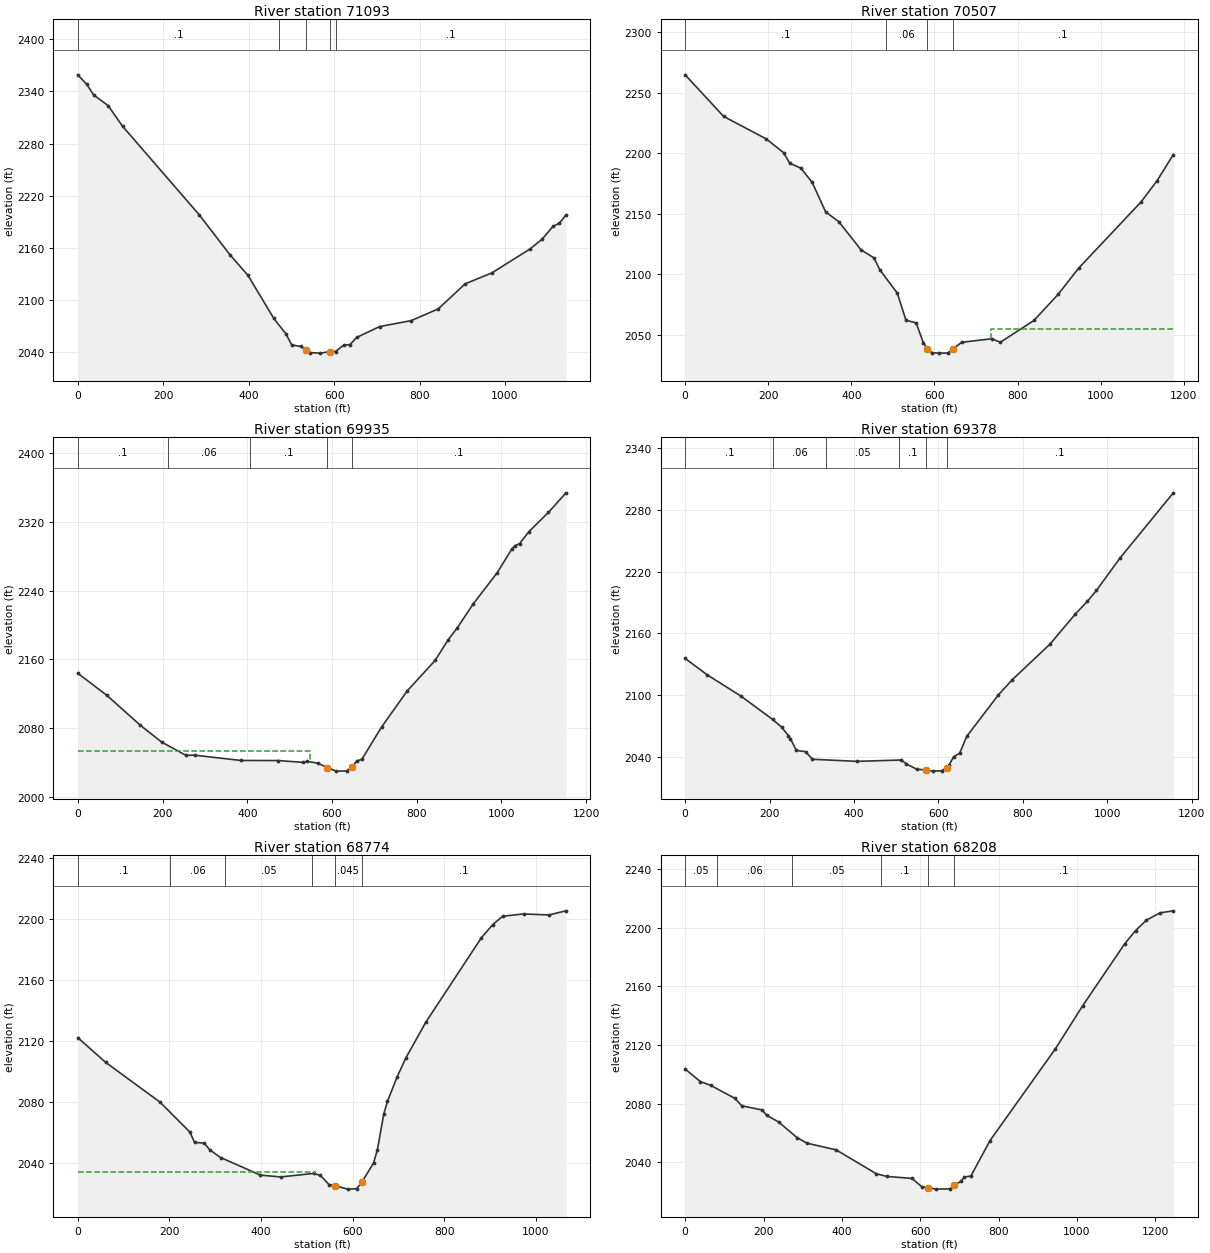
Type RM Length L Ch R = 1 ,71093   ,589.7,586.4,580.5
XS GIS Cut Line= 2
2156166.07274939382331.1829067322155178.76665314381755.800855398
#Sta/Elev= 30
       0 2359.11    20.7 2348.15    37.4 2335.83    71.1  2323.6   104.6 2300.02
   284.3 2197.93   356.4 2151.89   398.2 2128.37   458.9 2078.71   487.1 2061.02
   500.7 2048.26   522.1 2046.49  533.712042.353   542.5 2039.45   567.7 2038.83
  589.372040.507   603.2 2040.68   622.2    2048   637.3 2048.67   652.6 2056.87
   706.8 2069.44   780.4 2076.24   843.6 2089.69     907 2118.65   969.3 2131.16
  1058.9 2158.83  1086.6 2169.85  1112.3 2184.62  1127.3 2188.32  1142.7 2197.91
#Mann= 5 ,-1 , 0
       0      .1       0  471.35     .06       0  533.71    .045       0
  589.37     .06       0  603.72      .1       0
Bank Sta=533.71,589.37
XS Rating Curve= 0 ,0
Exp/Cntr=0.3,0.1

Type RM Length L Ch R = 1 ,70507   ,569.2,571.2,570.2
XS GIS Cut Line= 3
2156394.08902563381732.3379758152156046.86662297381562.893432811
2155306.38647664381291.956638724
#Sta/Elev= 30
       0 2264.72    92.6 2230.41   194.8 2211.92     237 2200.49   251.7 2191.79
   278.7 2187.69   305.7 2175.95   338.4 2151.47   369.5 2143.68   423.1 2120.38
   454.6 2113.66   468.6 2103.78   510.5 2084.66   531.4 2062.27   555.9 2060.03
   573.3 2043.63  582.672038.758   594.3 2035.36   611.9  2035.1   632.7 2035.16
  644.83 2038.59   665.4 2044.02   737.5 2046.96   758.5 2044.06   839.4 2062.04
   898.2  2083.8   946.8 2105.12  1097.4  2159.9  1136.1 2177.52  1174.9  2198.9
#Mann= 4 ,-1 , 0
       0      .1       0  483.89     .06       0  582.67    .045       0
  644.83      .1       0
#XS Ineff= 2 , 0
                          736.16         2054.65
Permanent Ineff=
       F       F
Bank Sta=582.67,644.83
XS Rating Curve= 0 ,0
Exp/Cntr=0.3,0.1

Type RM Length L Ch R = 1 ,69935   ,551.8,557,562.5
XS GIS Cut Line= 2
2156288.53346246381217.060134977 2155232.9778308 380754.56007573
#Sta/Elev= 30
       0 2143.92    68.7 2118.18   147.8 2083.34   197.7 2063.94   254.9 2048.51
   276.5  2048.6   385.7 2042.45   473.5 2042.39   530.8 2040.27   541.5 2041.34
   566.3 2039.33  589.31 2034.24   609.6 2030.08   634.7 2030.26  648.242034.985
   658.4 2041.98   670.5 2043.72     717 2081.36   777.9 2123.58   843.5 2158.86
   874.6 2183.13   896.1 2196.92   933.4 2224.64   989.7 2260.66  1025.1 2288.84
    1032 2292.23    1043 2294.78  1064.4 2308.41  1111.1 2331.11  1152.4 2353.85
#Mann= 5 ,-1 , 0
       0      .1       0  212.73     .06       0  406.14      .1       0
  589.31    .045       0  648.24      .1       0
#XS Ineff= 2 , 0
          549.22 2053.92
Permanent Ineff=
       F       F
Bank Sta=589.31,648.24
XS Rating Curve= 0 ,0
Exp/Cntr=0.3,0.1

Type RM Length L Ch R = 1 ,69378   ,599.3,604.3,607.9
XS GIS Cut Line= 2
2156419.12506481380810.4946751452155488.53342205380124.004578307
#Sta/Elev= 30
       0 2135.72    52.2 2119.87     132 2099.28     207 2076.67   228.3 2069.24
   244.6 2060.93   249.3 2058.09   263.3 2046.58   285.3 2045.42   301.6 2038.01
   407.6    2036     512 2037.31   523.8 2033.65   548.6 2028.32  570.012027.722
     587 2026.53   607.4 2026.83  619.152029.514   624.7 2032.11   635.9 2040.37
   650.5 2044.04   666.9 2060.16   741.9 2100.37   775.1 2115.23     864 2149.52
   924.4  2178.8   953.1 2191.22   974.3 2201.67  1030.5 2233.23  1156.4 2296.25
#Mann= 6 ,-1 , 0
       0      .1       0   209.2     .06       0   333.4     .05       0
  505.94      .1       0  570.01    .045       0  619.15      .1       0
#XS Ineff= 2 , 0
          504.77 2036.82
Permanent Ineff=
       F       F
Bank Sta=570.01,619.15
XS Rating Curve= 0 ,0
Exp/Cntr=0.3,0.1

Type RM Length L Ch R = 1 ,68774   ,564.3,566,565.6
XS GIS Cut Line= 2
2156720.00963363380396.8170248122155966.42682321 379643.21748215
#Sta/Elev= 30
       0 2122.04    61.1 2105.76   179.5 2079.76   244.5 2060.19   254.9 2053.39
   275.8  2052.9   288.4 2048.41   311.6 2043.46   398.7 2031.92   442.8 2030.73
   514.7 2033.01   529.7 2031.73   548.3 2025.73  560.742025.049   588.9 2022.73
   608.6    2023  619.772027.112   645.7 2039.94   653.9 2048.36   667.8 2071.78
     676 2080.32   696.7 2096.03   716.5 2108.96   759.5 2132.06   881.2 2187.61
   905.5 2196.07   927.6 2201.65     973 2203.16  1028.6  2202.5  1065.7  2205.2
#Mann= 6 ,-1 , 0
       0      .1       0  201.58     .06       0   322.4     .05       0
  510.34      .1       0  560.74    .045       0  619.77      .1       0
#XS Ineff= 2 , 0
          517.49 2034.23
Permanent Ineff=
       F       F
Bank Sta=560.74,619.77
XS Rating Curve= 0 ,0
Exp/Cntr=0.3,0.1

Type RM Length L Ch R = 1 ,68208   ,557.5,555.5,546.9
XS GIS Cut Line= 3
2157169.20460139380120.2342446452156878.92696673379771.623393312
2156336.86604297379193.811884895
#Sta/Elev= 30
       0 2103.66      39 2095.09    64.7 2092.63   126.2 2083.79   144.6 2078.62
   195.8 2075.81   208.6 2072.06   238.5 2067.63   285.3 2056.97   310.9 2053.15
   385.5 2048.58   488.1 2032.29   514.9 2030.51     579 2029.15   603.9 2023.48
  620.612022.745   640.8 2021.85   675.9 2022.04  686.082024.444   703.8 2027.12
   712.8 2030.09   729.3 2030.81     778 2054.91   945.1 2117.53  1014.7 2146.85
  1121.5  2188.9  1149.6 2198.01  1177.2 2205.14    1212 2210.09  1245.9 2211.47
#Mann= 6 ,-1 , 0
       0     .05       0   81.16     .06       0  273.94     .05       0
  500.42      .1       0  620.61    .045       0  686.08      .1       0
Bank Sta=620.61,686.08
XS Rating Curve= 0 ,0
Exp/Cntr=0.3,0.1

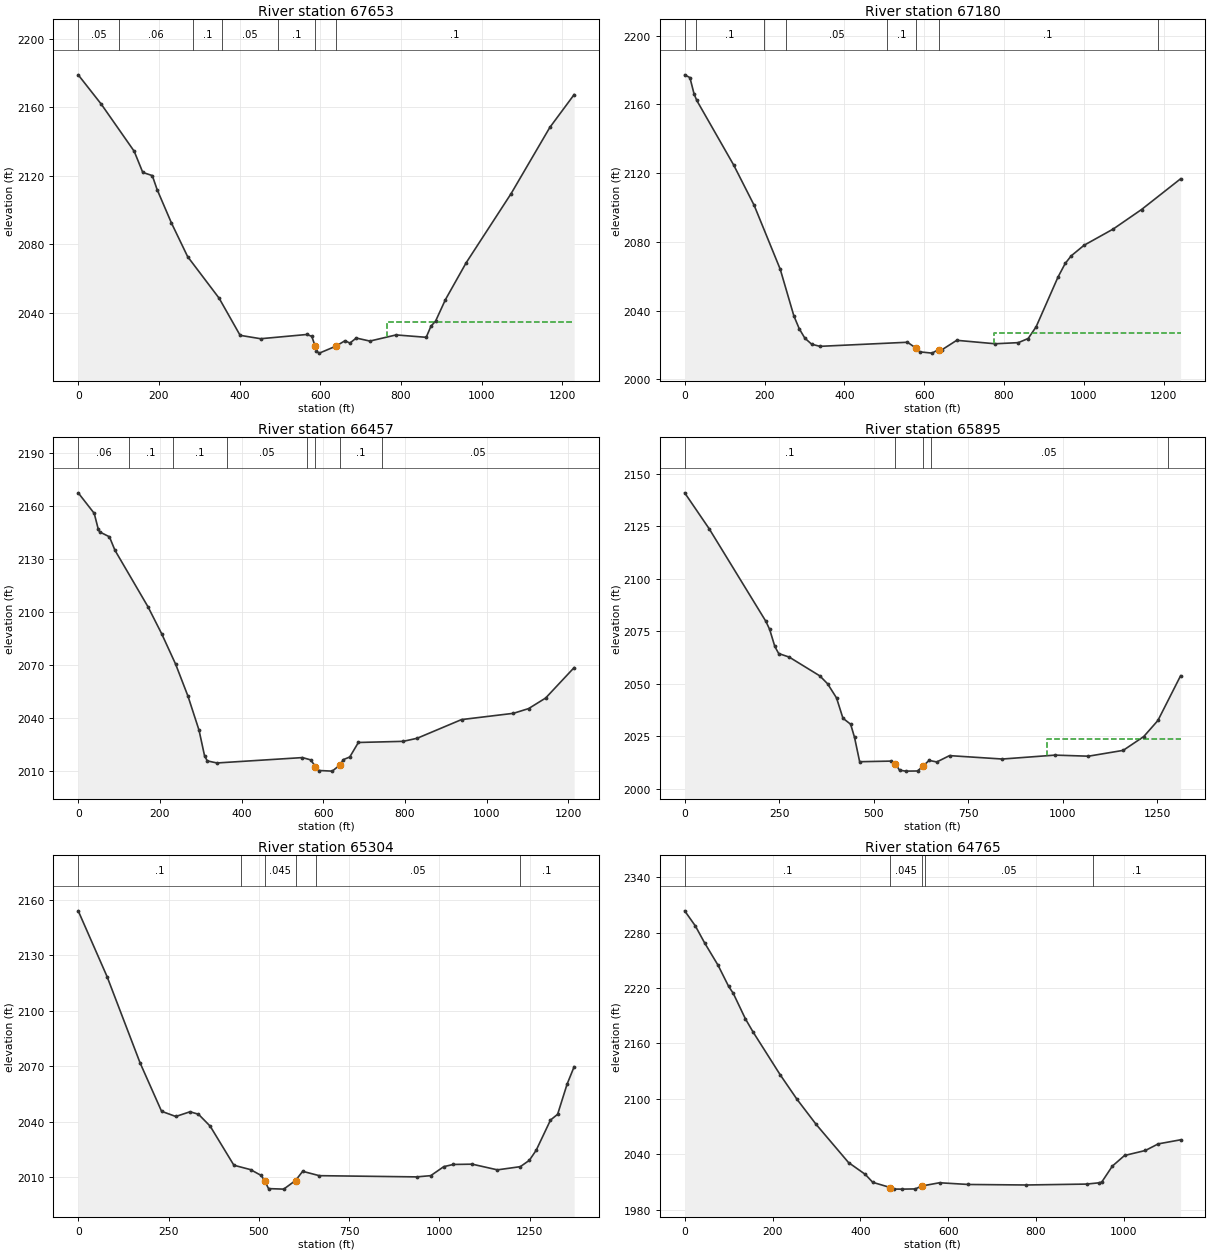
Type RM Length L Ch R = 1 ,67653   ,481.6,472.7,465.1
XS GIS Cut Line= 2
2157700.51095347379655.2108964772156678.92703864  378971.6233529
#Sta/Elev= 30
       0 2178.94    57.5 2161.69   138.8 2134.28     160 2121.95   183.6  2120.1
   195.5 2111.97   231.1 2092.41   271.2 2072.78   349.3 2048.47   401.3 2026.81
   452.2 2024.83   566.8 2027.31   578.9 2026.22  586.74 2020.82   590.5 2017.54
   597.6 2016.42  639.182020.537   661.4 2023.69   673.3 2022.28   689.1 2025.23
   722.9 2023.46   787.8 2027.05   862.5 2025.66   874.3 2032.16   885.7 2035.09
   910.1 2047.64   961.4 2069.13    1073  2109.6  1168.8 2148.19  1229.2 2167.41
#Mann= 7 ,-1 , 0
       0     .05       0  102.15     .06       0  284.27      .1       0
  356.27     .05       0   495.8      .1       0  586.74    .045       0
  639.18      .1       0
#XS Ineff= 2 , 0
                          764.57          2034.6
Permanent Ineff=
       F       F
Bank Sta=586.74,639.18
XS Rating Curve= 0 ,0
Exp/Cntr=0.3,0.1

Type RM Length L Ch R = 1 ,67180   ,725.2,723.1,718.1
XS GIS Cut Line= 2
2158049.13624047379111.2766169012156860.12877597378750.660868317
#Sta/Elev= 30
       0 2177.17    13.1 2175.56    23.4 2166.16    30.2  2162.3   122.8 2124.67
     174 2101.27   239.4 2064.04   273.6 2036.87   287.1 2029.38   301.1 2023.93
   318.2 2020.41   338.8 2019.18   558.2 2021.56  580.272018.013   589.1 2015.97
   619.9 2015.23     6362017.333   643.9 2017.08   681.6 2022.69   777.6 2020.68
   835.9 2021.33   860.6 2023.74   880.5 2030.55   935.3 2059.48   953.3 2067.39
   968.4 2071.84  1000.5 2077.98  1073.7 2087.45  1144.5 2098.78  1242.5 2116.68
#Mann= 8 ,-1 , 0
       0     .06       0   27.13      .1       0  197.58      .1       0
  252.76     .05       0  507.43      .1       0  580.27    .045       0
     636      .1       0 1185.33     .05       0
#XS Ineff= 1 ,-1
  774.87 1242.49 2027.14
Permanent Ineff=
       F
Bank Sta=580.27,636
XS Rating Curve= 0 ,0
Exp/Cntr=0.3,0.1

Type RM Length L Ch R = 1 ,66457   ,560.9,561.8,565.5
XS GIS Cut Line= 5
2158219.06897147378378.2679123132157648.52352464378239.022455901
2157628.78471898378235.8003494742157609.04591331378232.578243062
 2157029.3758128378139.242799804
#Sta/Elev= 30
       0 2167.37    39.2 2155.74    49.3 2146.62    52.7 2145.23    76.4 2142.48
    89.9 2134.88   170.9 2102.83   204.7 2087.42   238.5 2070.38   268.9 2052.17
   295.9 2032.94   309.4 2018.45   316.1  2015.6   339.8 2014.43   549.2 2017.48
   569.4 2016.16  580.772012.412   589.6 2010.16   622.1 2009.81  640.412013.225
   649.5 2016.35     665 2017.82     686 2026.03   795.7 2026.67     830 2028.42
   938.6 2038.99  1065.7 2042.54  1102.9 2045.22  1144.6  2051.2  1214.4 2068.44
#Mann= 8 ,-1 , 0
       0     .06       0  124.69      .1       0  232.54      .1       0
   364.7     .05       0  561.15      .1       0  580.77    .045       0
  640.41      .1       0   743.4     .05       0
Bank Sta=580.77,640.41
XS Rating Curve= 0 ,0
Exp/Cntr=0.3,0.1

Type RM Length L Ch R = 1 ,65895   ,599,590.5,573.4
XS GIS Cut Line= 2
2158381.53190114377859.9352875652157115.84250338377515.755201638
#Sta/Elev= 30
       0 2140.88      65 2123.72   214.6 2079.76   224.7 2075.89   238.4 2067.76
   248.6 2064.39   276.5 2062.69   357.4 2053.75   377.8 2050.03   401.6 2043.27
   418.6 2033.59     439 2030.72   449.2 2024.49   462.8 2012.89   544.4 2013.18
  557.452011.913   568.2 2008.86   584.7 2008.41   615.8 2008.48  629.592010.658
   646.4 2013.53   666.8 2012.77   700.5 2015.79   840.2 2014.17   979.6 2016.03
    1068 2015.52  1159.8 2018.29  1214.2 2024.87  1251.6 2032.51  1311.7 2053.83
#Mann= 5 ,-1 , 0
       0      .1       0  557.45    .045       0  629.59      .1       0
  651.54     .05       0 1277.22      .1       0
#XS Ineff= 2 , 0
                          958.41        2023.919
Permanent Ineff=
       F       F
Bank Sta=557.45,629.59
XS Rating Curve= 0 ,0
Exp/Cntr=0.3,0.1

Type RM Length L Ch R = 1 ,65304   ,548.2,539,526
XS GIS Cut Line= 2
2158483.77546306 377111.825891392157111.67584506377165.755245477
#Sta/Elev= 30
       0 2153.95    79.8 2118.47   171.5 2071.72   230.8 2045.66   270.2 2042.85
   309.6  2045.4     333 2044.06   365.4 2037.62   431.1 2016.51   477.1 2014.15
   506.6    2011   516.5 2008.01     527 2003.89     569 2003.61   601.8 2008.27
   621.5 2013.23   667.5 2010.88   937.1 2010.22   976.1 2010.89  1012.2 2015.75
  1038.5 2016.94    1091 2017.09  1160.7 2014.02  1224.2 2015.75  1249.1 2019.17
  1268.1 2024.62  1307.7 2040.93  1327.4 2044.03  1353.7 2060.36  1373.2 2069.76
#Mann= 6 ,-1 , 0
       0      .1       0  450.22      .1       0   516.5    .045       0
   601.8      .1       0  658.78     .05       0 1222.46      .1       0
Bank Sta=516.5,601.8
XS Rating Curve= 0 ,0
Exp/Cntr=0.3,0.1

Type RM Length L Ch R = 1 ,64765   ,683.1,660.7,630.9
XS GIS Cut Line= 2
2158299.17576663376451.1720289742157226.25894922376803.255314305
#Sta/Elev= 30
       0 2303.76    24.3 2287.38    45.5 2268.92    76.1 2244.69   100.2 2221.76
   110.6 2214.35   138.2 2186.75   155.5  2172.6   217.6 2125.96   255.6 2099.57
   299.5 2072.18     373 2030.95     411 2018.17   428.3 2009.47  468.052003.872
   476.6 2002.18   493.9 2002.11   524.9 2002.33  540.062005.496   580.2 2009.02
   645.8 2007.15     777  2006.6   915.1 2007.58   942.8 2008.93   949.7 2009.82
   973.8 2027.09  1001.5 2038.56    1049    2044  1078.2 2051.15  1129.2 2055.58
#Mann= 5 ,-1 , 0
       0      .1       0  468.05    .045       0  540.06      .1       0
  547.61     .05       0  929.01      .1       0
Bank Sta=468.05,540.06
XS Rating Curve= 0 ,0
Exp/Cntr=0.3,0.1

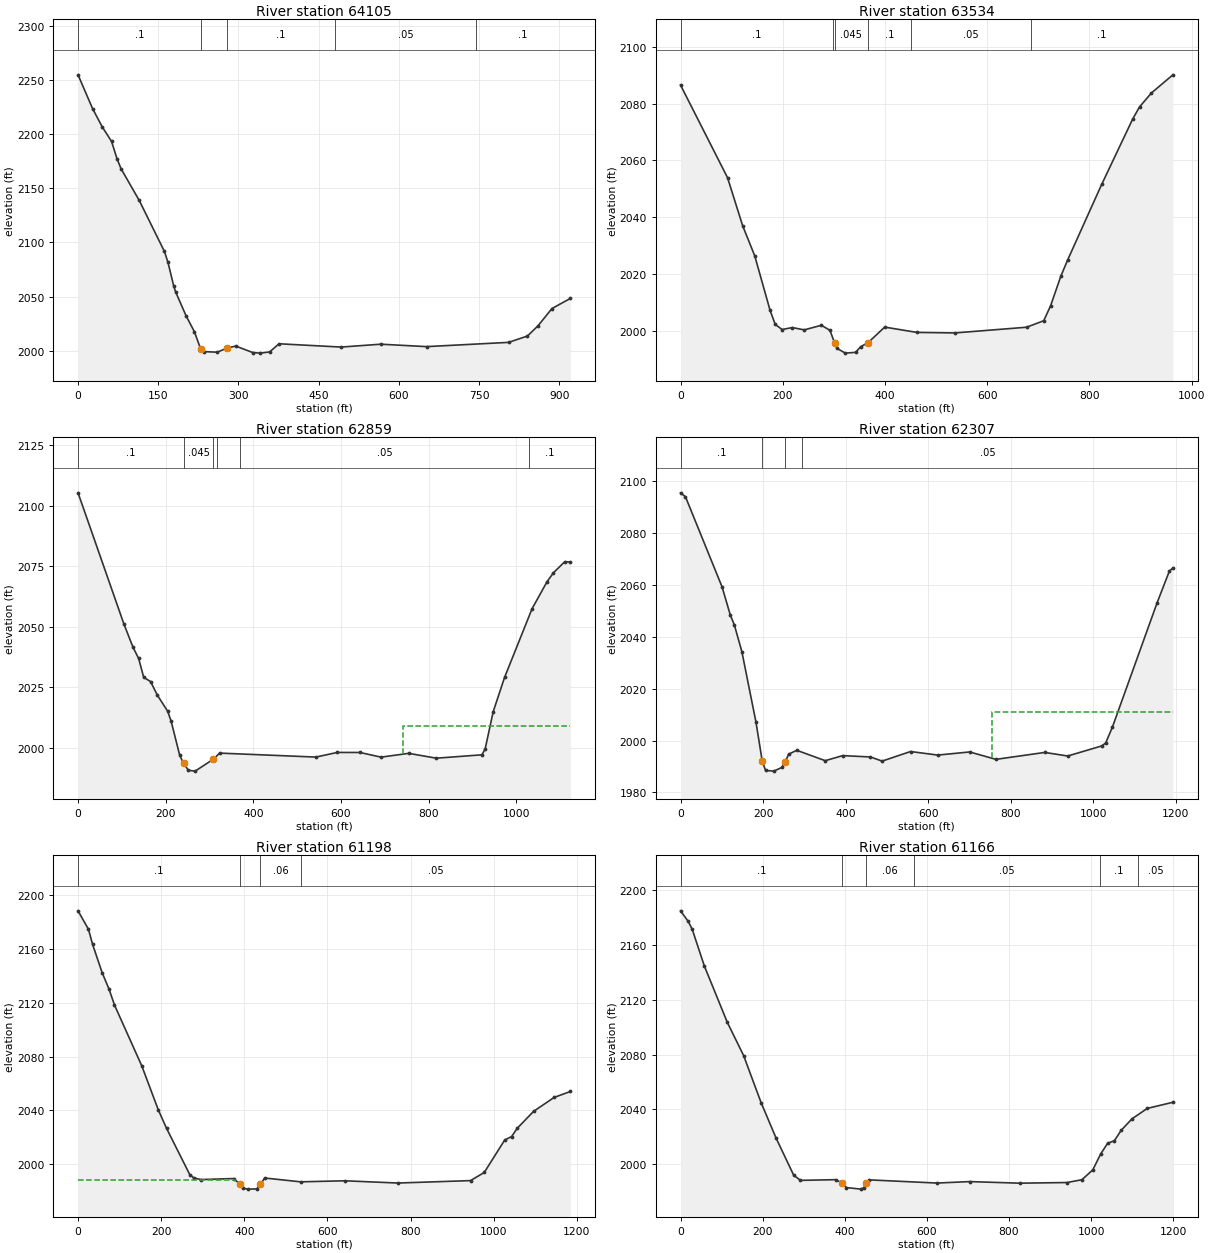
Type RM Length L Ch R = 1 ,64105   ,573.1,570.8,565.8
XS GIS Cut Line= 2
2157498.30761772375902.1396624742157164.97429489376760.473247647
#Sta/Elev= 30
       0 2254.88    27.2 2223.65    45.1 2206.92    62.7 2193.31    72.8 2177.48
    80.3 2168.23   114.5 2138.76   161.6 2091.62   168.3 2081.45   178.8    2060
   182.4 2054.42   202.1 2032.12   217.6 2017.51  229.382001.453   235.2 1999.09
   260.4 1998.55  278.532002.351     295 2004.22   326.7 1998.23   340.7 1997.69
   358.3 1998.78   375.9 2006.33   492.1 2003.29     566 2005.94   651.8  2003.7
   805.3 2007.63   840.5  2013.5   860.3 2022.95   886.3  2038.9   920.8 2048.25
#Mann= 5 ,-1 , 0
       0      .1       0  229.38    .045       0  278.53      .1       0
  481.13     .05       0  744.49      .1       0
Bank Sta=229.38,278.53
XS Rating Curve= 0 ,0
Exp/Cntr=0.3,0.1

Type RM Length L Ch R = 1 ,63534   ,665.3,674.5,689.8
XS GIS Cut Line= 2
2156909.70807314 375765.855158152156720.17105064376710.299463481
#Sta/Elev= 30
       0 2086.51      92 2053.91   121.6 2036.99   145.1 2026.48   175.1 2007.31
   185.2 2002.35   198.6 2000.54   218.7 2001.22   242.1 2000.41   275.6 2002.03
   292.3 2000.25  301.431995.822   305.7 1993.95   322.4 1992.23   342.5 1992.51
   352.5 1994.49  366.961995.924   399.4 2001.39   462.3 1999.52   536.6 1999.33
   677.1 2001.34   710.6 2003.63     724 2008.89     744 2019.27   757.4 2025.01
     824  2051.6   884.6 2074.56     898 2078.83   921.4 2083.76   963.3 2090.12
#Mann= 6 ,-1 , 0
       0      .1       0  298.74      .1       0  301.43    .045       0
  366.96      .1       0  450.07     .05       0  686.17      .1       0
Bank Sta=301.43,366.96
XS Rating Curve= 0 ,0
Exp/Cntr=0.3,0.1

Type RM Length L Ch R = 1 ,62859   ,565.2,552,536.1
XS GIS Cut Line= 3
2156392.39349097375588.771850899 2156192.3932348375897.104895636
2155840.30994947376565.855198562
#Sta/Elev= 30
       0 2105.36   104.8 2051.06   125.6 2041.45   138.2  2036.9   149.8  2029.1
   165.5 2027.33   181.2 2021.64   204.4 2015.11   212.5  2010.9     232 1996.83
  240.681993.556   251.8 1990.66   267.2 1990.31  308.981995.272     323 1997.76
   542.7 1996.12   591.3 1998.03   643.2 1998.02   691.4 1996.09   754.4 1997.66
   817.4 1995.66   921.3 1997.05   928.7 1999.37   947.2 2014.88   973.2 2029.08
    1036  2057.5    1070 2068.59  1084.6  2072.3  1110.4 2076.88  1123.3 2076.76
#Mann= 6 ,-1 , 0
       0      .1       0  240.68    .045       0  308.98      .1       0
  317.73      .1       0  370.18     .05       0 1028.22      .1       0
#XS Ineff= 1 ,-1
  740.92 1123.29 2009.02
Permanent Ineff=
       F
Bank Sta=240.68,308.98
XS Rating Curve= 0 ,0
Exp/Cntr=0.3,0.1

Type RM Length L Ch R = 1 ,62307   ,1104.2,1109.4,1102.4
XS GIS Cut Line= 3
2155771.56008697375345.021682233 2155750.7267953375642.938409224
2155715.30987139 376536.68826215
#Sta/Elev= 30
       0 2095.54    11.9 2094.03   100.7 2059.23   120.4  2048.5   130.3 2044.63
   148.6 2034.29   182.9 2007.01  198.011991.997     206 1988.49   225.7 1988.22
   245.4 1989.63   253.21991.583   261.9 1994.76   281.6 1996.25   350.6 1992.25
   392.9  1994.2     460 1993.68   488.6 1992.09   557.4 1995.78   623.1 1994.41
   700.6 1995.61   764.3 1992.76   882.5 1995.43   938.3 1994.05  1020.4 1997.93
  1030.2 1999.06  1046.7 2005.27    1155 2053.21  1184.6 2065.38  1193.1 2066.59
#Mann= 4 ,-1 , 0
       0      .1       0  198.01    .045       0   253.2      .1       0
  294.13     .05       0
#XS Ineff= 1 ,-1
  755.18 1193.09 2011.06
Permanent Ineff=
       F
Bank Sta=198.01,253.2
XS Rating Curve= 0 ,0
Exp/Cntr=0.5,0.3

Type RM Length L Ch R = 1 ,61198   ,31.4,31.9,32.1
XS GIS Cut Line= 3
2154787.54860355375591.0546547322154743.06083164376099.952258974
2154676.87165955376770.525064811
#Sta/Elev= 30
       0 2188.18    25.1 2174.48      35 2163.29    58.1 2142.19    74.5 2130.11
    87.7 2118.27   153.6 2072.92   193.1 2040.43   212.9 2026.75   268.8 1992.39
   278.7 1989.86   295.7 1988.67   374.2 1989.42  389.681985.346   397.3 1982.11
   409.8 1981.57   430.2 1981.71   438.81985.138   449.2 1989.83   535.6 1986.98
   641.8 1987.76   769.7 1986.09   944.4  1987.9   977.4 1993.92  1026.8 2018.08
  1043.3  2020.6  1056.5 2026.63  1096.1 2039.29  1145.5 2049.64  1184.7 2054.06
#Mann= 4 ,-1 , 0
       0      .1       0  389.68    .045       0   438.8     .06       0
   535.6     .05       0
#XS Ineff= 2 , 0
          379.68  1988.2   448.8          1988.2
Permanent Ineff=
       F       F
Bank Sta=389.68,438.8
XS Rating Curve= 0 ,0
Exp/Cntr=0.5,0.3

Type RM Length L Ch R = 1 ,61166   ,772.7,775.2,776.7
XS GIS Cut Line= 2
2154759.83540438375581.3063146472154647.33562939 376775.05622372
#Sta/Elev= 30
       0 2185.13    18.5 2177.48    28.4 2171.64      58 2144.77   113.9 2103.58
   153.6 2079.31   196.4 2044.73   232.7 2018.95   275.5  1991.9     292 1988.09
   377.7 1988.59  393.131986.202     404 1982.82   439.2 1981.68   446.9 1982.76
   452.11986.515   459.8 1988.44   624.8 1986.12   703.9 1987.19   825.8 1986.03
   941.2  1986.5   977.4 1988.56  1003.8 1995.72  1023.4 2007.51    1040 2015.18
  1056.6 2017.12    1073 2024.65  1099.3 2033.05  1136.5 2040.68    1199 2045.18
#Mann= 6 ,-1 , 0
       0      .1       0  393.13    .045       0   452.1     .06       0
  568.71     .05       0 1022.04      .1       0 1113.57     .05       0
Bank Sta=393.13,452.1
XS Rating Curve= 0 ,0
Exp/Cntr=0.5,0.3