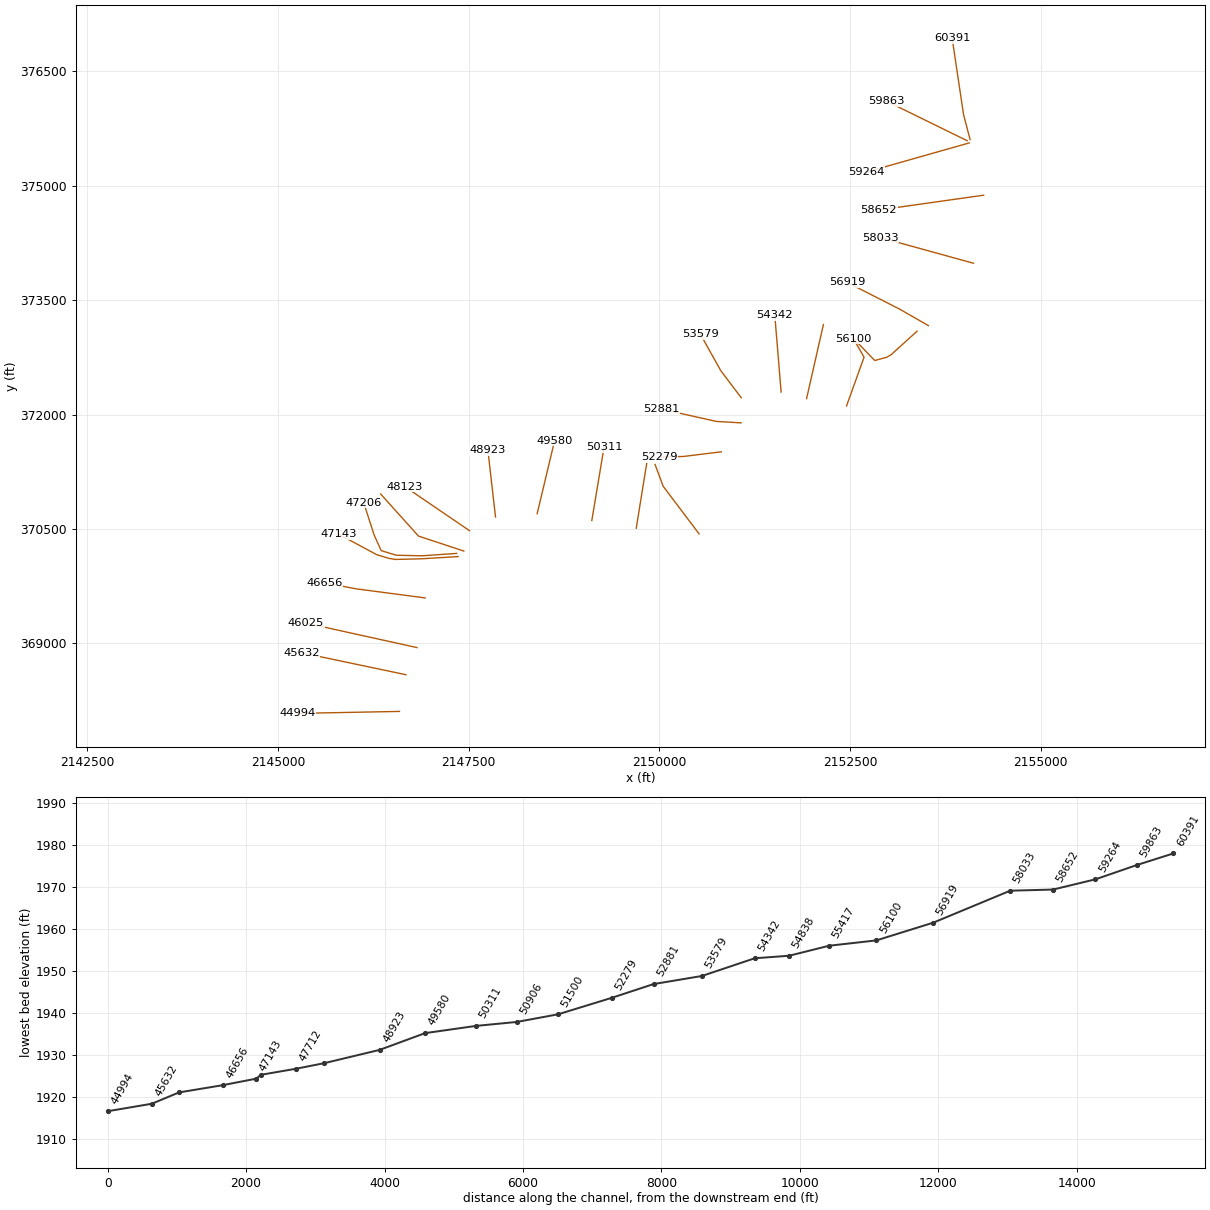
HEC-RAS study SPRINGCK.prj: SPRINGCK

--- SPRINGCK.g01 (geometry) --- (continued)

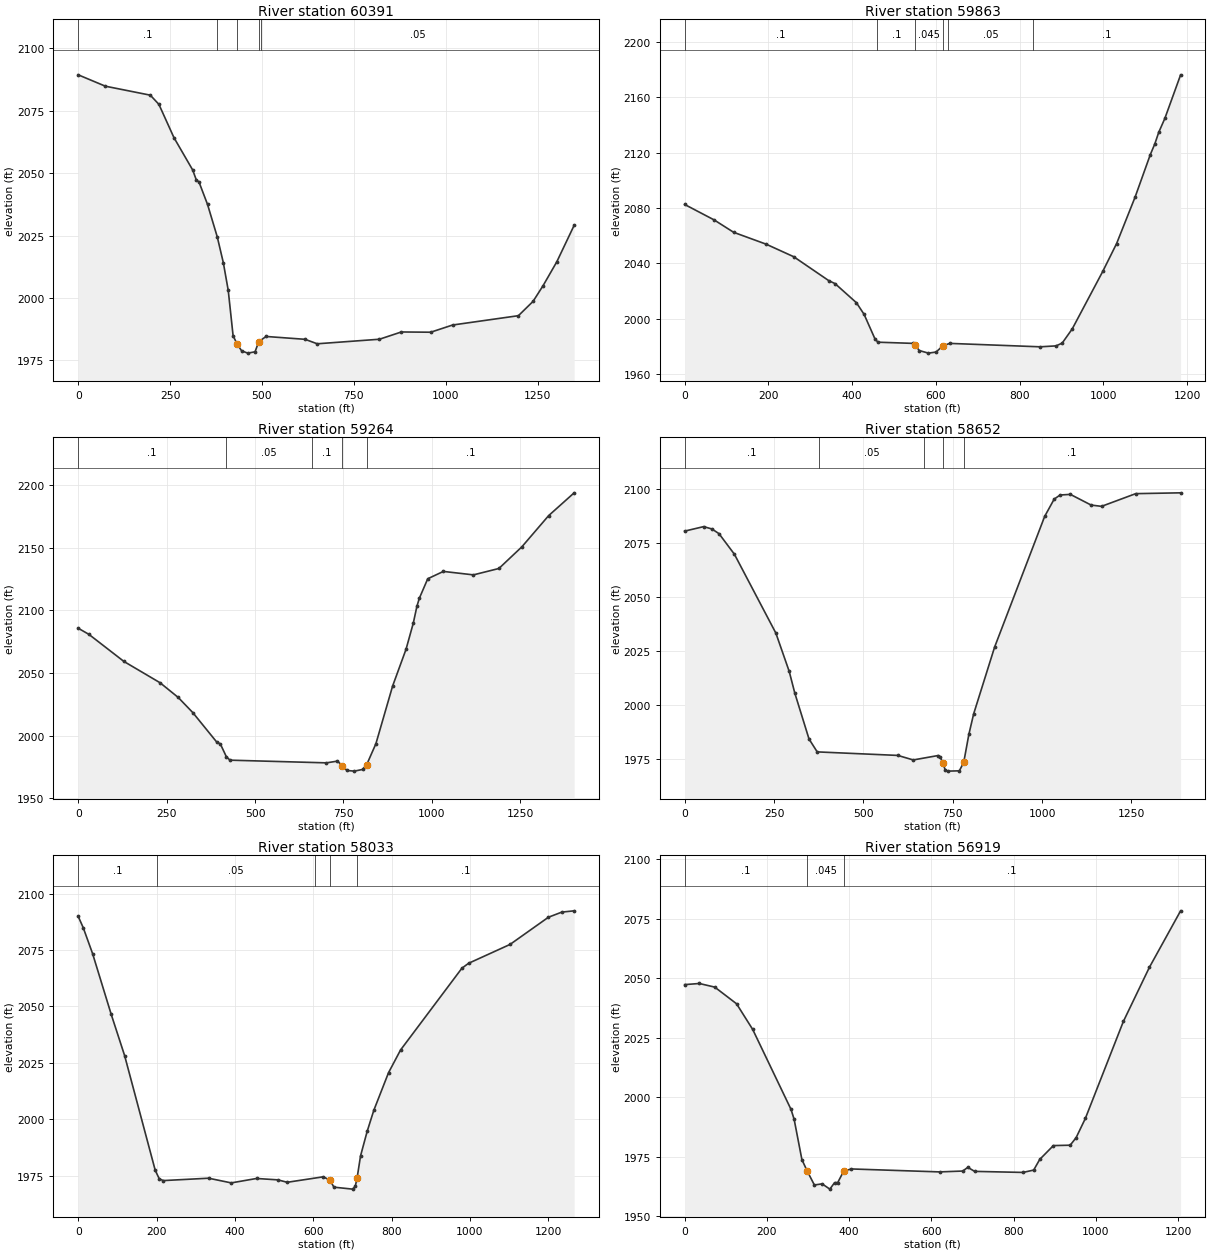
Type RM Length L Ch R = 1 ,60391   ,489.8,528.4,551.6
XS GIS Cut Line= 3
 2154073.7242438 375607.000817062153988.30774798375929.917494059
2153838.30771989376934.084120899
#Sta/Elev= 30
       0 2089.32    73.9 2084.77   196.1 2081.18   219.5 2077.51   260.5 2064.17
   311.4 2051.24   321.6 2047.13   328.4  2046.5   351.8 2037.46   378.3 2024.46
   394.9 2014.06   408.2 2003.01   421.4 1984.87  432.28 1981.56   444.6 1978.84
   461.2 1977.92   481.1 1978.45  491.23 1982.49     511 1984.59   617.1 1983.45
   650.3 1981.66   819.5 1983.48   879.2 1986.39   959.1 1986.29  1018.5 1989.17
  1197.7 1992.91  1237.5 1998.64  1264.6 2004.88  1302.1 2014.48  1349.3 2029.08
#Mann= 5 ,-1 , 0
       0      .1       0  377.57      .1       0  432.28    .045       0
  491.23      .1       0  495.97     .05       0
Bank Sta=432.28,491.23
XS Rating Curve= 0 ,0
Exp/Cntr=0.3,0.1

Type RM Length L Ch R = 1 ,59863   ,570.9,598.9,621
XS GIS Cut Line= 2
2154034.73941363375591.6383149772152971.64114614376113.250788808
#Sta/Elev= 30
       0 2082.48    70.3 2071.34   116.9 2062.39   194.5 2053.82   260.3 2044.77
   344.3 2027.44     359 2025.36   410.1 2011.55   428.4 2003.17     454 1985.69
   461.3 1983.05   545.3  1982.2  551.081980.714     560 1977.05   581.9 1975.16
   600.2 1975.93  616.691980.467     633 1982.19   848.7 1979.72   886.7 1980.39
   901.4  1982.4   925.4 1992.64   998.5 2034.29  1031.4 2054.29  1075.5 2087.81
  1111.8 2118.47  1122.7 2126.29  1131.8 2134.46  1146.6 2144.66  1184.2 2176.08
#Mann= 6 ,-1 , 0
       0      .1       0  459.94      .1       0  551.08    .045       0
  616.69      .1       0  629.83     .05       0  832.89      .1       0
Bank Sta=551.08,616.69
XS Rating Curve= 0 ,0
Exp/Cntr=0.3,0.1

Type RM Length L Ch R = 1 ,59264   ,615.7,612.1,608.3
XS GIS Cut Line= 2
2154063.03463264375562.8319421412152713.75747555375180.496092647
#Sta/Elev= 30
       0 2085.68    30.2 2080.81   129.2 2059.21   231.4 2042.23   282.5 2030.58
     324 2018.44   391.6 1994.96   401.9 1993.44   418.9 1983.25   429.1  1980.5
   701.9 1978.36   733.2 1979.74  747.071976.021   759.9 1972.27   780.8 1971.76
   804.1  1973.1  815.881977.001   841.8 1993.62   889.1 2039.63     927 2068.91
   947.5 2089.74   957.7 2103.08   964.5  2109.5   988.4 2125.14  1032.6 2130.98
  1117.6 2128.23  1189.6 2133.32  1254.4 2150.54  1330.2 2175.44  1402.4 2193.64
#Mann= 5 ,-1 , 0
       0      .1       0   418.4     .05       0  660.12      .1       0
  747.07    .045       0  815.88      .1       0
Bank Sta=747.07,815.88
XS Rating Curve= 0 ,0
Exp/Cntr=0.3,0.1

Type RM Length L Ch R = 1 ,58652   ,632.7,618.4,606.6
XS GIS Cut Line= 2
2154250.53458571374877.0678937292152876.64724164374682.768741637
#Sta/Elev= 30
       0 2080.59      53 2082.67    76.2 2081.59    96.1  2079.4   139.2 2069.86
   255.1 2033.32   292.5 2015.54   308.1 2005.52   347.9 1984.22   370.8 1978.25
   596.4 1976.61   639.5 1974.51   709.1 1976.56   715.7 1975.78  721.66 1973.04
     729 1969.99   735.6 1969.33   768.5 1969.47  780.711973.352   795.2 1986.43
   808.5 1995.85   867.2 2026.84  1007.3 2087.44  1033.8 2095.42  1050.4 2097.33
  1079.1 2097.62  1137.2 2092.67  1166.3 2092.07    1262 2097.96  1387.6 2098.34
#Mann= 5 ,-1 , 0
       0      .1       0  375.68     .05       0  670.52      .1       0
  721.66    .045       0  780.71      .1       0
Bank Sta=721.66,780.71
XS Rating Curve= 0 ,0
Exp/Cntr=0.3,0.1

Type RM Length L Ch R = 1 ,58033   ,1098.6,1114.1,1021.9
XS GIS Cut Line= 2
2154118.58996773373984.7068175672152898.10389164 374321.51257439
#Sta/Elev= 30
       0 2089.88    12.9 2084.83    36.7 2073.38    84.3 2046.44   118.4 2028.25
   196.7 1977.34   206.9 1973.65   217.1 1972.84   332.8  1973.9   390.7 1971.82
   455.3 1973.78   509.8 1973.16   533.6 1972.09   625.5 1974.51  642.891973.035
   652.7 1969.93   700.4 1969.06   707.2 1970.26  711.77 1973.77   720.8  1983.8
   737.8 1994.72   754.6 2003.95   792.2 2020.63   822.9 2030.69   979.5 2066.91
   996.5 2069.09  1102.5 2077.46  1200.4  2089.5  1234.7 2091.78  1266.1 2092.34
#Mann= 5 ,-1 , 0
       0      .1       0  200.93     .05       0  605.06      .1       0
  642.89    .045       0  711.77      .1       0
Bank Sta=642.89,711.77
XS Rating Curve= 0 ,0
Exp/Cntr=0.3,0.1

Type RM Length L Ch R = 1 ,56919   ,772.7,819.6,820.8
XS GIS Cut Line= 3
2153526.57605989373166.9984792322153151.57615373373382.276263893
2152462.33999939373732.970772475
#Sta/Elev= 30
       0  2047.4    35.6 2047.87    73.1 2046.35   126.1 2039.35   165.4 2028.55
   258.5 1994.97   266.1  1990.8     285 1973.84  298.091968.974   315.3 1963.19
   334.2 1963.66   352.9 1961.45   364.4 1964.16   372.1 1964.23  386.541968.981
   405.2 1969.93   619.6 1968.69   676.1 1969.05   688.3 1970.61   704.9 1968.91
   822.5 1968.47   848.5 1969.46   863.2 1973.94   896.4 1979.75   937.2 1979.91
   951.6 1983.06   974.1 1991.16  1066.5 2031.91  1129.9  2054.7  1205.7 2078.41
#Mann= 3 ,-1 , 0
       0      .1       0  298.09    .045       0  386.54      .1       0
Bank Sta=298.09,386.54
XS Rating Curve= 0 ,0
Exp/Cntr=0.3,0.1

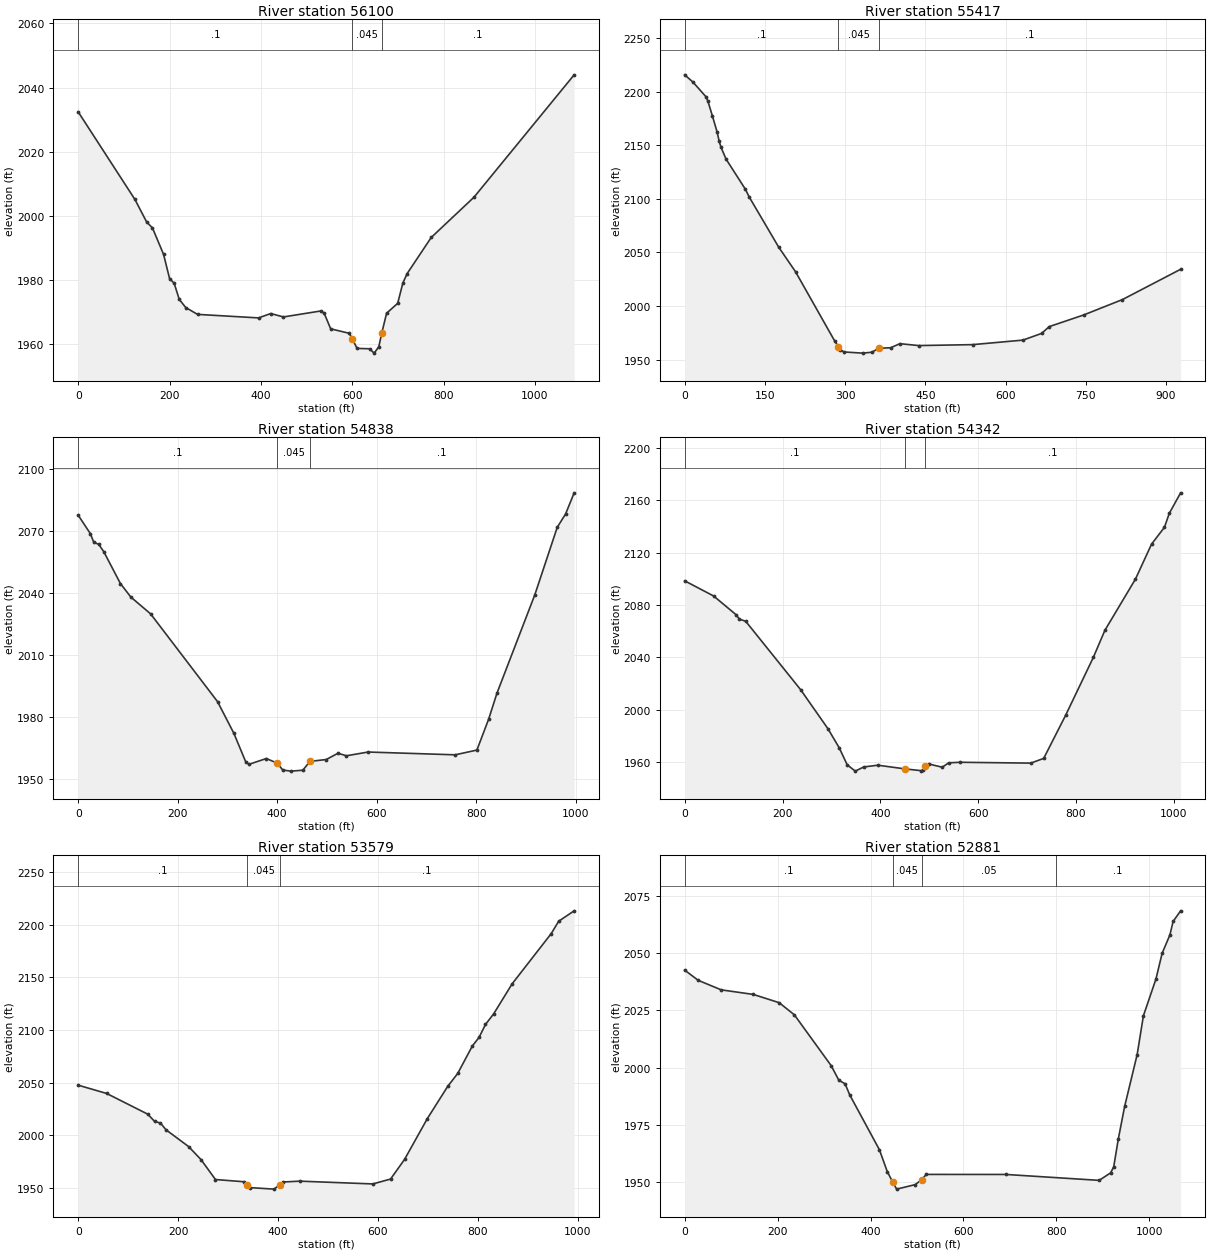
Type RM Length L Ch R = 1 ,56100   ,767.3,682.4,626.9
XS GIS Cut Line= 6
2153378.39230114373094.0750686382153036.72566164372784.352590978
2152977.00334014372751.0193243182152824.76939264372709.940010145
2152804.80420947372728.1693044012152547.85984147372996.398426726
#Sta/Elev= 30
       0 2032.44   124.2 2005.14   149.7 1998.16   162.6 1996.26   186.9 1988.02
     200 1980.49   210.1 1979.01   221.2 1974.01   235.4 1971.46   261.2 1969.33
   394.9 1968.23   421.4 1969.59   449.3 1968.53   532.4 1970.42   538.7 1969.61
   552.7 1964.82   593.5 1963.43  600.341961.573   610.5 1958.72   637.7 1958.61
   647.9 1957.25   658.1 1959.26   664.71963.599   675.1 1969.68   699.4 1972.78
   710.6 1979.05   719.9    1982   772.8  1993.3   866.4 2005.85  1085.7    2044
#Mann= 3 ,-1 , 0
       0      .1       0  600.34    .045       0   664.7      .1       0
Bank Sta=600.34,664.7
XS Rating Curve= 0 ,0
Exp/Cntr=0.3,0.1

Type RM Length L Ch R = 1 ,55417   ,575.1,578.8,582.8
XS GIS Cut Line= 3
2152453.67564663372113.9333281372152683.49342847372753.541957065
2152559.36145888 372967.95163323
#Sta/Elev= 30
       0 2215.92    15.6 2209.08      40 2195.32    43.4 2191.32    51.7 2177.74
    60.9 2162.11    64.4 2154.04    67.8 2148.44    77.3 2137.27   113.2 2109.31
   120.9 2101.63   175.9  2054.9   207.3    2032   280.5 1967.32  287.541962.098
     291 1959.25   297.9 1957.06   332.8 1955.98   350.2 1956.82  362.691960.497
   385.1    1961   402.5 1964.81   437.4 1963.04   538.5 1963.91   632.6 1968.14
   667.5 1974.41   681.7 1980.74     746  1991.6   818.6    2006   927.4 2034.29
#Mann= 3 ,-1 , 0
       0      .1       0  287.54    .045       0  362.69      .1       0
Bank Sta=287.54,362.69
XS Rating Curve= 0 ,0
Exp/Cntr=0.3,0.1

Type RM Length L Ch R = 1 ,54838   ,491.3,496.6,500.6
XS GIS Cut Line= 2
2151929.76068397372209.791732222 2152150.5942318 373182.01419723
#Sta/Elev= 30
       0 2077.56    24.4 2068.65    31.1 2064.54    41.2 2063.43    51.3 2059.95
    84.9 2044.45   105.9 2037.89   145.5 2029.79   280.1 1987.26   312.9 1971.93
   337.3 1957.79     344 1956.95   378.2 1959.71  400.111957.447   411.3  1954.1
   428.1  1953.6   451.6 1954.04   465.71958.299   498.7 1959.23   522.3 1962.27
   539.1 1961.03   582.9 1962.85   757.8  1961.5   801.5  1963.8   825.1 1978.77
   841.9 1991.41     918 2039.06     963  2071.7   979.9 2078.22     997 2088.41
#Mann= 3 ,-1 , 0
       0      .1       0  400.11    .045       0   465.7      .1       0
Bank Sta=400.11,465.7
XS Rating Curve= 0 ,0
Exp/Cntr=0.3,0.1

Type RM Length L Ch R = 1 ,54342   ,745.5,763,775.2
XS GIS Cut Line= 2
 2151596.1012463372296.1390004752151512.76775156373306.555614814
#Sta/Elev= 30
       0  2098.5      59 2086.94   105.1 2072.58   111.7 2069.26   124.8 2067.54
   236.8 2015.38   292.7 1985.52   315.8  1970.9   332.2 1957.86   348.7    1953
     366 1956.19   394.8 1957.53  451.331954.657   483.7 1953.34     487 1953.58
  490.571956.647   500.1 1958.37   526.5 1955.99   539.6 1959.33   562.7 1959.77
   707.5 1959.12   733.9 1962.74   778.6 1995.59   835.3  2039.9     859 2060.66
   921.5 2099.84   954.4 2126.56   980.8 2139.45   990.6 2150.07  1013.8 2165.78
#Mann= 3 ,-1 , 0
       0      .1       0  451.33    .045       0  490.57      .1       0
Bank Sta=451.33,490.57
XS Rating Curve= 0 ,0
Exp/Cntr=0.3,0.1

Type RM Length L Ch R = 1 ,53579   ,673.1,698,715.7
XS GIS Cut Line= 3
2151073.18431313372221.1391504712150804.43452255372577.389094144
2150537.76773305373054.472457558
#Sta/Elev= 30
       0 2047.46      57 2039.59     139    2020     153 2013.06   164.7 2011.52
   175.8 2005.08     221 1989.19   245.7 1976.88   274.8  1957.9     332 1955.79
  338.761952.919   344.3 1950.21     392 1948.79  403.911952.989   410.1 1955.55
   443.5 1956.36   589.8 1953.72   625.3 1958.36   653.2 1976.93   698.8 2015.67
   739.6 2046.26   759.8 2058.68     789 2084.67   802.6 2092.94   815.3 2105.11
   831.6 2115.12   868.7 2143.71   946.9 2191.36   961.9 2203.12   992.8 2212.98
#Mann= 3 ,-1 , 0
       0      .1       0  338.76    .045       0  403.91      .1       0
Bank Sta=338.76,403.91
XS Rating Curve= 0 ,0
Exp/Cntr=0.3,0.1

Type RM Length L Ch R = 1 ,52881   ,591,601.7,589
XS GIS Cut Line= 3
2151071.10098398371891.9724859742150748.18430696371910.722448483
2150022.11358064372072.812019303
#Sta/Elev= 30
       0 2042.58    29.3 2038.11    78.6 2033.96   147.6 2031.97   203.4 2028.35
   236.1 2023.04   315.2 2000.86   331.8 1994.46   345.2 1992.92   355.3 1988.03
   419.2 1964.05     436 1954.56  447.531950.023   456.2 1946.87   496.3 1948.85
  510.271951.051     520  1953.3   691.5 1953.28     892  1950.7   916.7 1953.97
   923.4  1956.6   933.2 1968.67   946.9 1982.99   973.9  2005.7   987.3 2022.63
  1014.2 2038.63  1027.6 2049.93  1044.5 2058.06  1051.2 2063.85  1067.4  2068.5
#Mann= 4 ,-1 , 0
       0      .1       0  447.53    .045       0  510.27     .05       0
  798.67      .1       0
Bank Sta=447.53,510.27
XS Rating Curve= 0 ,0
Exp/Cntr=0.3,0.1

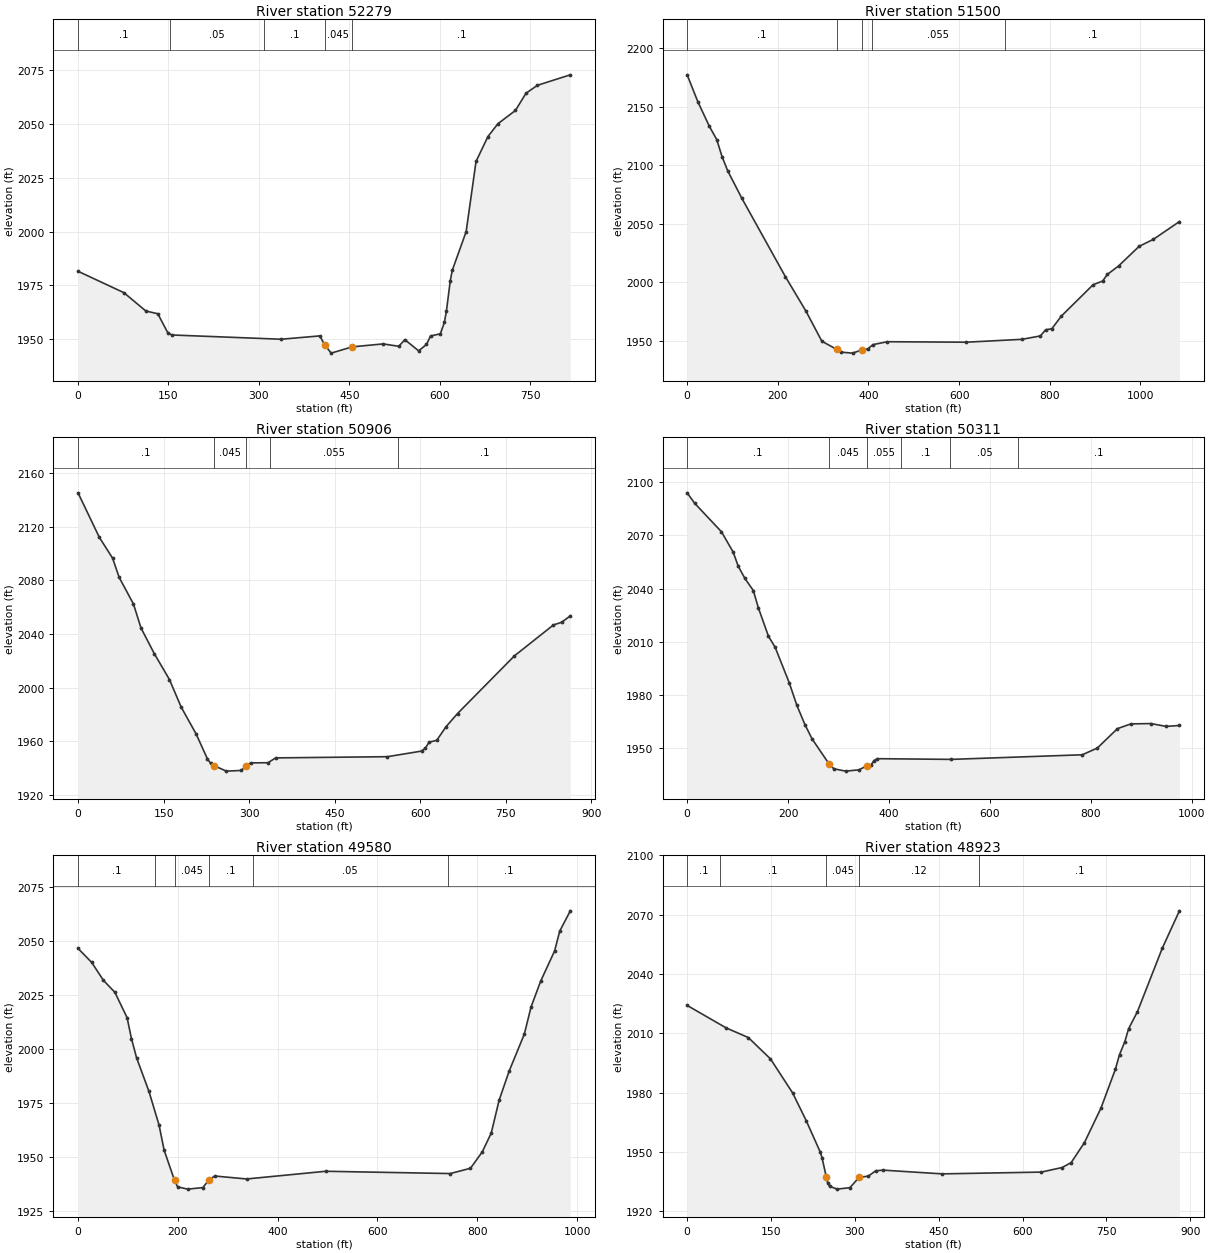
Type RM Length L Ch R = 1 ,52279   ,804.9,779,745.4
XS GIS Cut Line= 3
2150812.26291896371512.4312503042150312.26293471371450.972711816
2149999.76290356371443.681059733
#Sta/Elev= 30
       0 1981.57    76.1 1971.64   112.4 1963.16   132.3 1961.86   148.8 1953.08
   155.4 1952.03   337.2 1950.05     401 1951.61   408.9 1947.49   419.8 1943.61
  454.691946.527   505.8 1947.88     532 1946.78   541.9 1949.86   564.8 1944.68
   577.8 1947.62   584.5 1951.54   600.9 1952.59   607.5 1957.87   610.8 1962.96
   617.3  1977.2   620.6    1982   643.6 1999.96     660  2032.5   679.7 2044.04
   696.4 2050.01   725.3 2056.14   742.8  2064.1   761.7 2067.81   816.3 2072.67
#Mann= 5 ,-1 , 0
       0      .1       0  152.48     .05       0  308.32      .1       0
   408.9    .045       0  454.69      .1       0
Bank Sta=408.9,454.69
XS Rating Curve= 0 ,0
Exp/Cntr=0.3,0.1

Type RM Length L Ch R = 1 ,51500   ,617.6,594.2,572.5
XS GIS Cut Line= 3
2150520.59617947370436.3894391512150049.76280355371060.347836897
2149943.51268797371345.764588892
#Sta/Elev= 30
       0 2177.29    23.7 2154.22    48.9 2133.41    65.3 2121.99      77 2107.48
    89.5 2095.31   120.4 2072.08   216.9 2004.86   262.1 1975.57   297.2 1949.83
  330.331942.813   339.4 1940.52   364.9 1939.68  385.931942.459     398 1943.13
   410.1 1946.95   441.8 1949.42   615.6    1949   738.9 1951.47   779.5 1954.38
   790.8 1959.51   804.8 1960.54   825.5 1971.23   895.8 1998.09   916.8 2001.22
   927.3 2006.91   951.8 2014.05   997.3 2030.85  1028.8 2036.85  1086.2 2051.99
#Mann= 5 ,-1 , 0
       0      .1       0  330.33    .045       0  385.93      .1       0
  406.95    .055       0  701.54      .1       0
Bank Sta=330.33,385.93
XS Rating Curve= 0 ,0
Exp/Cntr=0.3,0.1

Type RM Length L Ch R = 1 ,50906   ,593.7,594.6,595.6
XS GIS Cut Line= 2
2149696.63785364370510.3479526492149834.13790672 371362.43122223
#Sta/Elev= 30
       0 2145.11    37.3 2111.99    60.6 2096.46    72.1 2082.15    97.2 2062.32
   110.4 2044.47   133.7 2025.38   160.3 2006.05     181 1985.43   206.9 1965.68
   226.8 1947.08   232.5 1943.63  238.66 1941.93     260 1937.87   286.6 1938.38
  294.241941.904   303.2 1944.02   333.1 1944.12   346.4 1947.72   542.5 1948.62
   602.3 1952.79   608.9 1955.02   615.6 1959.45   628.9  1960.8   645.5  1971.1
   665.4 1980.76   765.1 2023.68   833.5 2046.73   847.8 2048.69   863.1 2053.47
#Mann= 5 ,-1 , 0
       0      .1       0  238.66    .045       0  294.24      .1       0
  337.01    .055       0  561.56      .1       0
Bank Sta=238.66,294.24
XS Rating Curve= 0 ,0
Exp/Cntr=0.3,0.1

Type RM Length L Ch R = 1 ,50311   ,731.9,731.3,727.8
XS GIS Cut Line= 2
2149114.34603922370611.3894172312149274.76271313371573.889460728
#Sta/Elev= 30
       0 2094.03    14.8 2088.17      68 2072.05    91.3 2060.55   101.2 2052.63
   114.5 2045.71   131.2 2038.85   141.1 2029.15   161.1 2013.12   174.4 2006.85
   202.3 1986.85   217.6 1973.97   233.6 1963.12   247.6 1955.13   281.61940.875
   290.8 1938.24   314.1 1936.92   340.7 1937.65  356.911940.034     364  1940.2
   370.6 1942.88   377.3 1943.94   523.6 1943.55   783.1 1946.15     813 1949.92
   852.9  1960.9   879.5 1963.58   919.5 1963.77   949.4 1962.17   975.8 1962.68
#Mann= 6 ,-1 , 0
       0      .1       0   281.6    .045       0  356.91    .055       0
  424.34      .1       0  521.86     .05       0  656.34      .1       0
Bank Sta=281.6,356.91
XS Rating Curve= 0 ,0
Exp/Cntr=0.3,0.1

Type RM Length L Ch R = 1 ,49580   ,646.5,656.8,668.2
XS GIS Cut Line= 2
2148397.67949356370700.9728994822148626.84602997371660.347949222
#Sta/Elev= 30
       0 2046.57    27.4 2040.06      51 2031.76    73.8 2026.26    98.3 2014.54
   107.1 2004.79   117.3 1995.97   142.1 1980.42   162.4 1964.81   172.5 1953.25
  193.341939.283   199.5 1936.27   219.7 1935.21   250.1 1935.91  262.161939.426
   273.7 1941.28   337.9 1939.91   496.3 1943.47   745.9 1942.41   786.4 1944.86
     810 1952.43     828 1961.15   843.7 1976.28     864 1989.88   894.3 2006.93
   907.8  2019.5     927 2031.39     955 2045.42   965.2 2054.54   986.4 2063.94
#Mann= 6 ,-1 , 0
       0      .1       0  154.07      .1       0  193.34    .045       0
  262.16      .1       0  349.73     .05       0  741.03      .1       0
Bank Sta=193.34,262.16
XS Rating Curve= 0 ,0
Exp/Cntr=0.3,0.1

Type RM Length L Ch R = 1 ,48923   ,778.2,800.3,817.6
XS GIS Cut Line= 2
2147851.84626764370658.2646515672147751.84613955371533.264541984
#Sta/Elev= 30
       0 2024.09    69.8 2012.71   109.5 2007.83   149.1 1997.05   188.7 1979.86
   212.9  1965.9   238.3 1949.85   241.6 1946.75  248.821937.561   251.5 1934.31
   254.8 1932.72     268 1931.23   291.1 1931.95  307.751937.201   324.1 1937.78
   337.3  1940.5   350.5 1940.83   456.2 1938.94   633.7 1939.84   670.8 1942.15
     687 1944.62   710.7  1954.7   740.4 1972.21   766.1 1991.79   773.5  1999.2
   783.1 2005.83   789.7 2012.24   805.6 2020.93     850 2052.97   880.7 2071.89
#Mann= 5 ,-1 , 0
       0      .1       0   58.04      .1       0  248.82    .045       0
  307.75     .12       0  522.55      .1       0
Bank Sta=248.82,307.75
XS Rating Curve= 0 ,0
Exp/Cntr=0.3,0.1

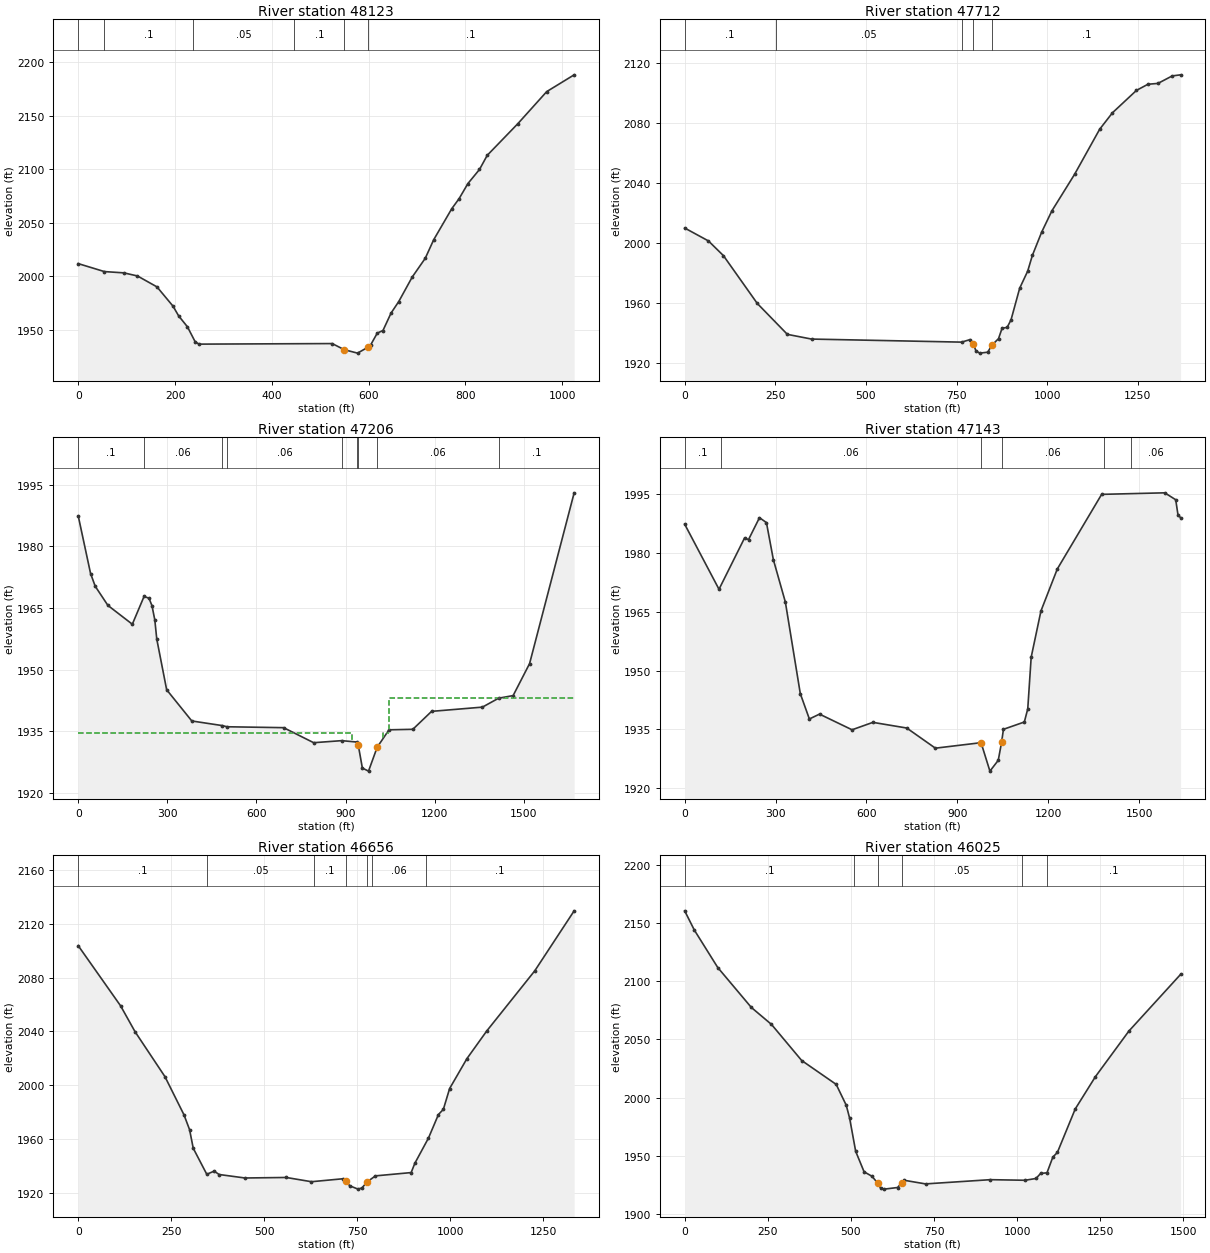
Type RM Length L Ch R = 1 ,48123   ,417.2,411.1,406.1
XS GIS Cut Line= 2
2147511.22096464370478.0563505592146664.34601797371055.139513984
#Sta/Elev= 30
       0  2011.7    54.1 2004.25    94.3 2003.06   122.5 2000.15   162.8 1989.94
   195.8 1972.01   207.6 1962.82   225.7 1952.66   241.6 1938.74   249.5 1936.48
   524.8    1937  550.05 1931.24   577.2 1928.07  599.17 1933.72   604.3 1935.73
     618 1946.79   629.7 1949.18   646.5 1965.52   662.4 1976.29   690.2 1999.16
   717.1 2016.66   734.6 2034.02   771.9    2063     787 2072.35   805.3  2086.5
   829.2 2099.67   845.2 2112.87   908.6  2142.5   968.1 2172.39  1024.8 2188.07
#Mann= 6 ,-1 , 0
       0      .1       0   52.97      .1       0  237.92     .05       0
  446.18      .1       0  550.05    .045       0  599.17      .1       0
Bank Sta=550.05,599.17
XS Rating Curve= 0 ,0
Exp/Cntr=0.3,0.1

Type RM Length L Ch R = 1 ,47712   ,495.6,505.3,514.7
XS GIS Cut Line= 3
2147436.09086555370211.042448893 2146842.3410688370407.222830817
2146345.81319048370959.306044221
#Sta/Elev= 30
       0 2010.23    65.5 2001.61   106.9 1991.79   200.2  1959.9   283.2 1939.26
   349.9 1936.12   763.9 1934.08   787.1 1935.78  795.411933.134   803.4 1928.24
   813.6 1926.74   835.7 1927.36  847.751932.158   865.6 1936.41   875.4 1943.34
   889.3 1943.91     900 1948.88   923.9 1970.04     946 1981.44     959 1991.99
   984.6  2007.5  1012.8 2021.69  1075.2 2045.99  1144.5 2076.12  1179.8 2087.11
    1246 2102.05  1277.7 2106.15  1305.2 2106.71  1344.7 2111.72  1367.8 2112.44
#Mann= 5 ,-1 , 0
       0      .1       0  251.15     .05       0   763.9      .1       0
  795.41    .045       0  847.75      .1       0
Bank Sta=795.41,847.75
XS Rating Curve= 0 ,0
Exp/Cntr=0.5,0.3

Type RM Length L Ch R = 1 ,47206   ,59.6,63,72.6
XS GIS Cut Line= 6
2147342.47097406370180.1396235672146889.34622414370148.889686063
2146551.84624296370156.1813381462146353.53528789370216.394800395
2146261.63717772370417.9714969842146123.83331947370844.404043064
#Sta/Elev= 30
       0 1987.45    41.6 1973.41    57.3  1970.3     100 1965.64   182.2 1961.06
   221.7 1967.82   238.2  1967.4   248.3  1965.6   257.9 1962.11   264.5 1957.45
   297.8 1945.11   382.5 1937.51   484.7 1936.39   501.1  1936.1   691.5 1935.88
   792.8 1932.22   887.3 1932.72   938.7 1932.38  943.031931.605   956.8 1926.04
   977.5  1925.3 1006.721931.125  1046.5 1935.36  1126.7 1935.48  1189.9 1939.85
    1361 1940.88  1415.5 1943.05  1464.4 1943.69  1519.8 1951.47  1669.9 1993.05
#Mann= 9 ,-1 , 0
       0      .1       0   221.7     .06       0   484.7     .05       0
   501.1     .06       0   887.3     .05       0   938.7      .1       0
  943.03    .045       0 1006.72     .06       0  1415.5      .1       0
#XS Ineff= 3 ,-1
       0  923.03  1934.7 1026.72  1047.2  1934.7  1047.2 1669.88 1943.02
Permanent Ineff=
       F       F       F
Bank Sta=943.03,1006.72
XS Rating Curve= 0 ,0
Exp/Cntr=0.5,0.3

Type RM Length L Ch R = 1 ,47143   ,480.9,487.7,489
XS GIS Cut Line= 6
2147361.22126463370138.4727121442146875.80458455370109.306103811
2146539.34626797370100.9727871422146456.01277322370114.514426723
2146292.47110556370164.5146548152145800.80443797370429.097787067
#Sta/Elev= 30
       0 1987.24   113.3 1970.68   197.6 1983.72   210.8 1983.32   246.9  1988.9
   269.9 1987.64   292.7 1978.23   332.4 1967.41   381.7 1944.11   411.6 1937.67
   445.1 1938.91   552.5 1934.92   621.3 1936.81     733 1935.37   827.6 1930.24
  978.341931.639  1007.6  1924.4  1035.1 1927.15  1046.11931.722  1052.2 1935.04
  1121.2  1936.9  1132.5 1940.24  1143.8 1953.39  1176.1 1965.17  1230.1 1975.85
  1376.4 1994.83  1584.8 1995.22  1620.9 1993.46  1628.4 1989.62  1637.1 1988.88
#Mann= 6 ,-1 , 0
       0      .1       0  119.64     .06       0  978.34    .045       0
  1046.1     .06       0 1382.88      .1       0 1472.67     .06       0
Bank Sta=978.34,1046.1
XS Rating Curve= 0 ,0
Exp/Cntr=0.5,0.3

Type RM Length L Ch R = 1 ,46656   ,633.5,630.2,623.5
XS GIS Cut Line= 3
2146929.14634138369596.4590323872146019.42440756369716.250787556
 2145611.4380188369794.375631318
#Sta/Elev= 30
       0 2103.79     114 2059.04   152.7 2039.87   233.1 2006.46   284.3 1978.07
   299.3 1967.04   309.2 1953.22   345.6 1933.86   365.4 1936.23   378.7 1933.71
   448.2 1931.12   559.2  1931.5   626.9 1928.35   712.9 1930.58  720.951928.719
   729.5 1925.35   752.1 1922.84   762.5 1923.72  776.661928.235   798.9 1932.69
   894.9 1935.14   904.8 1942.05   941.5 1960.83   968.2 1978.27   981.5 1982.17
   998.3 1997.62  1044.9 2019.88  1098.2 2040.44  1227.2 2085.12    1333 2129.69
#Mann= 7 ,-1 , 0
       0      .1       0  346.81     .05       0  633.12      .1       0
  720.95    .045       0  776.66      .1       0  788.43     .06       0
  935.03      .1       0
Bank Sta=720.95,776.66
XS Rating Curve= 0 ,0
Exp/Cntr=0.3,0.1

Type RM Length L Ch R = 1 ,46025   ,399.6,393.4,393.1
XS GIS Cut Line= 2
2146821.50744906368945.4173554782145364.91029663369266.597815484
#Sta/Elev= 30
       0 2160.75      29  2144.2    99.5 2111.92   200.5 2077.55   261.1 2062.93
   351.9 2031.87   455.7  2011.3   485.9 1993.37     496 1982.35   514.3 1953.69
   539.6 1936.01   563.2 1932.22  580.241926.395     590 1921.73   600.1 1921.12
   640.4 1922.51  652.371926.547   660.2 1928.74   724.4 1925.62   919.3 1929.26
  1023.6 1928.75  1056.6 1930.28  1070.5  1934.6  1089.7 1935.19  1107.4 1948.76
  1120.9 1952.69  1174.6 1990.12  1235.5 2018.02  1335.9 2057.18  1491.6 2106.04
#Mann= 6 ,-1 , 0
       0      .1       0  509.09      .1       0  580.24    .045       0
  652.37     .05       0 1014.27     .06       0 1088.93      .1       0
Bank Sta=580.24,652.37
XS Rating Curve= 0 ,0
Exp/Cntr=0.3,0.1

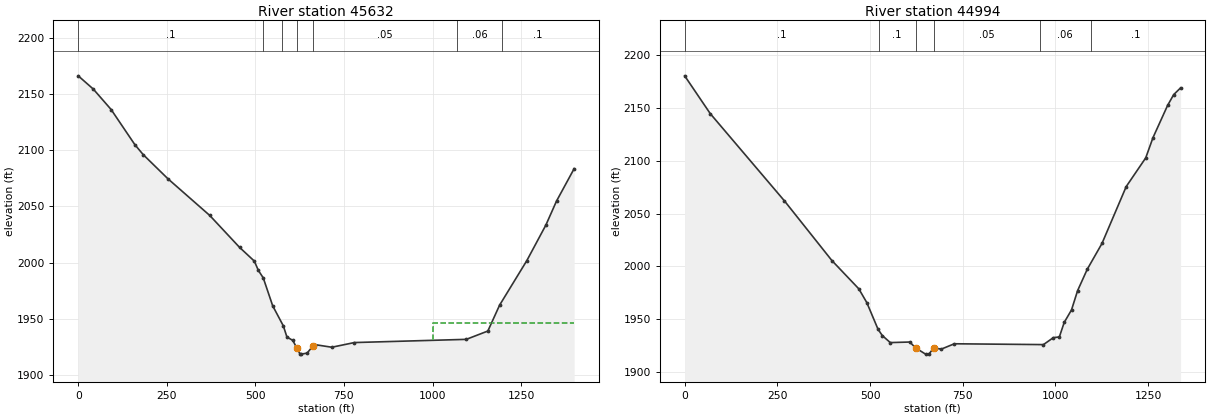
Type RM Length L Ch R = 1 ,45632   ,632.2,637.9,643
XS GIS Cut Line= 2
2146677.41029631368589.5145239832145307.61874455368877.708829477
#Sta/Elev= 30
       0 2166.38    42.6 2154.56    92.9 2136.36   159.9 2105.05   183.4 2096.19
   253.2 2074.67   371.2    2042   455.4 2013.55     497 2001.33   508.6 1992.96
   522.3 1986.34   548.9 1961.49     579 1943.57   589.1 1933.69   605.8 1930.62
   616.31924.258     626 1918.57   629.3 1918.43   646.1 1919.34  662.19 1925.55
   669.5 1926.82   715.8 1924.57   779.5 1928.74  1095.3 1931.59  1156.2    1939
  1189.4 1962.09  1266.3  2001.8    1320 2033.43  1350.1 2054.84  1399.8 2083.69
#Mann= 7 ,-1 , 0
       0      .1       0  521.21      .1       0  575.09     .05       0
   616.3    .045       0  662.19     .05       0 1069.14     .06       0
 1196.92      .1       0
#XS Ineff= 1 ,-1
 1002.26 1399.78 1945.98
Permanent Ineff=
       F
Bank Sta=616.3,662.19
XS Rating Curve= 0 ,0
Exp/Cntr=0.3,0.1

Type RM Length L Ch R = 1 ,44994   ,688.7,699.1,702.2
XS GIS Cut Line= 2
2146593.15915248368108.3176517342145255.53551538368082.569999814
#Sta/Elev= 30
       0  2180.6      69 2144.75   269.2 2061.97   397.1 2005.43   469.8 1978.57
   491.5 1965.41   521.8 1940.09   533.3 1934.21   554.6  1927.6   607.2 1928.13
  623.031922.559   649.8 1916.65   659.7 1917.13  671.871922.473   692.5 1921.42
   727.4 1926.47   967.9 1925.68   994.4 1932.25  1010.8 1932.95  1023.9 1946.75
  1043.6 1958.62    1060 1976.86  1086.2 1997.25  1125.7 2021.58  1191.2 2075.61
  1243.8 2102.79  1263.4 2122.01  1302.8 2152.55  1319.2 2162.79  1337.9  2169.2
#Mann= 6 ,-1 , 0
       0      .1       0  523.01      .1       0  623.03    .045       0
  671.87     .05       0  957.88     .06       0 1095.12      .1       0
Bank Sta=623.03,671.87
XS Rating Curve= 0 ,0
Exp/Cntr=0.3,0.1