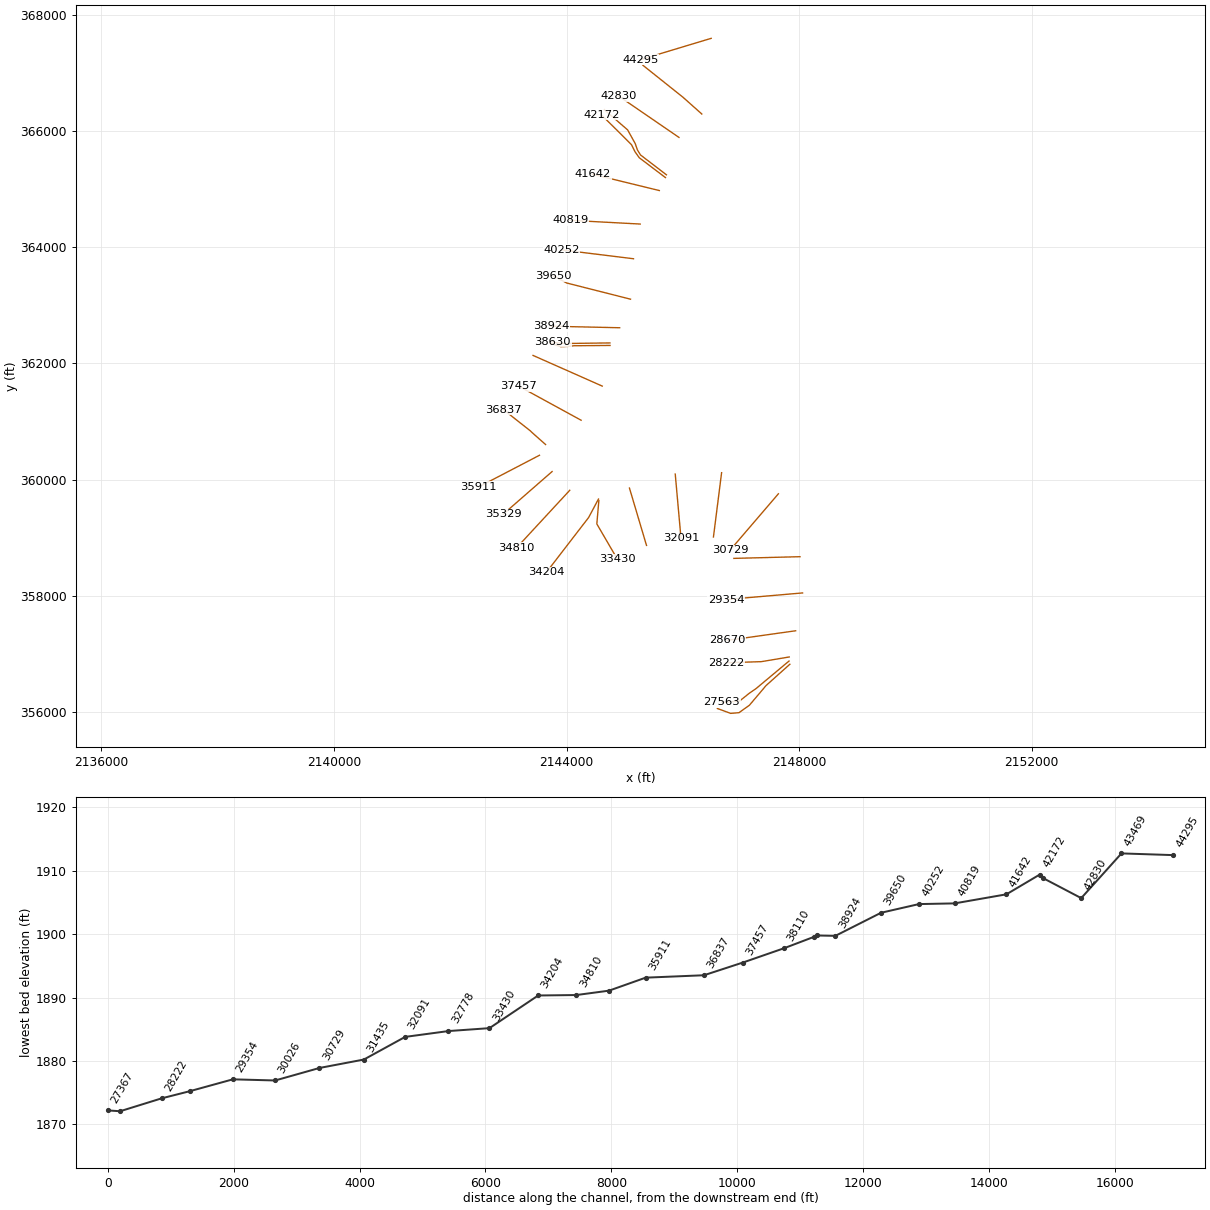
HEC-RAS study SPRINGCK.prj: SPRINGCK

--- SPRINGCK.g01 (geometry) --- (continued)

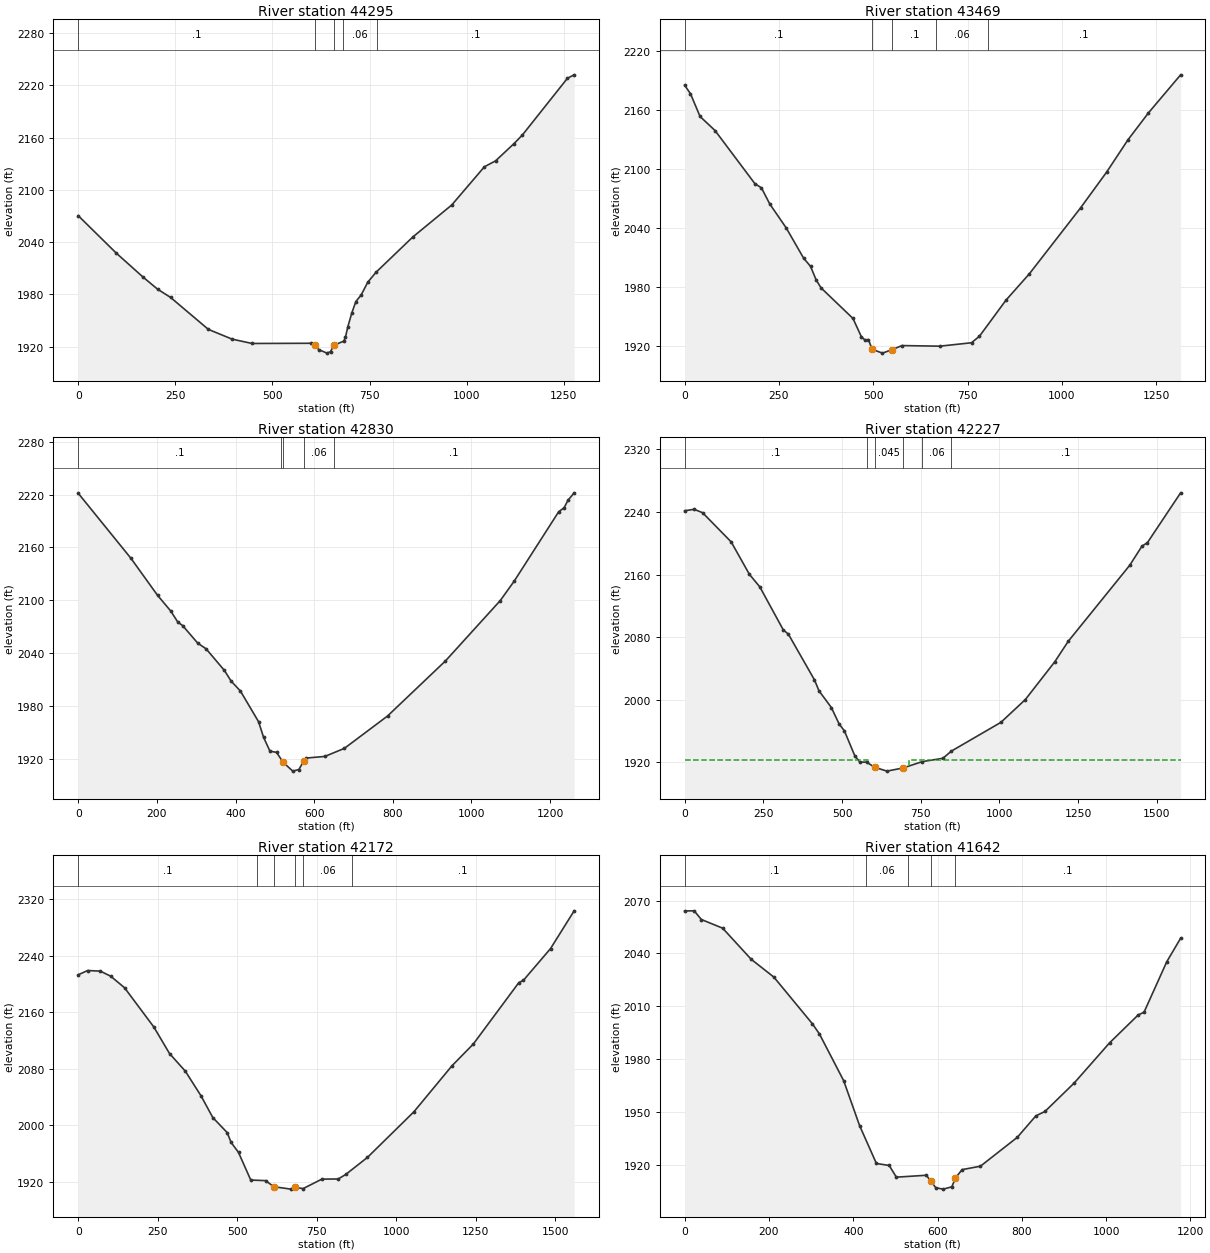
Type RM Length L Ch R = 1 ,44295   ,837.8,825.6,813.1
XS GIS Cut Line= 2
2146486.78928646367593.3757682292145264.30977605367224.637660563
#Sta/Elev= 30
       0  2070.3      98  2027.3   166.5 1999.94   204.3  1985.9   237.7 1976.46
   335.1 1939.73   396.2 1928.54   447.6 1923.55   598.3 1923.78  608.971921.248
   619.4  1916.5   640.5 1912.47   649.7 1914.17  658.081921.521     684 1926.26
   687.9 1930.61   694.3 1942.88   704.6 1958.85   714.9 1971.67   728.6 1979.32
   745.5 1993.87   766.8 2005.32   861.6 2045.85   961.7 2082.53  1045.9 2126.44
  1074.7 2133.23  1122.3 2153.13  1143.7 2162.94  1259.7 2228.06  1276.9 2231.98
#Mann= 5 ,-1 , 0
       0      .1       0  608.97    .045       0  658.08      .1       0
  682.57     .06       0  768.92      .1       0
Bank Sta=608.97,658.08
XS Rating Curve= 0 ,0
Exp/Cntr=0.3,0.1

Type RM Length L Ch R = 1 ,43469   ,634.8,639.3,642.6
XS GIS Cut Line= 3
2146324.97989881366290.9033075572146003.79911073366577.361724138
2145312.82706746367129.444937557
#Sta/Elev= 30
       0 2185.21    15.4 2176.52    40.8  2153.4    80.5 2139.11   185.9  2085.2
   203.6 2080.79   225.5 2064.49   269.4 2039.96   315.1 2009.46   333.7 2000.95
   348.5 1987.25   361.4 1979.15   446.2 1947.99   468.6 1929.25   477.7 1926.18
   487.3  1926.5   496.7 1916.66   524.4 1912.74   550.4 1916.37     576 1920.42
   676.4 1919.81   760.4 1923.29   781.5 1929.94   851.9 1966.66     914 1993.51
  1049.9 2060.66    1119 2097.04  1175.3 2129.74  1229.6 2157.12  1314.8 2195.78
#Mann= 5 ,-1 , 0
       0      .1       0   496.7    .045       0   550.4      .1       0
  666.85     .06       0  803.47      .1       0
Bank Sta=496.7,550.4
XS Rating Curve= 0 ,0
Exp/Cntr=0.3,0.1

Type RM Length L Ch R = 1 ,42830   ,617.5,603.4,570.5
XS GIS Cut Line= 2
2145932.61880688365888.1255698062144892.68814397366601.667449817
#Sta/Elev= 30
       0 2221.47   134.1 2147.51   201.7 2105.49   235.5 2087.54   253.4 2074.95
   265.4 2071.17   303.9 2051.14   325.3 2044.64   371.7 2020.16   388.8 2008.03
   412.6 1996.64   458.6 1961.87   471.4 1944.09   487.6 1928.42   504.5 1926.99
  520.851915.868   545.6 1905.69   561.1 1907.51  573.271916.849   579.7 1920.53
   627.2  1922.4   676.7 1931.51   786.6  1968.3   933.8 2030.85  1073.1  2099.4
  1108.9  2121.7  1221.8 2200.39  1235.7 2205.01  1245.4 2213.37  1261.2 2221.93
#Mann= 5 ,-1 , 0
       0      .1       0  515.66     .06       0  520.85    .045       0
  573.27     .06       0  650.46      .1       0
Bank Sta=520.85,573.27
XS Rating Curve= 0 ,0
Exp/Cntr=0.5,0.3

Type RM Length L Ch R = 1 ,42227   ,52.2,54.7,73.3
XS GIS Cut Line= 6
2145716.35217905365244.9582209742145270.51875314 365586.62486048
 2145216.3521948365675.5137903092145180.24104655365781.069353476
2145049.03724071366018.0137614762144649.73160888366363.499619067
#Sta/Elev= 30
       0 2241.58    30.2 2243.38    56.9 2239.06   147.9 2201.69   205.7  2160.3
   238.8 2144.27   313.2 2089.44   329.7 2083.77   412.4 2025.52   426.8 2011.53
   466.1  1990.1   491.2 1968.85   507.6  1960.3   540.6 1928.54   556.7  1920.4
   578.1 1920.26  603.981913.766   642.6 1908.83  694.481912.881   755.6 1921.05
   820.5 1925.16   847.6  1934.4  1005.1 1971.18  1082.8 2000.34  1176.1 2048.47
    1219 2074.71  1414.3 2171.78  1453.3  2196.3  1470.7 2200.79  1576.2 2264.45
#Mann= 6 ,-1 , 0
       0      .1       0   578.1     .06       0  603.98    .045       0
  694.48      .1       0   755.6     .06       0   847.6      .1       0
#XS Ineff= 2 , 0
          583.98  1922.7  714.48          1922.7
Permanent Ineff=
       F       F
Bank Sta=603.98,694.48
XS Rating Curve= 0 ,0
Exp/Cntr=0.5,0.3

Type RM Length L Ch R = 1 ,42172   ,507.2,530.2,553
XS GIS Cut Line= 6
2145700.07891764365196.8329891412145248.69005664365538.847068891
2145177.50942472365639.5414213092145116.74576671365761.069065392
2144969.17617998365910.3748691382144595.91216272366278.430235401
#Sta/Elev= 30
       0 2212.76    29.5 2218.79    69.5 2217.97   102.1 2210.79   145.6 2194.48
     238 2138.76   287.1 2101.35   336.8  2076.4   386.2 2041.43   423.2 2010.75
   468.5 1989.42   480.8  1975.5   504.1 1961.35   542.6 1922.27   589.4 1921.44
     615 1912.83     669 1909.41  683.151911.741   707.5 1910.21   766.2 1923.56
   817.8 1923.79   841.4 1930.21   909.6 1954.33  1055.6 2018.84  1175.4    2084
  1242.5 2114.78  1385.8 2201.81  1399.6 2204.72  1485.5 2249.97  1559.6  2303.3
#Mann= 6 ,-1 , 0
       0      .1       0   562.1     .06       0     615    .045       0
  683.15      .1       0  705.38     .06       0  861.52      .1       0
Bank Sta=615,683.15
XS Rating Curve= 0 ,0
Exp/Cntr=0.5,0.3

Type RM Length L Ch R = 1 ,41642   ,818.5,823.1,822.1
XS GIS Cut Line= 2
2145594.67886597364973.681204483 2144451.6234093365252.847968981
#Sta/Elev= 30
       0  2064.1    22.6 2064.15    39.5 2059.23    90.1 2054.31   157.7 2036.69
   211.7 2026.54   302.9 2000.12   319.8 1994.29   377.2 1967.81     415 1942.33
   454.9 1920.83   485.3 1919.71   502.2 1913.08   573.1 1914.15  583.41 1911.15
   595.8 1907.04   613.6 1906.29   633.9 1907.61  642.411912.619   658.2 1917.35
   701.7 1919.29   789.2 1935.67   833.1 1947.82   854.8 1950.34   924.3 1966.51
  1008.4 1989.33    1076 2005.08  1089.9 2006.64  1143.8 2035.24  1176.7  2048.6
#Mann= 5 ,-1 , 0
       0      .1       0  429.63     .06       0  529.27      .1       0
  583.41    .045       0  642.41      .1       0
Bank Sta=583.41,642.41
XS Rating Curve= 0 ,0
Exp/Cntr=0.3,0.1

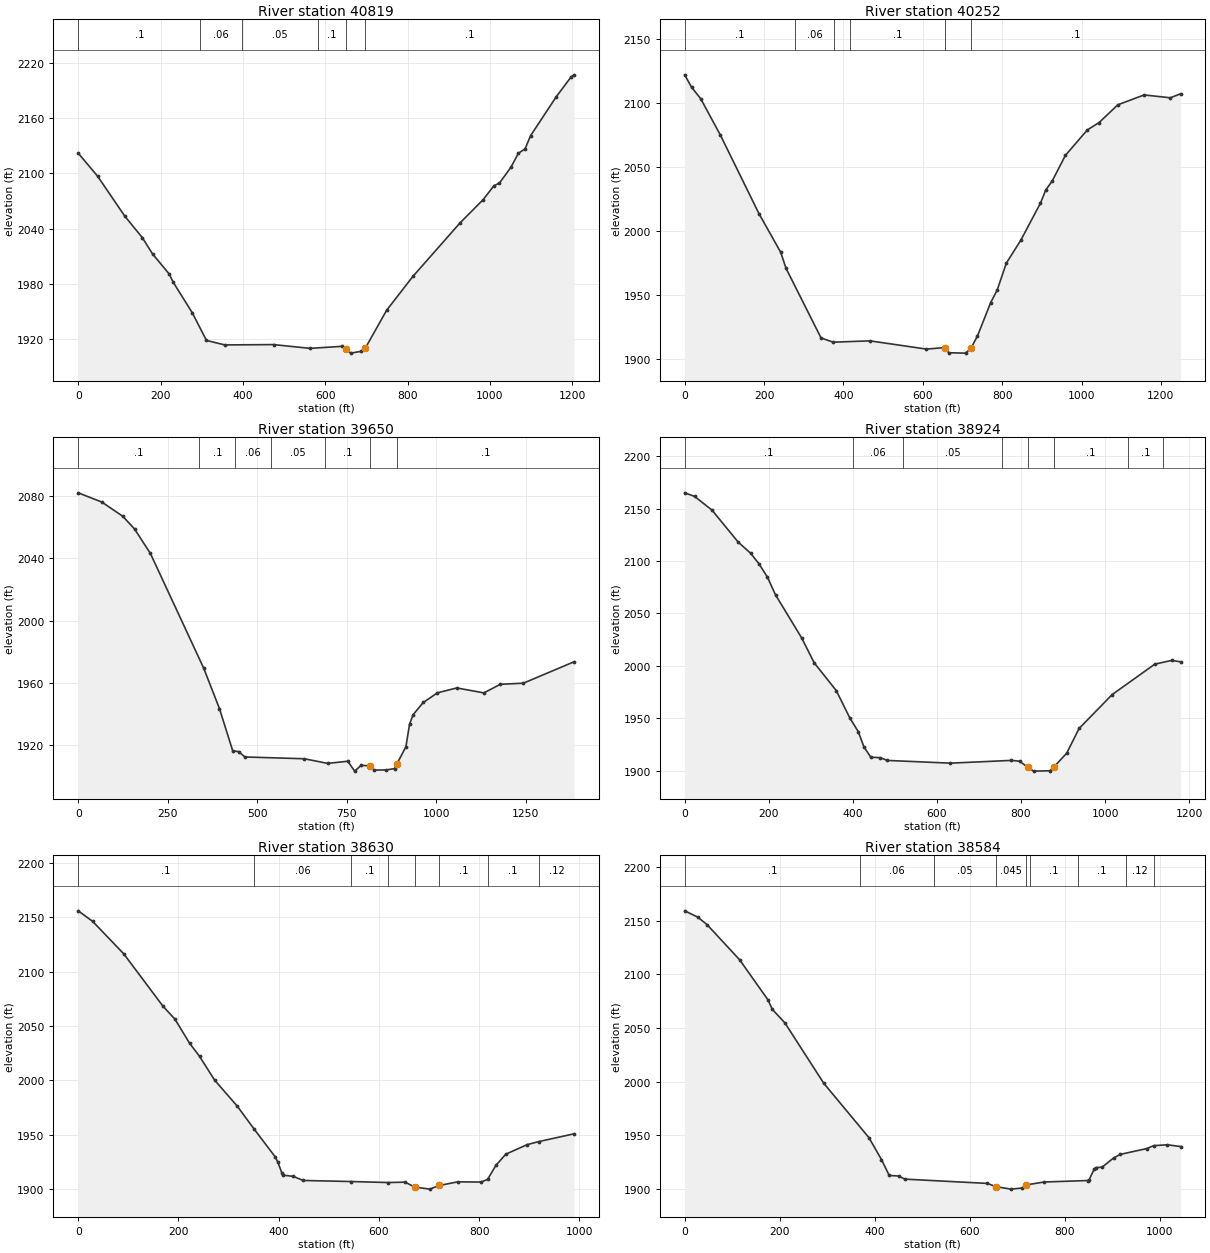
Type RM Length L Ch R = 1 ,40819   ,566,566.3,564.6
XS GIS Cut Line= 2
2145265.51220147  364397.29226542144062.73573564364461.247518063
#Sta/Elev= 30
       0 2122.11    47.2    2097   112.9  2053.8   155.6 2030.37   180.5 2012.65
   221.3 1990.63   230.4  1982.1   277.2 1948.57   311.5 1918.65     356 1913.77
   474.3 1914.14     563 1910.03   641.8 1912.27  651.331909.546   661.6 1904.86
   687.8 1906.85  697.161910.164     749 1951.39   812.7 1988.13   927.7  2046.5
   983.5  2071.6  1009.8 2086.76    1023 2089.53  1050.9  2106.7    1069 2121.91
  1085.4 2126.81  1098.5 2140.99  1160.9 2183.25  1197.1 2204.94  1204.5 2207.18
#Mann= 6 ,-1 , 0
       0      .1       0  296.74     .06       0  396.65     .05       0
  581.52      .1       0  651.33    .045       0  697.16      .1       0
Bank Sta=651.33,697.16
XS Rating Curve= 0 ,0
Exp/Cntr=0.3,0.1

Type RM Length L Ch R = 1 ,40252   ,606.4,602.7,599
XS GIS Cut Line= 2
2145150.23454489363800.0700346382143909.95651364363952.847944304
#Sta/Elev= 30
       0 2121.75    17.3 2112.09    40.4 2103.13      90 2074.75   187.3 2013.45
     242 1983.39   255.3 1970.95   343.6 1916.62   374.3 1913.28   466.8 1914.32
     609  1907.9  655.991909.075   665.2 1905.04   708.1 1904.75  721.581908.731
   737.8 1918.12   770.9 1944.04   787.5 1953.96   810.6 1974.97     847  1992.8
   896.6 2021.75   909.8  2031.9   926.3 2039.09   959.4 2058.96  1014.6 2078.77
  1044.1 2084.49  1091.6  2098.4  1157.7 2106.07  1223.8 2103.85  1249.7 2106.97
#Mann= 6 ,-1 , 0
       0      .1       0  277.08     .06       0  376.49     .05       0
  416.26      .1       0  655.99    .045       0  721.58      .1       0
Bank Sta=655.99,721.58
XS Rating Curve= 0 ,0
Exp/Cntr=0.3,0.1

Type RM Length L Ch R = 1 ,39650   ,716.4,725.6,729.1
XS GIS Cut Line= 3
2145098.84554005363104.2367806432143999.93664864363383.056761056
2143778.01222372363502.847860053
#Sta/Elev= 30
       0 2082.07    66.2 2076.12   124.7 2066.99   157.6 2058.81   201.6 2043.19
   350.5 1969.59   394.7 1943.52   431.8 1916.41   448.7 1915.91   465.6 1912.47
   632.2 1911.32     697 1908.34   753.3 1909.73   772.6 1903.38   790.5 1907.06
  815.891906.818   826.6 1904.06   861.5 1904.15   884.2 1905.03  891.26 1908.27
   915.8 1919.09   925.9 1933.49   936.1 1939.69   964.3 1947.45  1003.8 1953.65
  1057.9 1956.79  1133.6  1953.6  1179.6 1959.13  1244.1 1959.85  1385.9 1973.62
#Mann= 7 ,-1 , 0
       0      .1       0   338.9      .1       0  438.61     .06       0
  538.32     .05       0  688.54      .1       0  815.89    .045       0
  891.26      .1       0
Bank Sta=815.89,891.26
XS Rating Curve= 0 ,0
Exp/Cntr=0.3,0.1

Type RM Length L Ch R = 1 ,38924   ,291.9,293.7,295.3
XS GIS Cut Line= 2
2144912.73436372362612.570113063 2143733.5677588362638.958839804
#Sta/Elev= 30
       0 2164.96    23.5 2161.59      65 2148.48   127.4 2117.95     157 2107.33
   176.7  2097.3   196.8 2084.62     216 2067.74   278.4 2026.58   307.9 2003.04
   360.5 1976.52   393.2 1950.09   412.9 1937.39   426.1 1923.02   442.5 1913.04
   465.4 1912.54   481.9 1909.94   632.2 1907.34   777.2 1909.98   796.7 1909.18
  815.791903.421   829.7 1899.74   869.1 1900.09  878.041903.709   908.5 1916.79
     938 1940.39  1016.8 1972.72    1118 2001.67  1157.9 2005.23  1179.5 2003.94
#Mann= 8 ,-1 , 0
       0      .1       0  401.04     .06       0  519.76     .05       0
   753.6      .1       0  815.79    .045       0  878.04      .1       0
 1053.56      .1       0 1137.48     .12       0
Bank Sta=815.79,878.04
XS Rating Curve= 0 ,0
Exp/Cntr=0.5,0.3

Type RM Length L Ch R = 1 ,38630   ,47,46.4,47.2
XS GIS Cut Line= 5
2144745.21796647362351.3468822242144083.75964372362342.666453391
2144002.16236597362337.4581304792143797.30122714362356.555205137
2143760.84296672362373.916390896
#Sta/Elev= 30
       0 2156.09    28.8 2146.39    91.1 2116.35   169.1 2068.26   192.8 2056.45
   222.3 2034.08   242.1 2022.04   272.2 2000.15   317.5  1976.1   350.3 1955.49
     393 1929.51   398.6 1924.34   406.1 1914.81   409.4 1912.65   429.1 1911.54
   448.8 1907.78   543.9  1906.8   617.5 1905.88   652.2 1906.21  671.331901.695
   701.5  1899.8  720.381903.171   757.2 1906.52   803.5 1906.32   816.7 1908.72
   833.2 1921.62     853 1931.98   895.7 1940.78   918.9 1943.59   989.4 1950.75
#Mann= 8 ,-1 , 0
       0      .1       0   350.3     .06       0   543.9      .1       0
   617.5     .05       0  671.33    .045       0  720.38      .1       0
   816.7      .1       0   918.9     .12       0
#XS Ineff= 2 , 0
          655.33  1901.8  736.38          1901.8
Permanent Ineff=
       F       F
Bank Sta=671.33,720.38
XS Rating Curve= 0 ,0
Exp/Cntr=0.5,0.3

Type RM Length L Ch R = 1 ,38584   ,485.3,474.4,459.7
XS GIS Cut Line= 5
2144746.95385538362307.9440818882144127.16244406362302.735758975
2144034.96315339362292.1107802242143901.52575623362286.416565895
2143713.15769464362348.048332393
#Sta/Elev= 30
       0 2159.39    27.2 2153.59    46.9  2146.6   115.8 2113.64   174.9  2076.6
   184.7 2067.33     211 2054.81     293 1998.35   388.1  1947.6   414.4  1927.2
   430.8 1912.33   450.5 1911.86   463.6 1908.92   637.6 1904.91  655.021901.914
   687.1 1899.58   710.3 1900.58  719.141903.518   757.1 1906.23   848.3  1907.6
   851.8 1908.52   862.1 1917.93   865.6  1919.7   878.7 1919.97   903.5 1928.74
   917.3    1932   972.6  1937.4     988 1940.18  1016.6 1940.97  1044.4 1939.33
#Mann= 9 ,-1 , 0
       0      .1       0  369.51     .06       0  524.43     .05       0
  655.02    .045       0  719.14     .05       0  726.39      .1       0
  827.81      .1       0  928.51     .12       0  987.95     .05       0
Bank Sta=655.02,719.14
XS Rating Curve= 0 ,0
Exp/Cntr=0.5,0.3

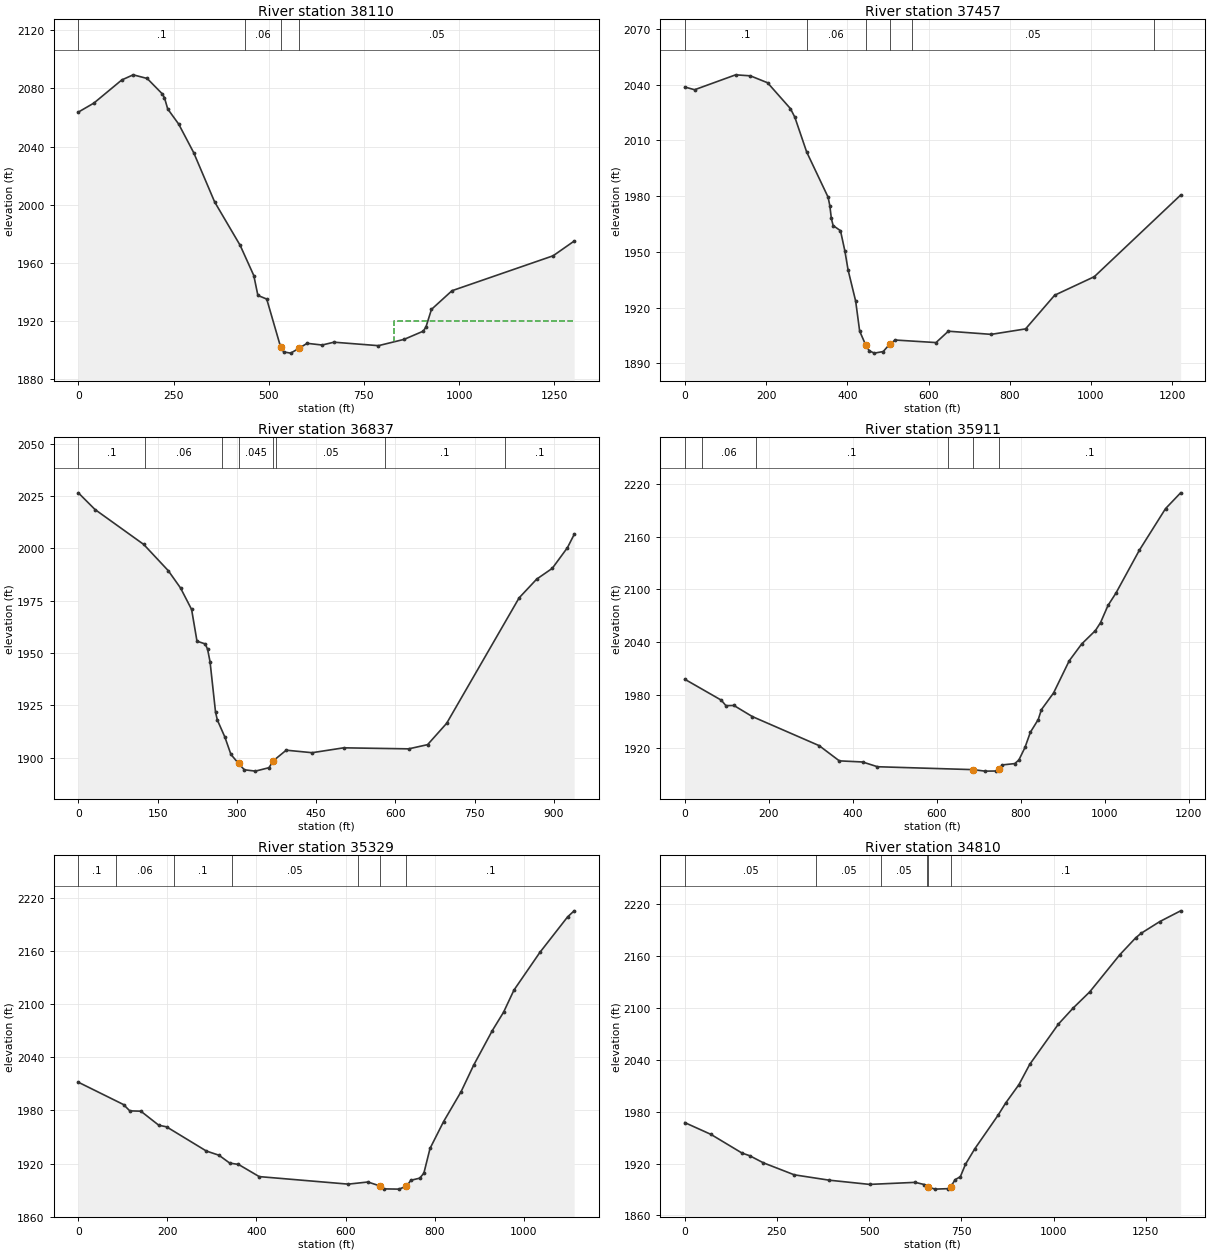
Type RM Length L Ch R = 1 ,38110   ,652.1,652.4,647
XS GIS Cut Line= 2
2144612.73430756361608.4034862222143422.45650439362136.181302056
#Sta/Elev= 30
       0 2063.74    40.9 2069.97   114.2  2085.9   144.1 2089.41   180.8  2086.9
   220.3 2076.34   226.1 2073.72   234.7 2065.91   263.5  2055.5   302.9 2035.84
   357.9 2001.91   424.9 1972.03   460.8 1951.18   471.5 1937.53   494.7 1935.02
  531.311901.918   539.4  1898.6   557.7 1897.79  580.511901.283   600.7 1904.54
   640.2 1903.37   671.2 1905.32   788.1 1902.93   855.6 1907.28   905.8 1912.92
     913 1915.92   927.3 1927.91   981.2 1940.76  1246.8 1964.82    1302 1974.94
#Mann= 4 ,-1 , 0
       0      .1       0  436.76     .06       0  531.31    .045       0
  580.51     .05       0
#XS Ineff= 2 , 0
                          829.54         1920.04
Permanent Ineff=
       F       F
Bank Sta=531.31,580.51
XS Rating Curve= 0 ,0
Exp/Cntr=0.3,0.1

Type RM Length L Ch R = 1 ,37457   ,625.1,620.1,611.6
XS GIS Cut Line= 2
2144248.84559964361020.9033488932143178.01211138361607.014381394
#Sta/Elev= 30
       0 2038.75    24.2 2037.29   125.2 2045.31   161.4 2044.77   203.8 2041.04
   259.9 2027.17   270.8 2022.57     300 2003.81   352.8 1979.46   357.1 1974.84
   360.8 1968.01   365.2 1964.19   383.3 1961.43   394.2 1950.41     402 1940.31
   420.7 1923.49   430.5 1907.38   445.11900.052   454.3 1896.76   466.7 1895.54
   488.5 1896.39  504.011900.265   517.9 1902.59   618.5 1901.22   648.8 1907.34
   754.4 1905.64     839 1908.58   910.6 1926.71  1008.2 1936.68  1220.7  1980.6
#Mann= 6 ,-1 , 0
       0      .1       0  299.79     .06       0   445.1    .045       0
  504.01      .1       0  559.55     .05       0 1155.74      .1       0
Bank Sta=445.1,504.01
XS Rating Curve= 0 ,0
Exp/Cntr=0.3,0.1

Type RM Length L Ch R = 1 ,36837   ,883.6,926.2,959.6
XS GIS Cut Line= 5
2143637.73428905360602.8477545532143403.62583339360810.618008316
 2143389.3420693360824.6169960652143375.05830522360838.616311893
 2142915.5123083361201.459090143
#Sta/Elev= 30
       0 2026.58    31.6  2018.6   123.8  2001.9   170.3 1989.34   193.5 1981.07
   214.4 1970.82   224.6 1955.66     240 1954.36   244.6 1951.86   249.3 1945.85
   259.7 1921.72   263.2 1917.92   277.3 1909.86   288.8 1901.53  303.231897.199
   314.3 1894.17   335.2 1893.53   360.8 1895.17  369.371898.558   393.5 1903.54
   442.5 1902.34   502.2 1904.67   625.3 1904.18   661.1 1906.19   697.2 1916.41
   834.3 1976.36   867.5 1985.31   897.1 1990.48   925.8 2000.38   938.5 2006.67
#Mann= 8 ,-1 , 0
       0      .1       0  126.68     .06       0   272.3      .1       0
  303.23    .045       0  369.37      .1       0  374.84     .05       0
  580.12      .1       0  807.04      .1       0
Bank Sta=303.23,369.37
XS Rating Curve= 0 ,0
Exp/Cntr=0.3,0.1

Type RM Length L Ch R = 1 ,35911   ,567.5,582.2,580.9
XS GIS Cut Line= 2
2143533.56783073360418.1256830542142486.34551573359872.292457148
#Sta/Elev= 30
       0 1997.76    86.8 1973.98    97.9 1967.71     117  1967.9   160.8 1955.28
   319.9 1922.19     368 1904.85   423.5 1903.56   458.9 1898.15   685.6 1894.86
   715.3 1893.15   741.7 1893.27  747.931896.047   756.5 1900.23   785.8 1901.73
   795.6 1905.75   810.2 1920.09     823 1937.38   841.8 1951.92   849.3 1963.14
   878.3 1982.17   915.5 2018.73   945.1 2037.84     978 2053.22   990.1 2062.19
    1008 2081.84  1026.8 2095.81  1082.5 2144.58  1144.9 2191.99  1180.9 2210.01
#Mann= 6 ,-1 , 0
       0      .1       0    40.8     .06       0  169.45      .1       0
   626.9     .05       0   685.6    .045       0  747.93      .1       0
Bank Sta=685.6,747.93
XS Rating Curve= 0 ,0
Exp/Cntr=0.3,0.1

Type RM Length L Ch R = 1 ,35329   ,515.1,518.2,521.5
XS GIS Cut Line= 2
2143750.23439214360137.5701418072142911.34564997 359405.62573956
#Sta/Elev= 30
       0 2011.84   101.5  1986.6   115.5  1979.5   140.4 1979.13   180.7 1963.25
   198.1 1961.46   287.5 1934.12   315.7 1929.41     340 1920.48   359.6    1919
   406.1 1905.25   606.1 1896.74   650.2 1899.15  677.811894.588   685.8 1891.38
     720  1891.1  736.751894.416   746.7 1901.08   766.5  1903.5   775.8 1909.04
   789.7 1937.09     820 1967.27   859.5 2001.24   887.4 2030.84   929.6 2070.21
   954.8 2090.92   978.1 2115.87  1036.2 2158.37  1098.5 2198.53  1113.3 2205.41
#Mann= 7 ,-1 , 0
       0      .1       0    84.8     .06       0  214.48      .1       0
  345.17     .05       0  627.02      .1       0  677.81    .045       0
  736.75      .1       0
Bank Sta=677.81,736.75
XS Rating Curve= 0 ,0
Exp/Cntr=0.3,0.1

Type RM Length L Ch R = 1 ,34810   ,603.7,606.8,609.3
XS GIS Cut Line= 2
2144053.68260413359815.0228866492143141.25693555358827.570137143
#Sta/Elev= 30
       0 1967.26    70.7  1953.7   155.1 1932.09     176 1929.01   213.2 1920.78
   296.8 1906.95   391.5 1900.75   501.1 1895.87   624.6 1898.23   649.7 1895.69
  659.111893.092   678.2 1890.41   714.7 1890.96  721.421893.409   733.2 1901.42
   747.2 1904.72   761.1 1919.15   786.6 1937.18   849.3 1975.69   870.1  1989.9
     906 2011.13   935.2 2034.48  1013.2 2081.15  1053.4 2099.78  1098.1 2118.33
  1179.5 2161.19    1223 2180.89  1237.5 2186.02  1288.1 2199.56  1344.5 2211.95
#Mann= 6 ,-1 , 0
       0     .05       0   355.5     .05       0  532.88     .05       0
     656      .1       0  659.11    .045       0  721.42      .1       0
Bank Sta=659.11,721.42
XS Rating Curve= 0 ,0
Exp/Cntr=0.3,0.1

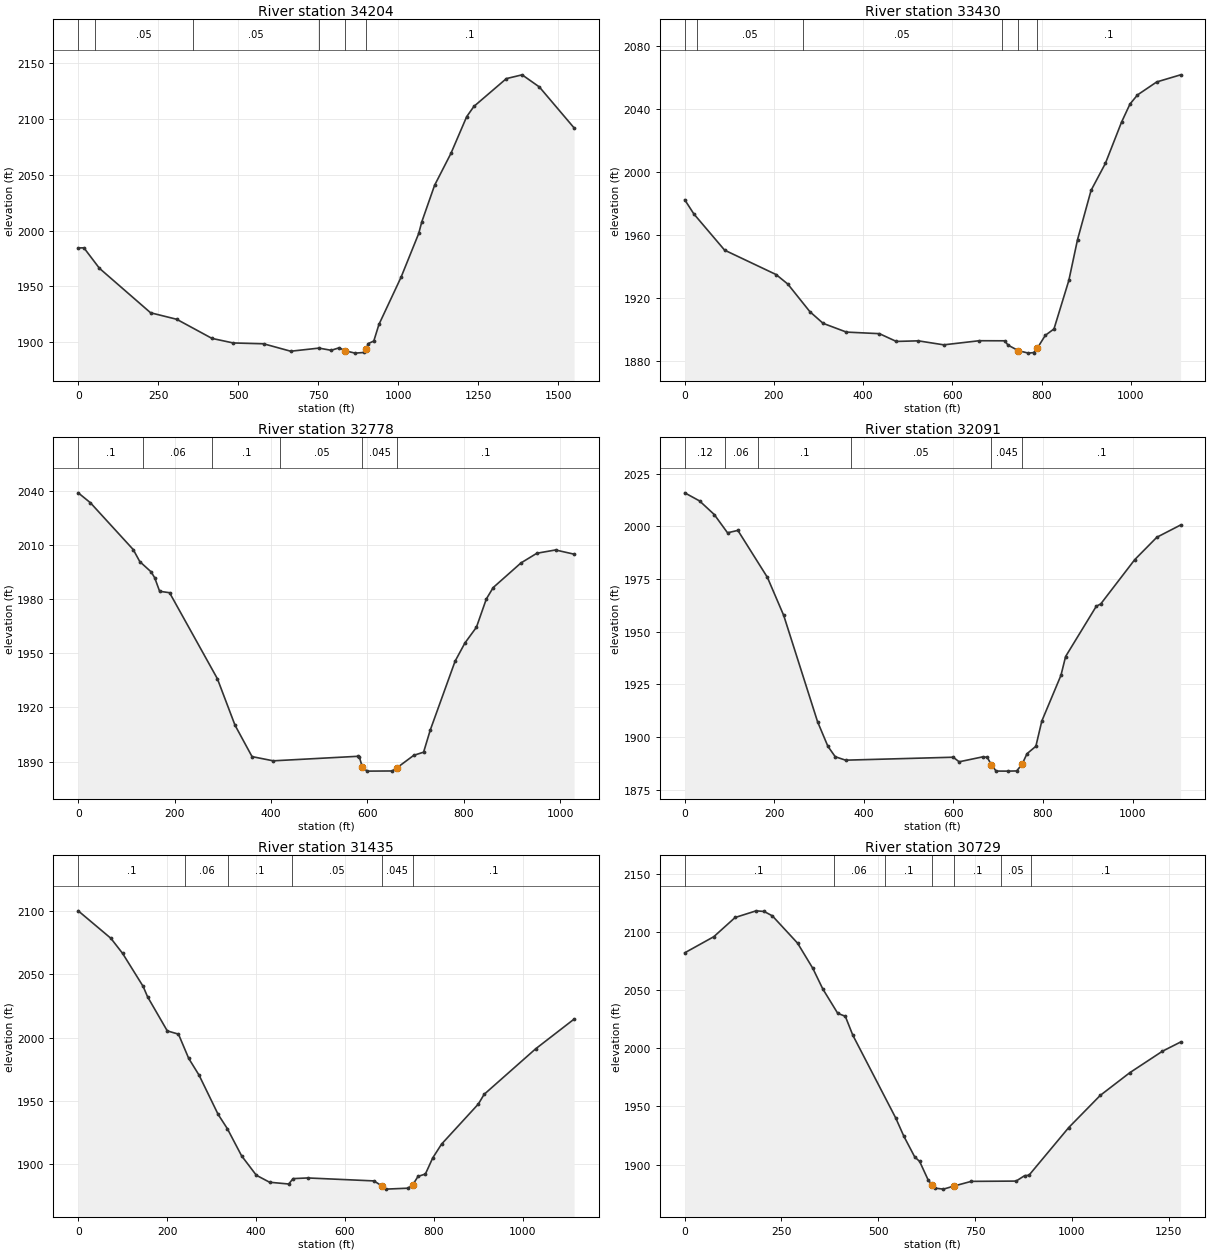
Type RM Length L Ch R = 1 ,34204   ,734,773.5,799.4
XS GIS Cut Line= 3
2144547.45655097359663.9588843142144378.94999821 359347.32008189
2143652.81332713358404.034238815
#Sta/Elev= 30
       0 1984.48    17.8 1984.59    66.3 1966.26   226.2 1926.44   307.6 1920.65
   417.8 1903.53     484 1899.45   579.5 1898.68   663.8 1892.04     752 1894.84
   790.4 1892.87   815.2 1895.11  834.191892.433     865 1890.34   893.9 1890.95
  899.781894.317   906.3  1898.9   923.4 1901.18   939.4 1915.98  1008.6 1958.31
  1063.7 1997.43  1073.2 2007.74  1113.3 2040.56  1164.4 2069.15  1213.5 2101.95
  1236.1 2111.16  1337.5 2136.06  1386.7 2139.44  1440.5 2128.61  1549.1 2091.94
#Mann= 6 ,-1 , 0
       0    .055       0    52.9     .05       0  359.51     .05       0
  752.13      .1       0  834.19    .045       0  899.78      .1       0
Bank Sta=834.19,899.78
XS Rating Curve= 0 ,0
Exp/Cntr=0.3,0.1

Type RM Length L Ch R = 1 ,33430   ,660.4,652,643.1
XS GIS Cut Line= 3
2144554.40109089359638.9589343072144519.67871939359236.181196556
2144875.23443872358625.070214063
#Sta/Elev= 30
       0 1982.35    20.5 1973.36    89.4 1950.43   204.7 1934.98     231 1928.95
   280.4 1911.47   310.1 1904.06   362.3 1898.52   436.3 1897.52   474.1  1892.6
   523.4 1892.98   580.5 1890.44   660.1 1893.05     717    1893   724.6 1890.25
  747.961886.724   770.2 1885.19   781.9 1885.53  790.511888.518   808.1 1896.47
   827.5 1900.51   860.8 1931.27   880.2 1957.03   910.6 1988.31   942.7 2005.41
   978.9 2031.54   997.8    2043  1014.6 2048.78  1057.8 2057.02  1111.3 2061.52
#Mann= 6 ,-1 , 0
       0    .055       0    26.4     .05       0  264.85     .05       0
  710.28      .1       0  747.96    .045       0  790.51      .1       0
Bank Sta=747.96,790.51
XS Rating Curve= 0 ,0
Exp/Cntr=0.3,0.1

Type RM Length L Ch R = 1 ,32778   ,693.7,687.4,679.6
XS GIS Cut Line= 2
2145080.79012997359852.8479422332145373.84564622358866.736725479
#Sta/Elev= 30
       0 2038.95    25.2 2033.47   114.2 2007.49   127.8 2000.82   151.2 1995.16
   158.7 1991.87   168.9 1984.39   189.5  1983.6   288.7 1935.95   325.3 1910.17
   360.6 1892.78   404.5 1890.44   579.6 1892.94   583.1 1892.61  589.721886.755
   599.7 1884.73   651.5 1884.82   661.8 1886.68     696 1893.47   716.5 1895.24
   730.2 1907.39   781.8 1945.63   802.1 1955.68   826.1 1964.47   846.6 1980.11
   860.9 1986.46   918.5  2000.1   951.6 2005.48   990.2 2007.28  1028.7 2004.96
#Mann= 6 ,-1 , 0
       0      .1       0     134     .06       0  278.56      .1       0
  419.28     .05       0  589.72    .045       0   661.8      .1       0
Bank Sta=589.72,661.8
XS Rating Curve= 0 ,0
Exp/Cntr=0.3,0.1

Type RM Length L Ch R = 1 ,32091   ,660.8,655.8,646.1
XS GIS Cut Line= 2
 2145868.2898673 360094.514453652145966.90121864358991.736803561
#Sta/Elev= 30
       0 2015.92      33 2012.09    65.9 2005.62    95.6 1996.94   118.6 1998.09
   184.5 1975.81     221 1957.71   296.5 1907.31   319.6 1895.61     336 1890.65
   359.1 1889.01   599.5 1890.41   612.7 1888.24   665.4 1890.59   675.3 1890.39
  684.621886.866   695.2 1883.84   721.4 1883.81   741.2  1883.9  753.41 1887.15
   764.2 1892.08     784 1895.61   797.2 1907.55     840 1929.28   850.4 1938.22
   918.9 1962.07   928.9 1963.19  1004.7 1984.19  1054.1 1994.83  1107.2 2000.65
#Mann= 6 ,-1 , 0
       0     .12       0   89.91     .06       0  162.67      .1       0
  371.43     .05       0  684.62    .045       0  753.41      .1       0
Bank Sta=684.62,753.41
XS Rating Curve= 0 ,0
Exp/Cntr=0.3,0.1

Type RM Length L Ch R = 1 ,31435   ,720.4,705.8,686.8
XS GIS Cut Line= 2
2146665.51235422360118.1256268922146525.23441955359011.181318477
#Sta/Elev= 30
       0 2100.31    73.4 2078.62    99.9 2066.64   146.2 2040.48   156.1 2032.31
   200.4 2005.38   225.6 2002.79   248.7 1983.57   271.9 1970.39   314.9  1939.3
   335.5  1928.1   367.7 1906.54   400.8 1891.22   430.6 1885.69   473.6 1884.29
   483.5 1888.55   516.6 1889.08   665.4 1886.74  683.881882.641   691.9 1880.24
   741.5 1880.97  752.591883.557   764.6  1890.3   781.2 1892.18   797.7 1904.91
   817.5  1915.8   900.2 1947.47   913.4 1955.19  1029.2 1991.16  1115.8 2014.68
#Mann= 6 ,-1 , 0
       0      .1       0   239.8     .06       0  337.35      .1       0
  481.83     .05       0  683.88    .045       0  752.59      .1       0
Bank Sta=683.88,752.59
XS Rating Curve= 0 ,0
Exp/Cntr=0.3,0.1

Type RM Length L Ch R = 1 ,30729   ,728.4,703.5,674
XS GIS Cut Line= 2
2147642.37129289359754.8445293162146808.56784239358782.014453977
#Sta/Elev= 30
       0 2082.11    75.2 2095.99   130.2 2112.48   184.5 2118.21   205.2 2117.66
   226.4 2113.88   291.6  2090.4   331.1 2068.66   356.7 2051.05   395.3 2030.09
   414.9 2027.52   434.2 2011.33   545.2 1940.06   566.1 1924.44   594.1 1906.68
     607 1902.68   628.9 1886.84  638.99 1882.37   645.9 1879.79   668.5 1878.91
   694.7 1881.47   740.2 1885.58   856.2 1885.83   877.9 1890.42   889.5 1890.86
   992.3  1931.9  1073.7 1959.53  1150.1 1979.05  1234.3 1997.49  1281.3 2005.41
#Mann= 7 ,-1 , 0
       0      .1       0  384.38     .06       0   516.2      .1       0
  638.99    .045       0   694.7      .1       0  816.96     .05       0
   895.7      .1       0
Bank Sta=638.99,694.7
XS Rating Curve= 0 ,0
Exp/Cntr=0.3,0.1

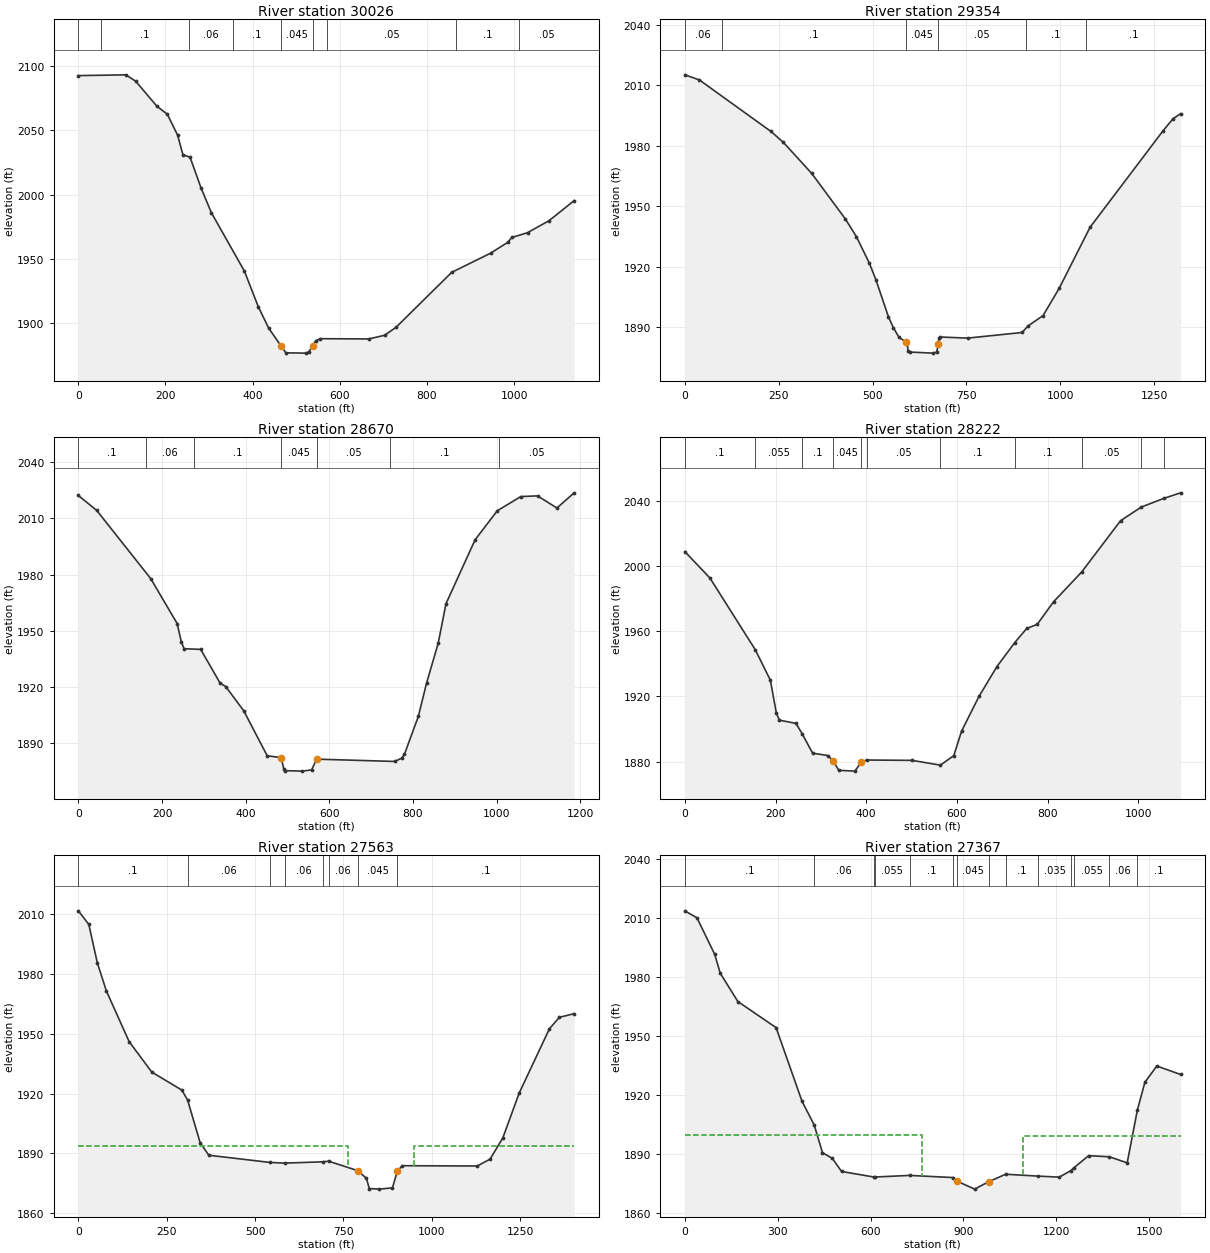
Type RM Length L Ch R = 1 ,30026   ,667.9,671.6,675.2
XS GIS Cut Line= 2
2148014.12317406358672.2922324842146876.62348056 358643.12562415
#Sta/Elev= 30
       0 2092.54   108.8 2093.15   131.7 2088.18   180.6 2068.64   204.2 2062.58
   227.8 2046.32     240 2031.09   256.4 2029.14   281.6 2005.31   305.2 1986.12
   381.2 1940.61     413 1912.99   436.9 1896.33  465.641882.295   476.3 1877.18
   522.3 1876.94   528.8 1877.89  537.791882.607   545.2 1886.59   555.1 1888.16
   666.7 1887.96   702.8 1890.81     729 1896.97     857 1939.74   946.1 1954.58
     985 1962.91   994.9 1966.78    1031 1970.53  1080.5 1979.89  1137.9 1995.43
#Mann= 9 ,-1 , 0
       0     .05       0   52.13      .1       0  254.29     .06       0
  355.37      .1       0  465.64    .045       0  537.79      .1       0
  571.53     .05       0  867.27      .1       0 1011.23     .05       0
Bank Sta=465.64,537.79
XS Rating Curve= 0 ,0
Exp/Cntr=0.3,0.1

Type RM Length L Ch R = 1 ,29354   ,679.6,684.2,683.5
XS GIS Cut Line= 2
2148058.56763896 358048.681274982146743.29008581357934.792395145
#Sta/Elev= 30
       0  2015.1    38.5  2012.6   229.5 1987.02   262.4 1981.62   338.1 1966.19
   427.1 1943.76   456.7 1934.93   491.4 1921.74   509.4 1913.19   542.3 1895.11
   555.5 1889.64   570.5 1884.93  589.671882.496   591.7 1881.85     595 1878.17
   598.3 1877.66   660.9 1877.12   670.8 1877.68  674.841881.753   677.3 1884.64
   680.6  1885.1   753.1 1884.57     898 1887.35   914.4 1890.65     954 1895.76
   996.8 1909.24  1079.1 1939.54  1273.5 1987.38  1299.7 1993.29  1320.2 1995.84
#Mann= 6 ,-1 , 0
       0     .06       0   98.02      .1       0  589.67    .045       0
  674.84     .05       0  908.86      .1       0 1068.56      .1       0
Bank Sta=589.67,674.84
XS Rating Curve= 0 ,0
Exp/Cntr=0.3,0.1

Type RM Length L Ch R = 1 ,28670   ,445,448.1,447.4
XS GIS Cut Line= 2
2147939.12332405357397.2921578142146765.51215422357232.014601231
#Sta/Elev= 30
       0  2022.2      44 2014.22   173.2 1977.84   236.2 1953.93   246.1 1944.25
   252.7 1940.51   292.5 1940.15   338.9 1922.17   352.4 1920.32   395.5 1907.38
   451.5 1883.42  484.551882.493   491.3 1876.36   494.6  1875.5   534.9 1875.25
   557.5  1875.9  569.681881.634   756.3 1880.41   772.9 1882.18   779.5 1884.21
   812.7 1904.42   832.5 1922.24   860.2 1943.41   878.9 1964.55   948.5 1998.61
  1001.5 2014.07  1057.6 2021.61  1097.6 2021.99    1144 2015.52  1185.2 2023.61
#Mann= 7 ,-1 , 0
       0      .1       0  161.11     .06       0  276.56      .1       0
  484.55    .045       0  569.68     .05       0  745.37      .1       0
 1005.94     .05       0
Bank Sta=484.55,569.68
XS Rating Curve= 0 ,0
Exp/Cntr=0.3,0.1

Type RM Length L Ch R = 1 ,28222   ,656.5,659,691.9
XS GIS Cut Line= 3
2147828.94408247356946.6037547292147351.16616663356866.048141554
2146742.83273764356846.603626639
#Sta/Elev= 30
       0 2009.02    55.5 1992.72   155.4 1948.69   188.6 1930.02   201.9 1909.75
   208.6 1905.43   245.2 1903.44   258.5  1897.2   281.8 1885.17   315.1 1883.69
  327.38 1880.33   339.4 1874.62   374.9 1874.12  389.581879.794   400.9 1880.95
   501.2 1880.72   563.5  1877.8   593.1 1883.65   610.3 1898.75   648.9 1920.14
   688.2 1938.36   727.6 1953.11   753.9 1961.76   776.9 1964.24     813 1978.15
   874.8 1996.36   960.7 2027.94  1006.3 2036.32  1057.2 2041.77  1093.2 2045.08
#Mann= 11 ,-1 , 0
       0      .1       0   155.4    .055       0   258.5      .1       0
  327.38    .045       0  389.58      .1       0   400.9     .05       0
   563.5      .1       0   727.6      .1       0   874.8     .05       0
  1006.3      .1       0  1057.2     .05       0
Bank Sta=327.38,389.58
XS Rating Curve= 0 ,0
Exp/Cntr=0.8,0.6

Type RM Length L Ch R = 1 ,27563   ,164.2,196,191.4
XS GIS Cut Line= 6
2147825.23444422  356876.4588819 2147259.4937778356403.449657306
2147140.51796588356321.296934471 2146976.7679653356189.213537231
2146745.51809973 356168.727357732146667.39292789 356168.72735773
#Sta/Elev= 30
       0 2011.82    29.6 2005.01    53.7 1985.73    79.4 1971.57   143.7 1946.16
   207.7 1930.88   292.8 1921.82   309.1 1916.82   344.5 1895.46     369 1889.12
   541.2 1885.51   583.9 1885.16   690.9 1885.79     708 1886.12   790.7 1881.36
   815.1  1877.5   823.1 1872.38   851.2 1872.09   888.6 1872.72   902.6 1881.17
   902.6 1881.18   902.6 1881.19   916.6 1883.85  1128.5  1883.7  1164.8 1887.15
    1201 1897.85  1247.1 1920.28  1332.7  1952.6  1360.8 1958.35  1402.7  1960.2
#Mann= 8 ,-1 , 0
       0      .1       0   309.1     .06       0   541.2      .1       0
   583.9     .06       0   690.9      .1       0     708     .06       0
   790.7    .045       0   902.6      .1       0
#XS Ineff= 2 , 0
          763.87 1893.58  948.26         1893.58
Permanent Ineff=
       F       F
Bank Sta=790.7,902.6
XS Rating Curve= 0 ,0
Exp/Cntr=0.8,0.6

Type RM Length L Ch R = 1 ,27367   ,657.5,578.9,520.6
XS GIS Cut Line= 6
2147839.59202705 356821.296918722147430.62204447356454.832756639
 2147143.8522768356115.7277918162146964.59213664355987.529557392
2146820.84209606355975.7241348182146593.06433639356059.751853898
#Sta/Elev= 30
       0 2013.86    39.4 2010.28    96.7 1991.68   114.5 1982.12   171.5 1967.68
   294.9 1954.42   378.6 1916.95   418.2 1904.81   444.7 1890.82   476.9 1887.83
   506.3 1881.21     610  1878.4   614.7 1878.39   726.5  1879.2   867.5  1878.1
  880.551876.176   936.5 1872.22  981.141875.979  1036.6  1879.8  1142.4 1878.83
  1209.8 1878.33  1247.1 1881.65  1257.9 1883.22  1304.4 1889.23  1371.3 1888.69
  1429.1  1885.6  1461.8 1912.33  1486.3 1926.63  1524.8 1934.87  1601.7 1930.57
#Mann= 14 ,-1 , 0
       0      .1       0   418.2     .06       0     610      .1       0
   614.7    .055       0   726.5      .1       0   867.5    .055       0
  880.55    .045       0  981.14    .055       0  1036.6      .1       0
  1142.4    .035       0  1247.1      .1       0  1257.9    .055       0
  1371.3     .06       0  1461.8      .1       0
#XS Ineff= 2 , 0
          767.32 1899.93 1093.43         1899.06
Permanent Ineff=
       F       F
Bank Sta=880.55,981.14
XS Rating Curve= 0 ,0
Exp/Cntr=0.8,0.6