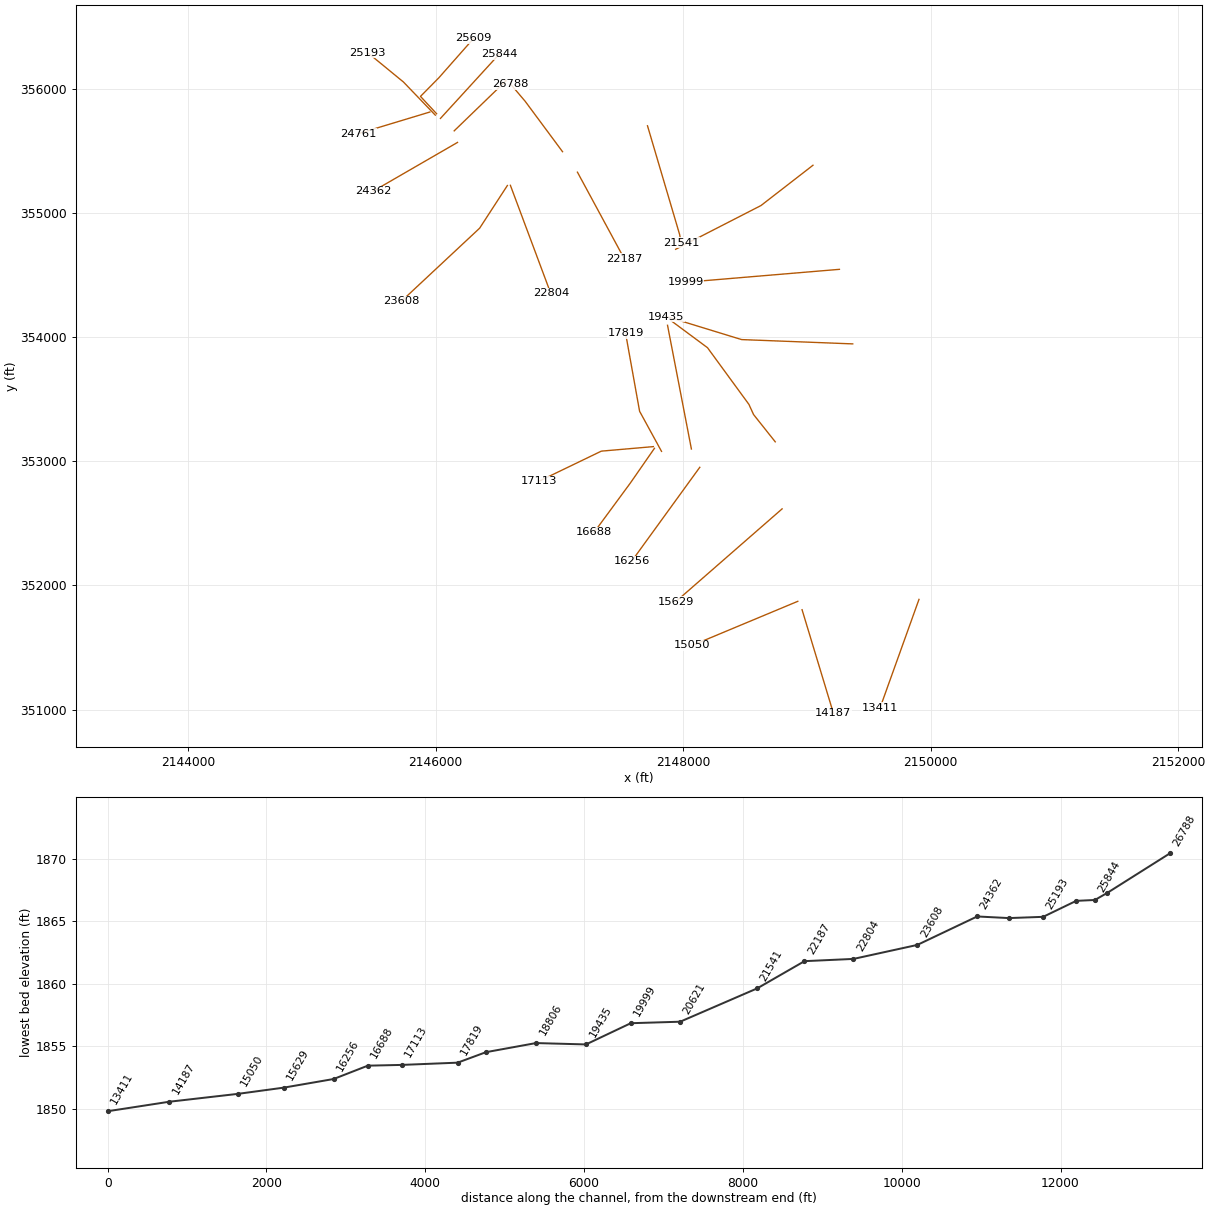
HEC-RAS study SPRINGCK.prj: SPRINGCK

--- SPRINGCK.g01 (geometry) --- (continued)

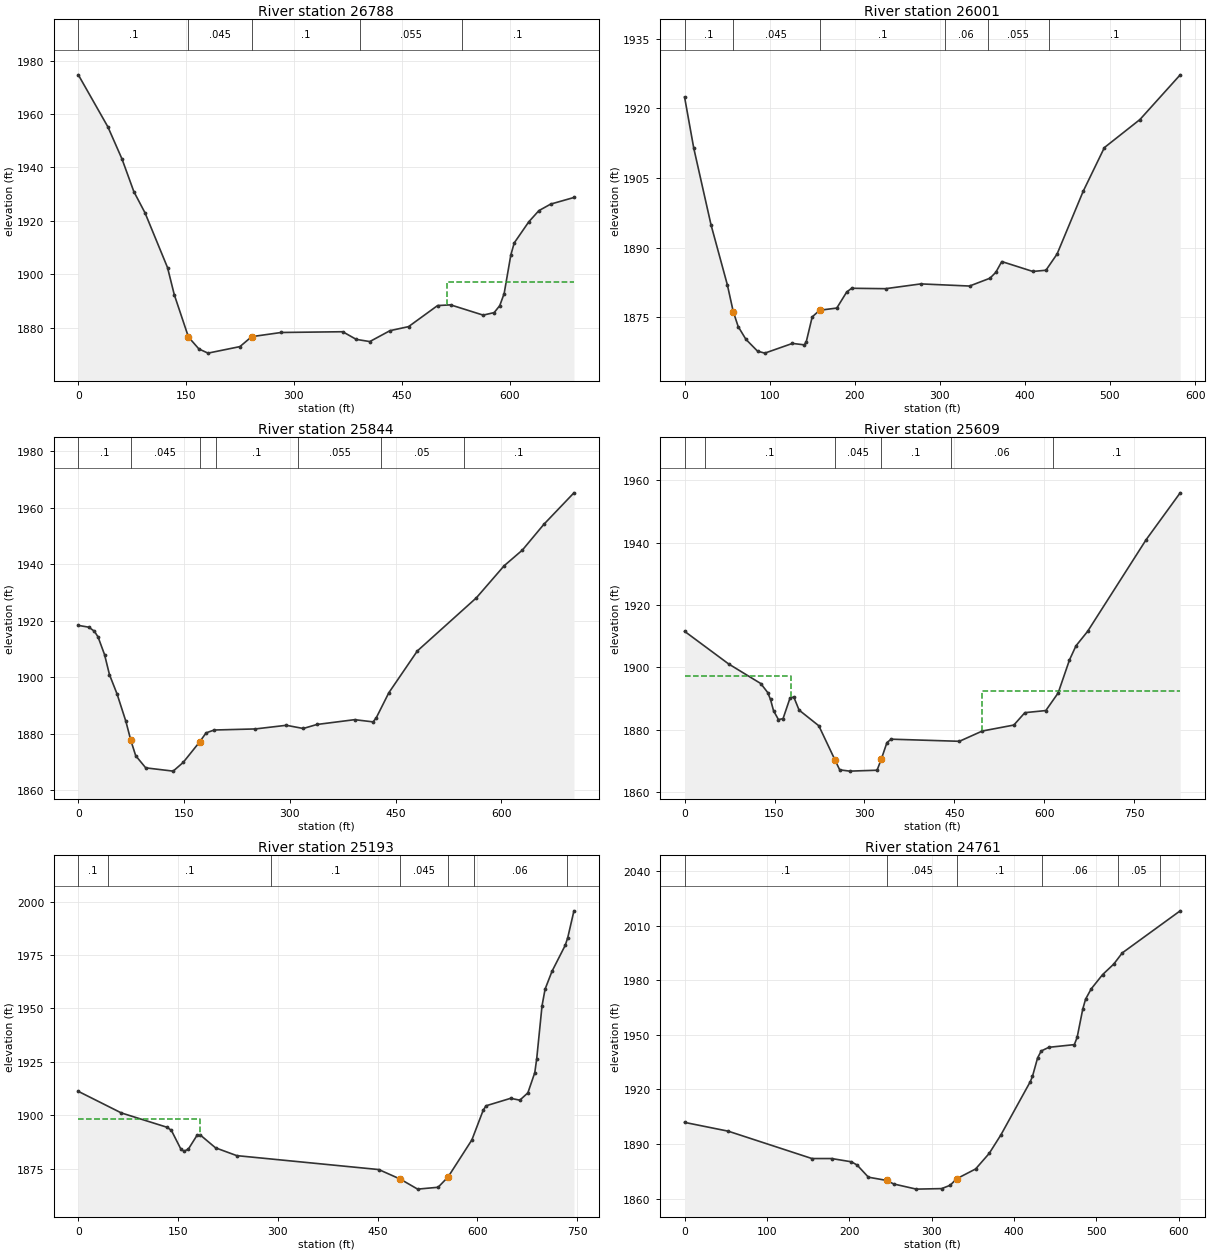
Type RM Length L Ch R = 1 ,26788   ,839.9,787.3,713.8
XS GIS Cut Line= 3
2147025.70323488355494.5781154782146724.31440197355900.133734807
2146604.86975896356040.411669478
#Sta/Elev= 30
       0 1974.64    41.1 1955.17    60.8 1943.11    77.2 1930.95    92.8 1922.96
   124.1 1902.48   133.5 1892.32  153.211876.472   167.8    1872   180.4 1870.45
   224.8 1872.89  241.231876.618   282.2 1878.18   367.8 1878.46   386.7 1875.59
   405.5 1874.78   433.6 1878.86   459.4 1880.37   499.8 1888.26   517.9 1888.52
   563.2 1884.68   578.5 1885.62   586.3 1888.24   592.4 1892.76   601.7  1907.2
   606.4  1911.7   626.7 1919.62   640.7 1923.79   657.1 1926.24   689.5 1928.72
#Mann= 5 ,-1 , 0
       0      .1       0  153.21    .045       0  241.23      .1       0
  392.43    .055       0  533.45      .1       0
#XS Ineff= 2 , 0
                           513.5         1897.11
Permanent Ineff=
       F       F
Bank Sta=153.21,241.23
XS Rating Curve= 0 ,0
Exp/Cntr=0.3,0.1

Type RM Length L Ch R = 1 ,26001   ,153.8,156.2,159.6
XS GIS Cut Line= 2
2146150.70334446355662.6338817332146570.14771555356066.800396234
#Sta/Elev= 30
       0 1922.41    10.8 1911.41    31.1  1894.9    50.3 1881.98    57.2 1876.23
      63 1873.01    72.1 1870.26    85.8 1867.71    94.3 1867.29   126.8 1869.38
   140.8 1869.07   143.1 1869.79     150 1875.08   158.7 1876.52   178.9 1876.99
   190.6 1880.46   196.4 1881.25   236.2 1881.16   277.7 1882.19   334.9 1881.73
   358.9 1883.41   365.8 1884.68   372.8    1887   409.3 1884.87   424.7 1885.13
   437.8 1888.62   468.5 1902.13   493.4 1911.53   535.2 1917.57   582.5 1927.19
#Mann= 7 ,-1 , 0
       0      .1       0    57.2    .045       0   158.7      .1       0
  306.16     .06       0  356.05    .055       0  428.59      .1       0
   582.2      .1       0
Bank Sta=57.2,158.7
XS Rating Curve= 0 ,0
Exp/Cntr=0.3,0.1

Type RM Length L Ch R = 1 ,25844   ,237,235.2,233.5
XS GIS Cut Line= 2
2146039.59201814355762.6336817292146514.59205239356280.689404145
#Sta/Elev= 30
       0 1918.33    14.9 1917.69    22.8 1916.25      28 1914.23    37.2 1907.97
    44.2 1900.87      55    1894    67.5  1884.3    74.4 1877.66    81.4 1872.17
    95.6 1867.88   134.5 1866.72   148.7  1869.8   171.9 1877.01   181.2 1880.27
   192.7 1881.28     251 1881.66     295 1882.95     319 1881.82   338.4 1883.24
   391.8 1884.94   418.1 1884.16   422.7 1885.69   440.3 1894.45   480.8 1909.28
   564.4 1928.06   603.9 1939.44   629.7 1944.98   660.3 1954.14   702.9 1965.27
#Mann= 7 ,-1 , 0
       0      .1       0    74.4    .045       0   171.9      .1       0
   194.8      .1       0  311.96    .055       0  429.12     .05       0
  546.28      .1       0
Bank Sta=74.4,171.9
XS Rating Curve= 0 ,0
Exp/Cntr=0.3,0.1

Type RM Length L Ch R = 1 ,25609   ,351.2,416.4,477.1
XS GIS Cut Line= 4
2146008.51563673355800.2002076512145878.30723572355939.957145974
2146026.74493097356090.1307301372146307.99469656356407.839084223
#Sta/Elev= 30
       0 1911.56    73.6 1901.06     127 1894.79   138.7 1891.88   143.3 1889.67
   148.4 1886.04   156.5 1883.22   164.2 1883.49   175.8  1890.1   182.1 1890.47
     191 1886.25   223.9 1881.21     251 1870.17   258.7 1867.06   275.4 1866.65
     321 1866.94   328.3 1870.62   337.5 1875.83   344.5 1876.91   458.3 1876.23
   496.5 1879.53   549.1 1881.45   567.5 1885.43   602.4  1886.1     623 1891.76
   641.9 1902.37   652.7 1906.89   672.1 1911.53   769.7 1940.98   826.5 1956.03
#Mann= 6 ,-1 , 0
       0      .1       0   34.54      .1       0     251    .045       0
   328.3      .1       0  444.39     .06       0  613.87      .1       0
#XS Ineff= 2 , 0
          178.27 1897.19  495.56         1892.37
Permanent Ineff=
       F       F
Bank Sta=251,328.3
XS Rating Curve= 0 ,0
Exp/Cntr=0.3,0.1

Type RM Length L Ch R = 1 ,25193   ,396.3,431.5,466.9
XS GIS Cut Line= 3
 2145997.9254348355789.0227365642145740.98106681356055.689197972
2145450.70310405356293.189379141
#Sta/Elev= 30
       0 1911.17    64.7 1901.06   133.5 1894.34     140 1892.87   154.1  1884.2
   158.9 1883.14   165.4 1884.08   178.4 1890.52   183.1 1890.81   206.4 1884.71
   238.3 1881.06     452 1874.53  484.461870.023   510.3 1865.37   541.1 1866.24
  556.211871.116   591.9 1888.43   608.8 1902.23   613.1  1904.4   650.2 1907.91
     664 1907.04   676.1 1910.47   686.5 1919.93   689.4 1926.44   697.4 1951.24
     702 1959.06   712.4 1967.41   732.4 1979.65   736.1  1983.2   745.4 1995.73
#Mann= 7 ,-1 , 0
       0      .1       0   44.76      .1       0  289.76      .1       0
  484.46    .045       0  556.21    .055       0  594.53     .06       0
  734.23     .05       0
#XS Ineff= 2 , 0
          182.91 1898.17
Permanent Ineff=
       F       F
Bank Sta=484.46,556.21
XS Rating Curve= 0 ,0
Exp/Cntr=0.3,0.1

Type RM Length L Ch R = 1 ,24761   ,387.4,399.3,408.9
XS GIS Cut Line= 2
2145953.82808205355814.0892874752145377.43914297355640.478086144
#Sta/Elev= 30
       0 1901.93    53.1 1897.09   154.7 1882.07   178.7 1882.07   202.7 1880.27
   209.6 1878.49   223.3 1871.82  245.371870.062   254.1 1868.09   281.5 1865.27
   312.3 1865.56   322.6 1867.39  330.43 1870.94   353.5 1876.34     370 1884.88
   384.3 1895.12     420 1924.36   422.6 1927.24   428.8 1937.35   433.2 1941.15
   442.5 1943.16   473.4 1944.63   476.8 1948.56   483.7 1964.24   487.1 1969.62
   493.9 1975.25   507.7 1983.06   521.4 1988.92   531.6 1994.99     602 2018.12
#Mann= 6 ,-1 , 0
       0      .1       0  245.37    .045       0  330.43      .1       0
  434.14     .06       0  525.91     .05       0  577.61     .06       0
Bank Sta=245.37,330.43
XS Rating Curve= 0 ,0
Exp/Cntr=0.3,0.1

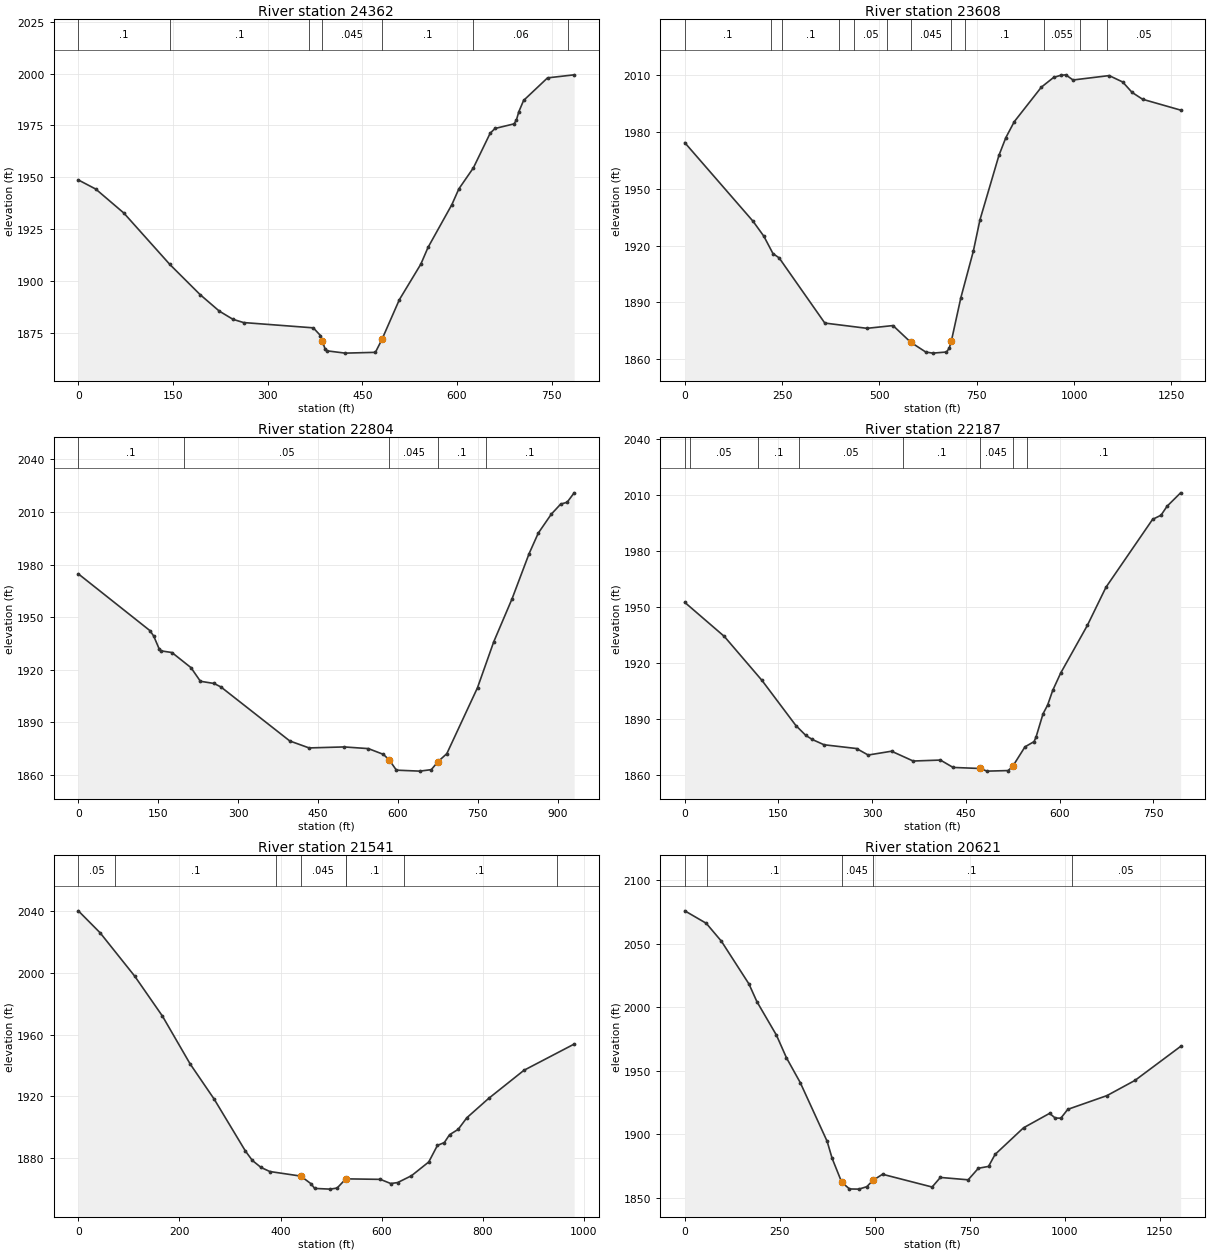
Type RM Length L Ch R = 1 ,24362   ,736.3,754.1,760.7
XS GIS Cut Line= 2
2146177.38865855355569.2252758892145496.83326113355176.864183977
#Sta/Elev= 30
       0 1948.78    27.6 1944.39    72.1 1932.85     145 1908.09   193.1 1893.53
   223.4 1885.62     245 1881.68   261.8 1880.12   372.3 1877.57   383.6 1873.88
  386.231871.477   391.2 1867.22     394  1866.5   422.8  1865.4   470.7 1865.78
  481.151872.067   508.6 1891.11   542.7 1908.26     554 1916.26   591.9 1936.94
   602.9 1944.47     626 1954.64   652.5 1971.26   660.1 1973.55   690.4 1975.78
   694.2 1977.75   697.9 1981.61   705.5 1987.06   743.4 1997.92   785.6 1999.39
#Mann= 7 ,-1 , 0
       0      .1       0  144.48      .1       0  365.51      .1       0
  386.23    .045       0  481.15      .1       0  625.85     .06       0
  775.76     .05       0
Bank Sta=386.23,481.15
XS Rating Curve= 0 ,0
Exp/Cntr=0.3,0.1

Type RM Length L Ch R = 1 ,23608   ,721.2,803.8,842.9
XS GIS Cut Line= 3
2146580.16639631355222.002873227 2146356.2081828354878.252904564
2145724.26358056354289.711430728
#Sta/Elev= 30
       0 1974.36   175.3 1932.83   203.1 1924.91   226.6 1915.71   242.3 1913.48
   359.7 1879.01   468.1 1876.23   534.9 1877.69  580.371868.884     619  1863.7
     637 1863.12   672.3 1863.71   679.3 1865.72  685.041869.735   709.2 1892.41
   741.2 1916.96   758.2 1933.51     807 1967.63   824.7 1976.99   846.4 1985.45
     916  2003.7   947.4 2008.82   965.3 2009.96   978.8 2010.22   997.3 2007.49
  1090.2 2009.82    1125 2006.43  1149.1 2000.93  1176.1 1997.31  1273.8 1991.57
#Mann= 12 ,-1 , 0
       0      .1       0  220.29      .1       0  249.64      .1       0
  397.01      .1       0  435.76     .05       0  518.94      .1       0
  580.37    .045       0  685.04      .1       0  719.78      .1       0
  921.72    .055       0 1015.16    .035       0  1083.7     .05       0
Bank Sta=580.37,685.04
XS Rating Curve= 0 ,0
Exp/Cntr=0.3,0.1

Type RM Length L Ch R = 1 ,22804   ,611.7,616.9,621.6
XS GIS Cut Line= 2
2146604.47212197355223.7390902342146930.86090489354352.211305723
#Sta/Elev= 30
       0 1974.66   134.5 1942.22   141.5 1939.11     152 1931.61   155.5 1930.67
   175.7 1929.73   211.4 1921.11   229.1 1913.32   254.7 1912.06   267.6 1910.08
   396.9 1879.22   433.1 1875.25   498.9 1875.82   544.4 1874.86   572.4 1871.59
  583.291868.486     597 1862.55     641    1862   662.5 1862.85  675.04 1867.42
   691.6 1871.98   749.2 1909.66   779.7 1935.89   814.2 1960.54     846 1986.19
   863.2 1997.91   887.7 2008.76   905.3  2014.5   917.4 2015.55   930.6 2020.94
#Mann= 5 ,-1 , 0
       0      .1       0  197.94     .05       0  583.29    .045       0
  675.04      .1       0  764.49      .1       0
Bank Sta=583.29,675.04
XS Rating Curve= 0 ,0
Exp/Cntr=0.3,0.1

Type RM Length L Ch R = 1 ,22187   ,602.6,595.6,587.5
XS GIS Cut Line= 2
2147146.13868955355329.6417655652147524.61102971354631.725182399
#Sta/Elev= 30
       0 1952.31    63.2 1934.08   123.7 1910.42   177.9 1886.25   193.8 1880.96
   204.1  1878.8   222.9 1875.96     275 1873.94   293.6 1870.45     331  1872.5
   365.7 1867.24   409.3 1867.75   429.6  1863.8  472.421863.236     484 1861.82
   517.6 1862.12  524.911864.315   544.7 1874.85   559.2 1877.64   562.4 1880.08
   573.6 1892.57     581 1897.28   589.1 1905.11   601.7 1914.31   644.5 1939.93
   674.3 1960.39     749 1996.83   762.5 1999.05   772.2 2003.87   793.9 2011.06
#Mann= 8 ,-1 , 0
       0      .1       0    8.63     .05       0  117.05      .1       0
  183.25     .05       0  349.12      .1       0  472.42    .045       0
  524.91      .1       0  547.59      .1       0
Bank Sta=472.42,524.91
XS Rating Curve= 0 ,0
Exp/Cntr=0.3,0.1

Type RM Length L Ch R = 1 ,21541   ,999.3,970.4,906.8
XS GIS Cut Line= 3
2147712.11388521355703.3669251722147971.57474013354827.552690143
2147983.71203377354761.317431363
#Sta/Elev= 30
       0 2040.29    43.1 2026.03   111.5  1997.9   166.3    1972     221    1941
   268.9 1917.96   330.5 1884.38   344.2 1878.27   361.3 1873.73   378.8 1871.07
     440  1868.1   460.5 1863.07   467.4  1860.1   498.2 1859.64   511.9 1860.34
     529 1866.25   529.3 1866.31   597.4 1865.98   617.9 1863.29   631.6 1863.89
     659 1868.34   693.2 1877.28   710.3 1888.01     724 1889.88   734.3 1894.95
   751.4 1898.44   768.5 1905.97   811.7 1918.54   881.4 1936.76   980.8 1953.79
#Mann= 8 ,-1 , 0
       0     .05       0   72.74      .1       0  390.17     .05       0
     440    .045       0     529    .045       0   529.3      .1       0
  643.52      .1       0  946.21     .05       0
Bank Sta=440,529
XS Rating Curve= 0 ,0
Exp/Cntr=0.3,0.1

Type RM Length L Ch R = 1 ,20621   ,642.3,621.9,595.1
XS GIS Cut Line= 3
2149048.91638005355385.1974287332148628.77745655355060.544534728
2147939.54130222354708.114137232
#Sta/Elev= 30
       0 2075.84    56.5 2066.03    96.3 2051.96   168.8 2018.35   189.8 2004.41
   241.3 1978.02   267.6 1960.26   303.8  1940.8   374.6 1894.61   387.8 1881.18
  412.971862.429   433.5 1857.11   458.3 1856.97   479.1 1858.89  494.911863.803
   520.5 1868.66     651 1858.63   672.7 1866.16   745.9  1864.3   772.7 1873.37
   799.5 1874.84   816.7 1884.25   891.6  1905.2   960.2 1916.56   974.9  1912.9
   989.7 1912.75  1008.1 1919.71  1111.3 1930.53    1185 1942.48  1305.1 1969.23
#Mann= 5 ,-1 , 0
       0     .05       0   59.08      .1       0  412.97    .045       0
  494.91      .1       0 1018.06     .05       0
Bank Sta=412.97,494.91
XS Rating Curve= 0 ,0
Exp/Cntr=0.3,0.1

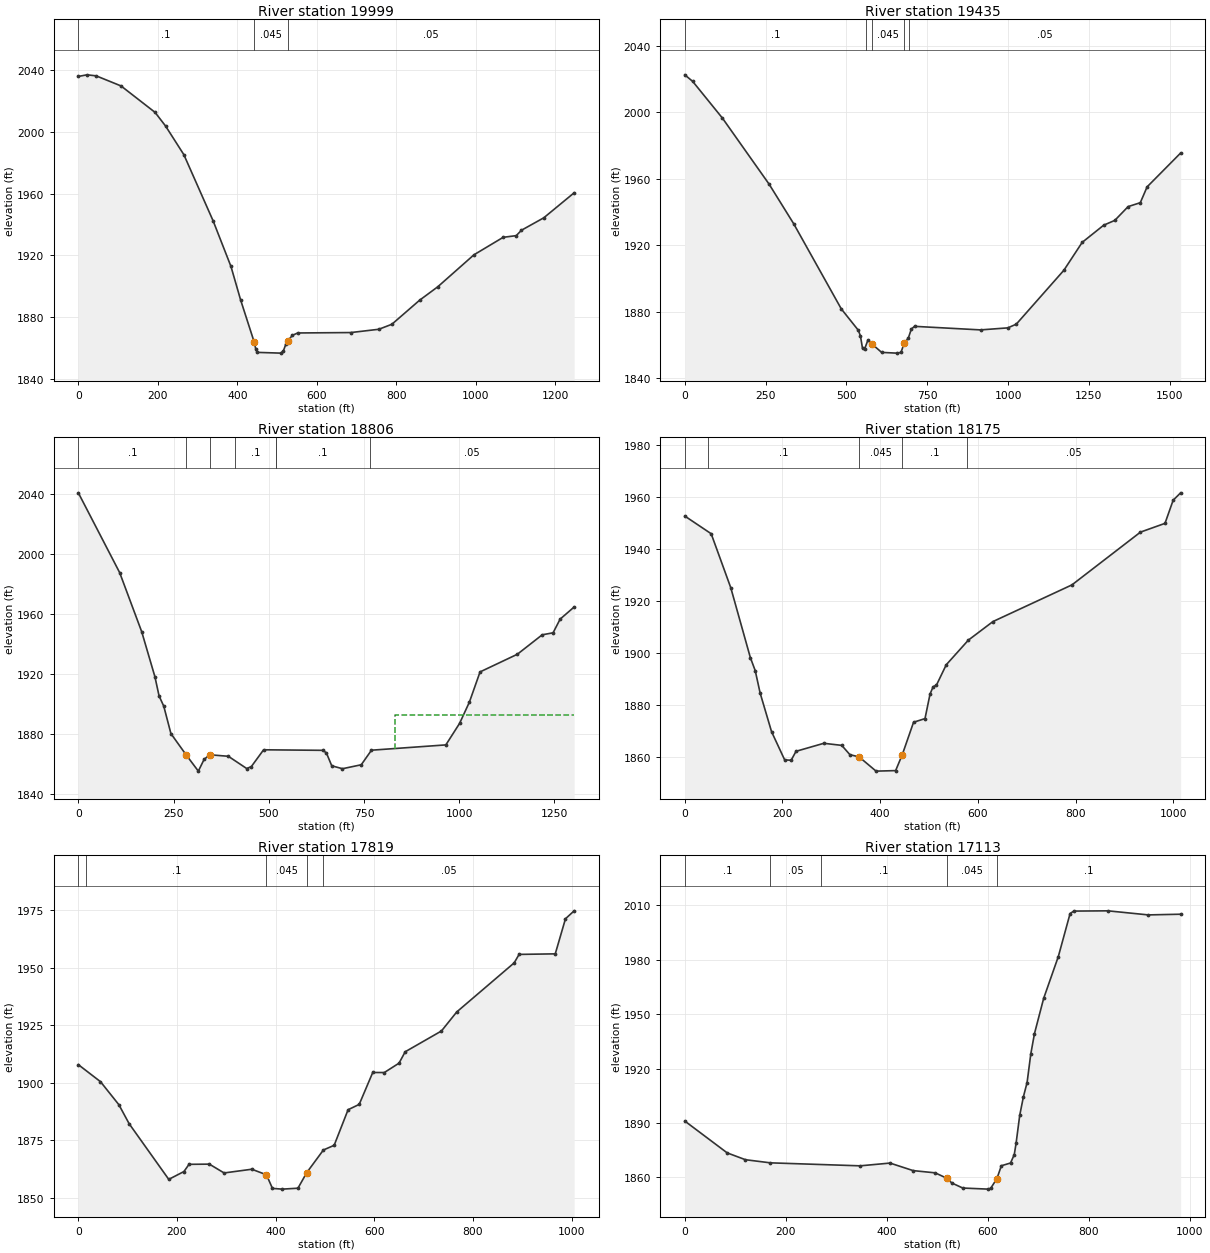
Type RM Length L Ch R = 1 ,19999   ,556.1,564.2,552.4
XS GIS Cut Line= 2
2149262.45794772354546.6557987332148019.40269105354442.489012316
#Sta/Elev= 30
       0 2035.71    21.8 2036.75    44.9 2036.09   107.4 2029.57     193 2012.49
   219.4 2003.68   265.5 1985.13   339.2  1942.3     384 1912.87   408.2 1891.29
     442 1864.35   446.5 1859.44   449.8 1857.34   509.1 1856.85   515.7 1858.18
   522.3  1862.8  527.121864.854   538.7 1868.38   551.9 1869.88   685.5 1870.15
     756 1872.27   788.8 1875.51   858.6 1891.06   904.2 1899.72   995.3 1920.41
  1068.8 1931.71  1101.7  1932.8  1114.9  1936.3  1170.9 1944.31  1247.4  1960.5
#Mann= 3 ,-1 , 0
       0      .1       0     442    .045       0  527.12     .05       0
Bank Sta=442,527.12
XS Rating Curve= 0 ,0
Exp/Cntr=0.3,0.1

Type RM Length L Ch R = 1 ,19435   ,668.8,629,594.9
XS GIS Cut Line= 3
2149370.09684005353945.9611339722148472.52744097353980.683505476
2147864.88856439 354166.44724156
#Sta/Elev= 30
       0 2022.53    24.4 2018.58   116.4 1996.49   260.8 1956.76   336.7    1933
   484.1 1881.73   536.6 1868.93   543.2 1865.52   549.7 1857.97   556.3  1857.7
   566.2 1862.89  580.251860.405   608.8  1855.6   654.8 1855.15   668.6 1855.54
   678.61861.143   691.2 1864.12   700.8 1869.65   710.6 1871.26   914.9 1869.12
     999 1870.34  1025.3 1872.57  1172.4 1904.96  1229.1 1921.76  1295.7  1932.1
    1330 1934.99  1371.2 1943.27  1408.9 1945.63  1429.9 1955.14  1533.6  1975.5
#Mann= 5 ,-1 , 0
       0      .1       0  561.57      .1       0  580.25    .045       0
   678.6      .1       0  693.51     .05       0
Bank Sta=580.25,678.6
XS Rating Curve= 0 ,0
Exp/Cntr=0.3,0.1

Type RM Length L Ch R = 1 ,18806   ,613.3,630.5,615.3
XS GIS Cut Line= 5
2148744.04592681353157.0493259732148569.04594871353376.493768975
2148531.54602373  353458.43815892148196.93973756353915.197415978
2147903.53678106354132.211417645
#Sta/Elev= 30
       0 2040.73   108.5 1987.57   166.4 1948.16   201.1 1918.15     212 1905.36
   224.3 1898.57   243.1 1880.27   283.91865.804   315.1 1855.26   330.2 1863.07
  345.051866.151   393.8 1865.16   442.1    1857   454.2 1858.28   486.5 1869.48
     642 1869.12   651.3 1867.43   665.4 1858.81   693.6 1856.87   742.9  1859.5
   769.7 1869.21     965 1872.74  1001.1 1887.09  1026.9 1901.31  1054.8 1921.38
  1152.7 1933.14    1218 1946.11  1246.6 1947.45    1265 1956.54  1301.9 1964.65
#Mann= 7 ,-1 , 0
       0      .1       0   283.9    .045       0  345.05      .1       0
  412.32      .1       0  519.17      .1       0  519.43      .1       0
  766.52     .05       0
#XS Ineff= 2 , 0
                          831.13         1892.96
Permanent Ineff=
       F       F
Bank Sta=283.9,345.05
XS Rating Curve= 0 ,0
Exp/Cntr=0.3,0.1

Type RM Length L Ch R = 1 ,18175   ,356.9,356.7,355.7
XS GIS Cut Line= 2
2148066.73133655 353099.225294652147874.02306056354095.752829149
#Sta/Elev= 30
       0 1952.69      54 1945.89    94.1 1925.12   134.2 1898.22   144.2 1893.19
   154.2 1884.59   177.6 1869.71   204.4 1858.87   217.7 1858.71   227.7 1862.16
   284.6 1865.24   321.3 1864.44     338 1860.86  356.88    1860   391.5 1854.53
   431.6 1854.73  445.291860.904   468.3 1873.34   491.7 1874.74   502.1 1884.24
   508.4    1887   515.1 1887.61   535.2 1895.46   580.5 1904.95   630.9  1912.1
   792.5  1926.2   932.8 1946.51     983 1949.88   999.7 1958.78    1015 1961.63
#Mann= 5 ,-1 , 0
       0      .1       0   47.92      .1       0  356.88    .045       0
  445.29      .1       0  578.47     .05       0
Bank Sta=356.88,445.29
XS Rating Curve= 0 ,0
Exp/Cntr=0.3,0.1

Type RM Length L Ch R = 1 ,17819   ,600.1,705.7,774
XS GIS Cut Line= 3
2147825.41193731353080.1278918982147648.32863006353403.044568896
2147535.48108672 354029.78084822
#Sta/Elev= 30
       0 1907.88    44.9 1900.47    82.2 1890.44   102.9  1882.2   183.3 1857.94
   214.1 1861.35   224.4 1864.49   265.6 1864.57   295.5 1860.73   351.6 1862.35
  381.351859.942   393.5    1854   413.5 1853.69   445.2 1854.09  462.991860.876
   496.8 1870.73   518.6 1872.77   546.8 1888.25   569.4 1890.59   596.8 1904.47
   620.3 1904.45   650.1 1908.53   662.6 1913.49   736.1 1922.54   767.1 1930.83
   883.5 1952.19   893.5 1955.88   966.8 1956.12   987.5  1971.4  1005.1 1974.85
#Mann= 5 ,-1 , 0
       0      .1       0   15.86      .1       0  381.35    .045       0
  462.99      .1       0  496.89     .05       0
Bank Sta=381.35,462.99
XS Rating Curve= 0 ,0
Exp/Cntr=0.3,0.1

Type RM Length L Ch R = 1 ,17113   ,395.6,425.3,444.6
XS GIS Cut Line= 3
 2147759.4396283353118.3223693072147339.30070481 353081.86410889
2146834.09239763352838.808492646
#Sta/Elev= 30
       0 1891.06      84  1873.5   120.2 1869.73   169.6 1868.01   347.5 1866.36
   406.6 1867.88   452.5 1863.72   496.2 1862.49  520.071859.375   528.9 1856.91
   550.8 1854.11   601.2 1853.51   606.1 1853.98  618.43 1859.33   627.2  1866.4
   645.4 1867.92   652.8 1872.55   656.4 1878.82   663.6 1894.22   670.9 1904.45
   678.2 1912.31   685.5 1928.02   692.8 1939.27     711 1958.71   740.1 1981.81
   763.4 2005.53   770.8 2006.88   838.4 2007.02   918.3 2004.77   982.4 2005.15
#Mann= 5 ,-1 , 0
       0      .1       0  168.29     .05       0  270.25      .1       0
  520.07    .045       0  618.43      .1       0
Bank Sta=520.07,618.43
XS Rating Curve= 0 ,0
Exp/Cntr=0.3,0.1

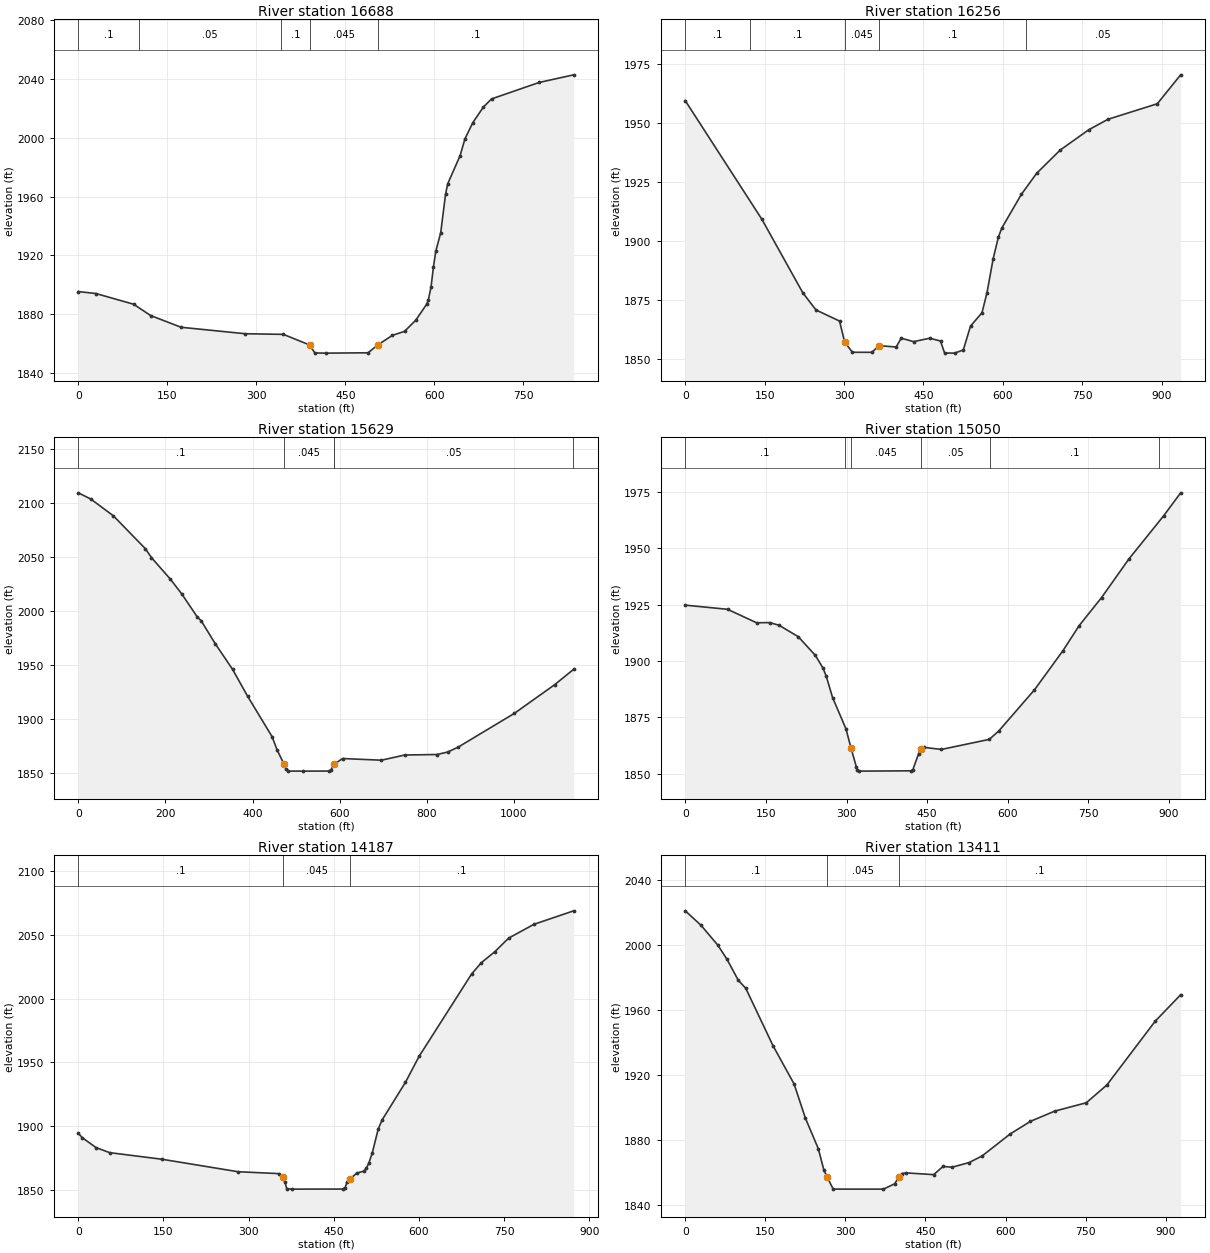
Type RM Length L Ch R = 1 ,16688   ,428.8,431.3,455.7
XS GIS Cut Line= 3
2147768.12005714353104.4336175622147573.67556414  352824.9197409
2147280.27293572352427.350326061
#Sta/Elev= 30
       0 1895.36    29.7 1894.02    93.3 1886.72   121.8 1879.05   173.2 1871.05
   281.5 1866.64   345.5 1866.22  389.581859.025   398.5 1853.57   417.2 1853.45
   488.2 1853.68  504.111858.854     529 1865.54   549.6 1868.27   568.4 1875.78
   587.1 1886.86   589.5 1889.37   594.2 1898.17   598.3 1912.12   602.4 1922.98
   610.6 1935.47   618.7 1961.52   622.3 1968.62   643.2 1987.87   651.3 1999.18
   664.6 2010.32   682.4 2020.91   696.2  2026.5   776.4  2037.7   834.6  2042.9
#Mann= 5 ,-1 , 0
       0      .1       0  101.53     .05       0  341.91      .1       0
  389.58    .045       0  504.11      .1       0
Bank Sta=389.58,504.11
XS Rating Curve= 0 ,0
Exp/Cntr=0.3,0.1

Type RM Length L Ch R = 1 ,16256   ,637,627.3,615.2
XS GIS Cut Line= 2
2148134.43953447352951.6557078962147584.09220997352194.711355641
#Sta/Elev= 30
       0 1959.28   144.9 1908.99   222.1 1877.92   246.9 1870.67   291.5 1865.95
  301.051857.065   315.8 1852.74   352.4 1852.72  366.491855.535   398.5 1854.97
   407.9 1858.71   431.4 1857.25   461.9 1858.69   482.2 1857.51   489.9 1852.45
   508.9 1852.38   525.3 1853.73   538.9 1863.81   560.6  1869.5     570 1877.92
   581.7 1892.37   591.7 1901.63   598.2 1905.42   634.9 1919.59   663.9 1928.55
   708.5  1938.4     762 1946.92   798.6  1951.4   891.8 1957.98   935.9 1970.23
#Mann= 5 ,-1 , 0
       0      .1       0  122.73      .1       0  301.05    .045       0
  366.49      .1       0  643.45     .05       0
Bank Sta=301.05,366.49
XS Rating Curve= 0 ,0
Exp/Cntr=0.3,0.1

Type RM Length L Ch R = 1 ,15629   ,597.4,578.9,562.5
XS GIS Cut Line= 2
2148799.37029122352616.5861680662147941.73125847351870.058461636
#Sta/Elev= 30
       0 2109.08    28.7 2103.31    80.4 2087.86     154 2057.38   167.9 2049.18
   210.9 2029.42   237.7 2015.45   272.6 1994.54   281.9 1990.81   314.4 1969.49
     354 1945.87   388.4 1921.08   444.7 1883.62   456.3 1871.28  471.851858.374
   477.2 1853.28   480.6 1851.71   516.8 1851.69   576.2 1851.76   580.6 1853.16
  586.54  1857.9   606.7 1863.34   695.8 1861.79   749.3  1866.6   823.2 1867.05
   848.2 1869.38   872.6 1874.07  1000.5 1905.01  1093.5 1931.68    1137 1945.89
#Mann= 5 ,-1 , 0
       0      .1       0  471.85    .045       0  586.54      .1       0
  587.98     .05       0 1135.85      .1       0
Bank Sta=471.85,586.54
XS Rating Curve= 0 ,0
Exp/Cntr=0.3,0.1

Type RM Length L Ch R = 1 ,15050   ,756.7,863.5,937
XS GIS Cut Line= 2
2148926.10625821351871.7946786432148075.41176538351517.628064141
#Sta/Elev= 30
       0 1924.75    78.6 1922.91   132.6 1916.95   156.8 1917.01   174.5 1915.84
   210.1 1910.79     242 1902.49   256.3 1896.84   262.3 1893.22     274 1883.81
   298.9 1869.95  308.251861.455   318.2 1853.13   320.2 1851.84   323.8 1851.19
   419.7 1851.33   423.3 1851.79     434 1858.87  439.421861.174   443.7 1861.72
   476.6 1860.81   565.4 1865.25   583.2 1868.99   649.5  1887.2   702.6 1904.58
   732.5 1915.61   774.4 1928.12   825.1 1945.17   890.3 1964.47   921.5 1974.53
#Mann= 6 ,-1 , 0
       0      .1       0  297.34      .1       0  308.25    .045       0
  439.42     .05       0  566.48      .1       0  881.82      .1       0
Bank Sta=308.25,439.42
XS Rating Curve= 0 ,0
Exp/Cntr=0.3,0.1

Type RM Length L Ch R = 1 ,14187   ,810.1,775.2,724.8
XS GIS Cut Line= 2
2148960.82862972351804.0861526432149214.30056372350969.016956642
#Sta/Elev= 30
       0 1894.36     7.2 1890.84    31.2 1883.14    55.2 1879.17   147.7 1873.97
   281.4 1864.21   353.5 1862.72  360.891859.992     364 1856.33   367.2 1850.91
   376.2 1850.56   466.6 1850.62     470 1851.69   473.4 1856.24     4791858.628
   490.6 1863.16   503.4  1864.7   507.7 1867.16   511.8 1870.99     518 1879.09
   528.3 1897.61   535.2  1904.8   576.3 1934.28   600.3 1954.62     693 2019.36
     710 2028.09     734 2036.83     758 2047.34   802.6 2058.19   872.7 2068.78
#Mann= 3 ,-1 , 0
       0      .1       0  360.89    .045       0     479      .1       0
Bank Sta=360.89,479
XS Rating Curve= 0 ,0
Exp/Cntr=0.3,0.1

Type RM Length L Ch R = 1 ,13411   ,633.9,621.4,602.5
XS GIS Cut Line= 2
2149905.27293505351887.4196473962149591.03668688351014.155645892
#Sta/Elev= 30
       0 2021.16    29.6 2012.22      61 2000.02    78.4 1991.21    99.3 1978.39
   113.3 1973.49   164.2 1938.23   203.9 1914.53   224.8 1893.73   249.3 1874.66
   259.7 1861.53  265.631857.343   277.1 1849.81   371.3  1849.8   392.2 1853.08
  400.091857.055   406.2 1859.39   412.9 1859.82   465.4 1858.72   482.9 1863.77
   500.1 1863.31   531.7 1866.15   556.1 1870.23   608.4 1883.69   646.7 1891.54
   692.1 1897.82   751.4 1902.99   789.9 1913.94   880.4 1953.19   928.1 1969.48
#Mann= 3 ,-1 , 0
       0      .1       0  265.63    .045       0  400.09      .1       0
Bank Sta=265.63,400.09
XS Rating Curve= 0 ,0
Exp/Cntr=0.3,0.1