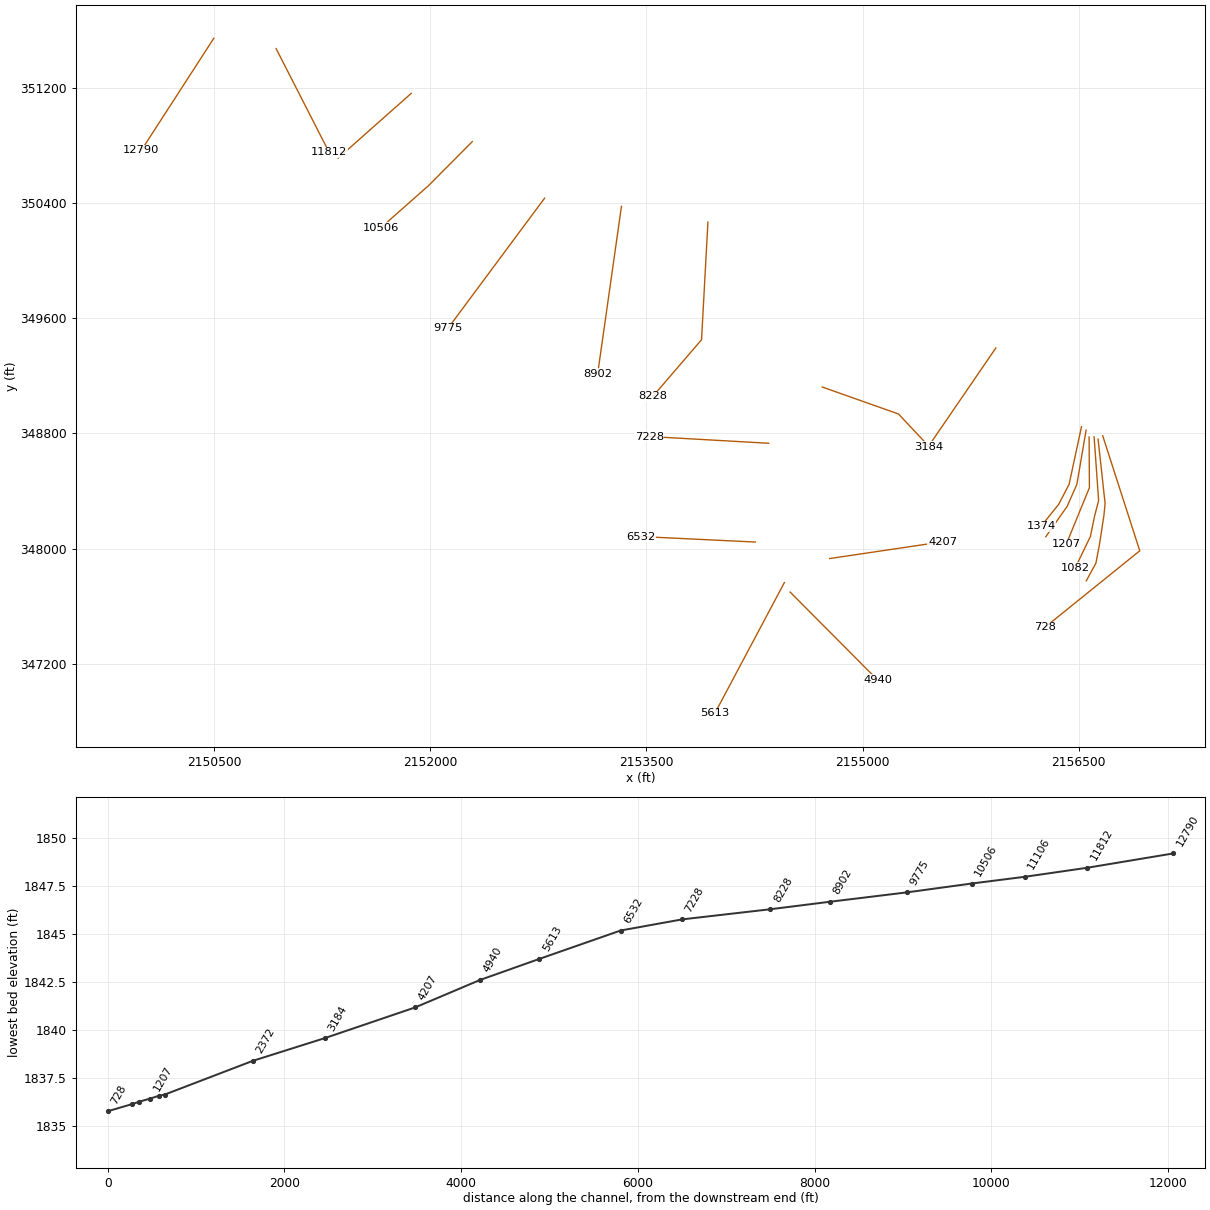
HEC-RAS study SPRINGCK.prj: SPRINGCK

--- SPRINGCK.g01 (geometry) --- (continued)

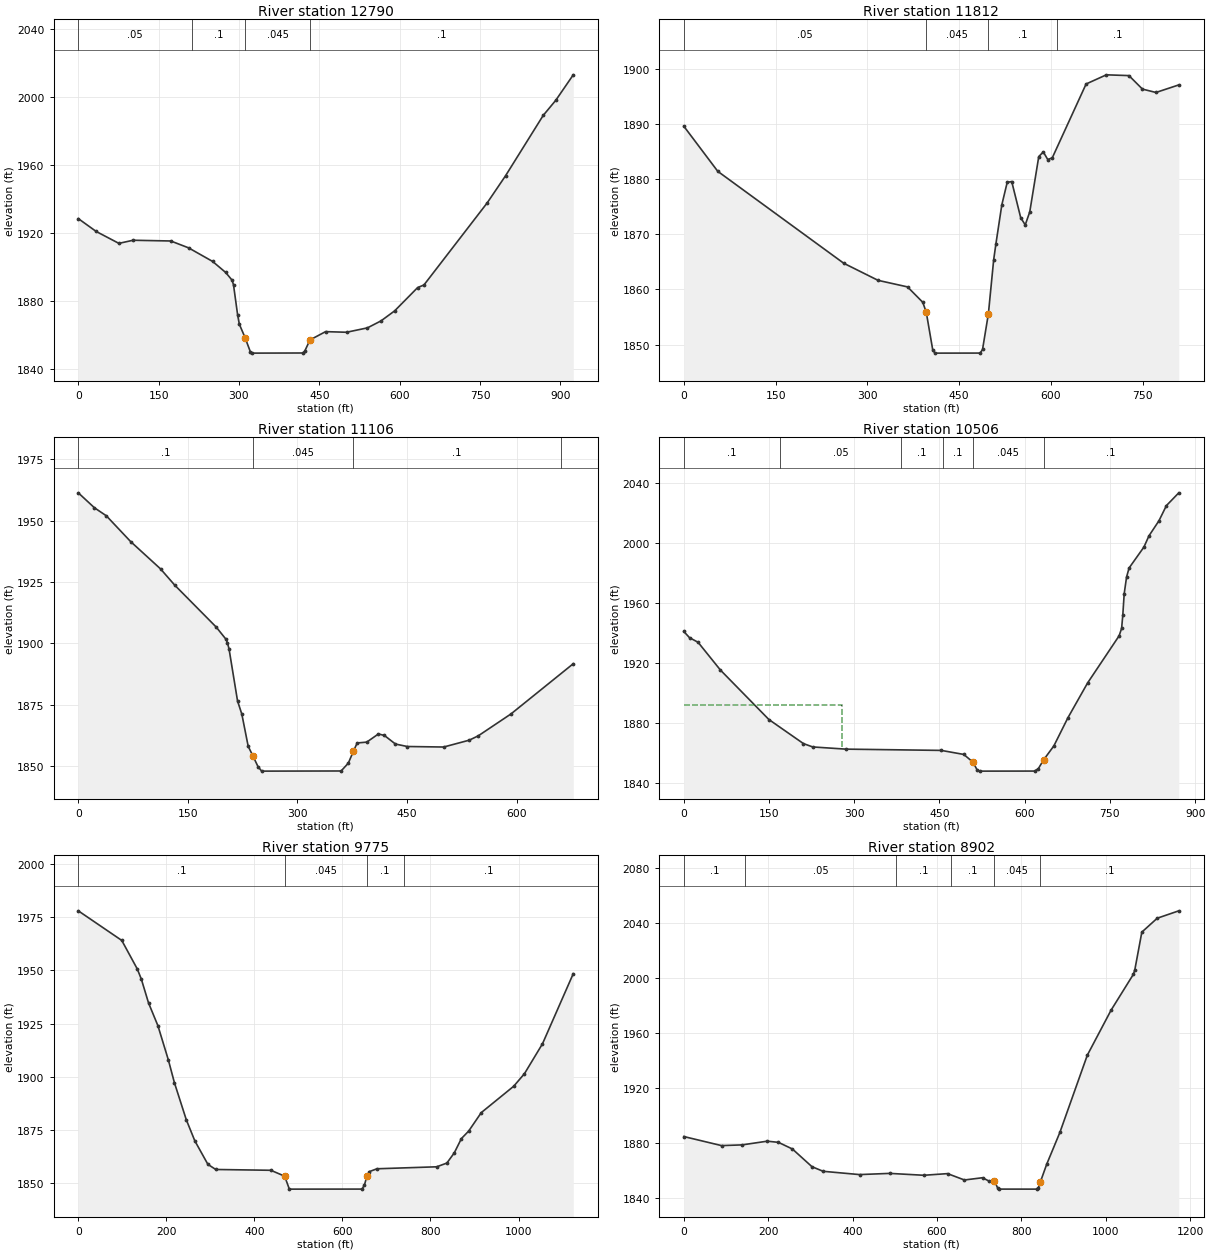
Type RM Length L Ch R = 1 ,12790   ,925,977.7,1035.8
XS GIS Cut Line= 2
2150499.02305989351541.9334617262149997.28685863 350765.89170672
#Sta/Elev= 30
       0 1928.29    33.5 1920.71    75.8 1913.73   102.3 1915.56   172.6 1915.13
   205.8 1911.11   250.8  1903.1   275.2 1896.61   287.2 1892.05   289.8 1889.29
   297.6 1871.38   300.7 1866.16  311.311858.353   321.1 1850.08     325 1849.19
   418.7 1849.27   422.6 1850.25  432.561856.955   461.7 1861.83   500.8 1861.46
   539.8 1864.04   565.2 1868.15   590.6 1874.03   633.6 1887.75   645.3 1889.25
   763.4 1937.53   797.7 1953.49     868 1988.97   891.5 1997.87   924.1 2012.83
#Mann= 4 ,-1 , 0
       0     .05       0  211.97      .1       0  311.31    .045       0
  432.56      .1       0
Bank Sta=311.31,432.56
XS Rating Curve= 0 ,0
Exp/Cntr=0.3,0.1

Type RM Length L Ch R = 1 ,11812   ,746.8,706.1,593.1
XS GIS Cut Line= 2
2150931.31451814351470.7528298052151299.37021247350750.266737983
#Sta/Elev= 30
       0 1889.59    55.5 1881.41   261.4 1864.74   317.5 1861.64   365.7 1860.45
   390.6 1857.66  396.341855.838     407 1848.96   410.7 1848.44   484.4 1848.45
   488.3  1849.1  497.881855.586   506.5 1865.36   510.2 1868.28   519.8 1875.32
   528.6  1879.4     536 1879.56   550.7    1873   558.1 1871.69   565.5 1874.06
   580.2 1884.08   587.6 1884.93   594.9 1883.55   602.3 1883.86   657.6 1897.25
   690.7 1898.91   727.6 1898.77   749.7 1896.32   771.8 1895.71   809.1 1897.08
#Mann= 4 ,-1 , 0
       0     .05       0  396.34    .045       0  497.88      .1       0
  609.82      .1       0
Bank Sta=396.34,497.88
XS Rating Curve= 0 ,0
Exp/Cntr=0.3,0.1

Type RM Length L Ch R = 1 ,11106   ,598,600.6,591.7
XS GIS Cut Line= 2
2151868.81461164351159.9890156392151361.87008747350710.336371645
#Sta/Elev= 30
       0 1961.35    22.1 1955.26    38.4 1951.99    71.6 1941.51   112.6 1930.36
     132 1923.75   188.8 1906.66   201.8 1901.84   204.1 1900.36   206.4 1897.71
     218 1876.57   223.9 1871.17   232.6 1858.07  238.971854.215     246 1849.82
     251 1847.97   359.8 1848.03   369.7 1851.24  376.461855.968   381.8 1859.44
   394.9 1859.79   410.9 1863.12   419.1 1862.49   434.2    1859   450.4    1858
   500.2 1857.79   535.2 1860.58   547.6 1862.36   592.3 1871.26   677.6 1891.73
#Mann= 4 ,-1 , 0
       0      .1       0  238.97    .045       0  376.46      .1       0
  660.18      .1       0
Bank Sta=238.97,376.46
XS Rating Curve= 0 ,0
Exp/Cntr=0.3,0.1

Type RM Length L Ch R = 1 ,10506   ,721.9,730.2,746.5
XS GIS Cut Line= 3
2152292.42564106350824.919475809 2151988.6063668350519.363984555
2151658.74514988350227.697245061
#Sta/Elev= 30
       0 1941.01    10.1 1936.85    25.1  1933.8    64.5 1915.19   149.7 1882.15
   210.6 1866.03   226.9 1863.79   285.2 1862.33   453.2 1861.48   492.8 1858.78
  509.171853.543   516.6 1848.14   521.7 1847.62   617.3 1847.66     624 1849.27
  633.111855.089   651.3 1864.48   676.1 1883.35   710.7  1906.6   766.2 1938.14
   770.6 1943.13   772.7 1952.23   775.1 1966.25   779.3 1977.45   783.7 1983.48
   809.9 1997.53   818.7 2004.99   836.3 2015.08   849.4 2025.22   871.2 2033.76
#Mann= 6 ,-1 , 0
       0      .1       0  169.35     .05       0  382.76      .1       0
   455.7      .1       0  509.17    .045       0  633.11      .1       0
#XS Ineff= 2 , 0
          278.44 1892.02
Permanent Ineff=
       F       F
Bank Sta=509.17,633.11
XS Rating Curve= 0 ,0
Exp/Cntr=0.3,0.1

Type RM Length L Ch R = 1 ,9775    ,839.6,873.1,906.6
XS GIS Cut Line= 2
 2152794.1618423350432.5583838972152124.02276264349529.780661896
#Sta/Elev= 30
       0 1978.04    98.8 1964.11     134  1950.7   143.2 1945.92   159.5 1934.76
   180.9 1923.99   204.4 1908.05   218.4 1897.17   245.3  1879.8   264.7 1869.87
   294.4 1858.81   312.2  1856.4   437.4 1856.02  468.741853.246   479.4 1847.16
   644.5 1847.18   649.9 1849.07  655.581853.168   661.1  1855.4   678.4 1856.73
   814.1 1857.66   837.2 1859.42     854  1864.2   870.2 1870.93   886.8 1874.48
   915.4 1883.15     989 1895.54  1013.5 1901.47  1054.4 1915.51  1124.3 1948.49
#Mann= 4 ,-1 , 0
       0      .1       0  468.74    .045       0  655.58      .1       0
  738.77      .1       0
Bank Sta=468.74,655.58
XS Rating Curve= 0 ,0
Exp/Cntr=0.3,0.1

Type RM Length L Ch R = 1 ,8902    ,669.1,673.8,678.3
XS GIS Cut Line= 2
2153327.11846101350375.5946621212153162.21720855349213.808524817
#Sta/Elev= 30
       0 1884.89    89.4 1878.31   138.1 1878.82   197.8 1881.52   224.3 1880.67
   257.4 1875.84   303.8 1862.97   330.3 1859.63   416.5 1857.24   488.2 1858.11
   568.9 1856.74   625.2 1857.94   665.2 1853.31   708.1 1854.95   724.6 1852.34
   736.4 1852.57   744.5 1847.16   747.8 1846.69   837.3 1846.67   840.6 1847.82
   845.1 1851.75   860.5 1864.94   891.5 1887.86   956.6 1944.06  1012.9 1976.76
    1066 2002.93  1069.3  2006.3  1085.8 2033.47  1122.3 2043.58  1173.4 2048.95
#Mann= 6 ,-1 , 0
       0      .1       0   145.9     .05       0  503.72      .1       0
  634.32      .1       0   736.4    .045       0   845.1      .1       0
Bank Sta=736.4,845.1
XS Rating Curve= 0 ,0
Exp/Cntr=0.3,0.1

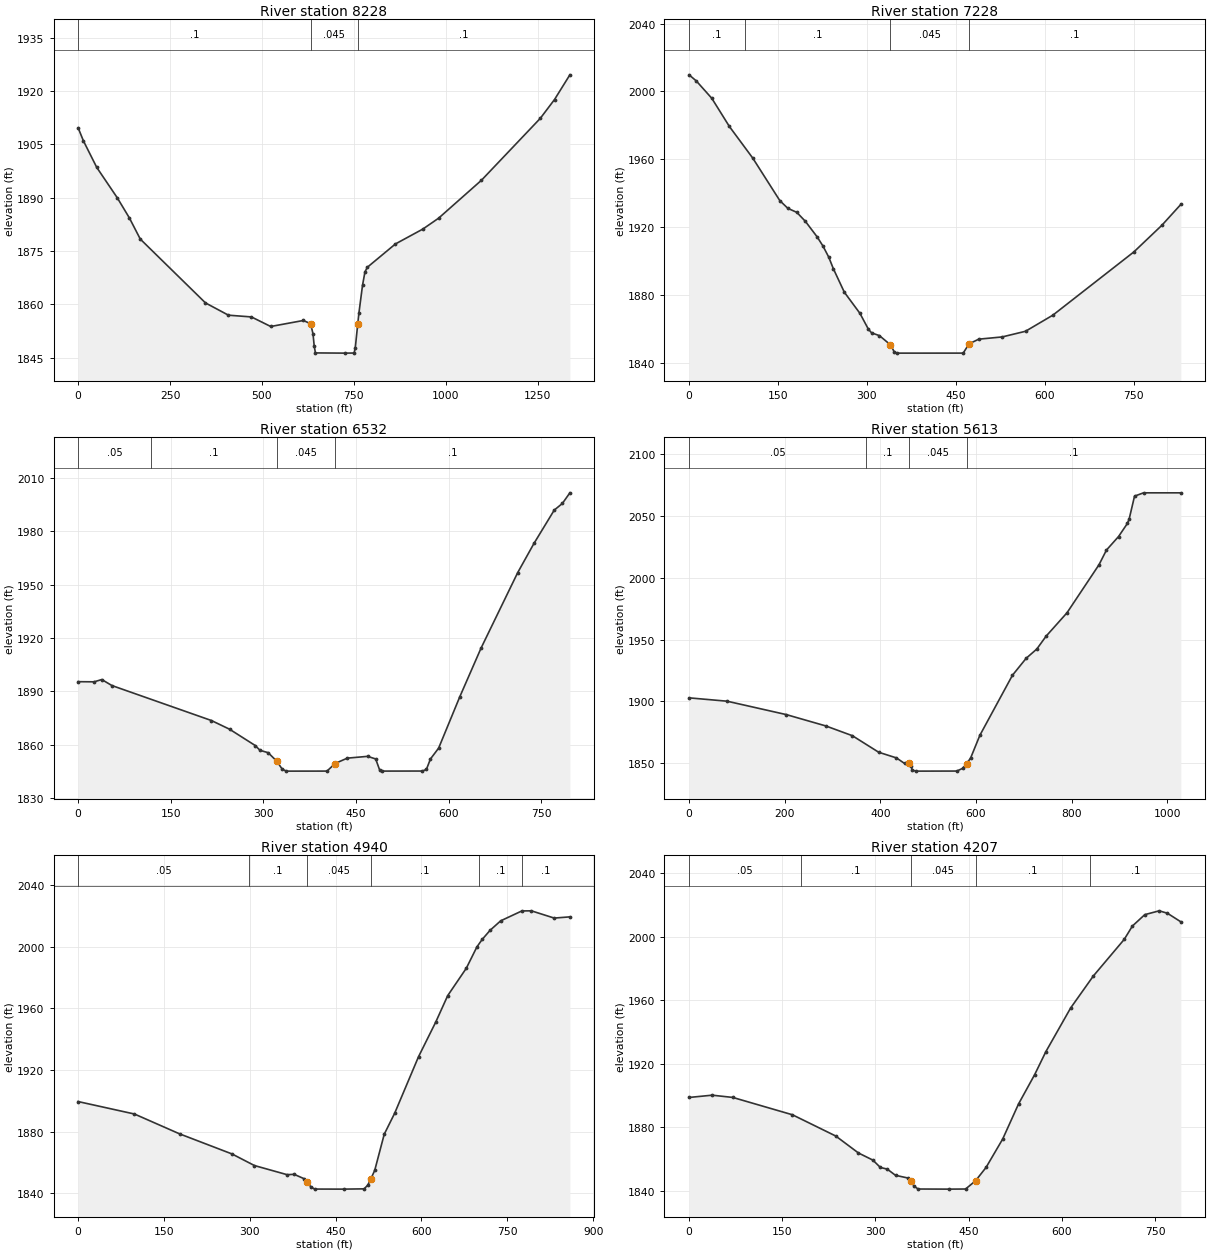
Type RM Length L Ch R = 1 ,8228    ,1107.2,1000.5,913.9
XS GIS Cut Line= 3
2153927.02819714350266.4985558052153882.62836177349449.522555201
2153544.16165464349055.822292224
#Sta/Elev= 30
       0 1909.65    14.5 1905.95    50.7  1898.5   106.5 1889.96   139.4  1884.3
     169 1878.36   346.4  1860.4   408.8 1856.95   471.3 1856.46   523.8 1853.77
   612.5 1855.46   632.3 1854.56   638.8  1851.7   642.1 1848.23   645.4 1846.34
   725.5 1846.28   750.5 1846.31   753.8  1847.8   760.4 1854.43   763.7 1857.59
   773.5 1865.39   780.1 1869.14   786.7 1870.44     863 1876.99   937.5 1881.17
   980.1 1884.21  1096.9  1894.9    1257 1912.32  1295.6  1917.6  1337.4 1924.55
#Mann= 3 , 0 , 0
       0      .1       0   632.3    .045       0   760.4      .1       0
Bank Sta=632.3,760.4
XS Rating Curve= 0 ,0
Exp/Cntr=0.3,0.1

Type RM Length L Ch R = 1 ,7228    ,694.9,695.5,695.4
XS GIS Cut Line= 2
2154347.98124123348731.1697263122153519.85625705348778.044632554
#Sta/Elev= 30
       0 2009.79    12.2 2006.19    38.4 1995.92      68 1979.34   107.5 1960.67
   153.1 1935.64   166.6  1931.1   181.7 1928.73   196.2 1923.43   215.9 1914.33
   225.8 1908.91   235.6 1902.34   243.3 1895.56   261.9 1881.65   288.2 1869.21
   302.4  1859.9   307.9 1857.69   321.1 1856.06   339.7 1850.65     346 1846.56
   350.6 1845.75   462.4 1845.76   472.2 1851.19   488.6 1853.98   528.1 1855.29
   567.5 1858.63   613.6 1868.12   750.3 1905.41   797.5  1921.1   829.5  1933.4
#Mann= 4 ,-1 , 0
       0      .1       0    94.5      .1       0   339.7    .045       0
   472.2      .1       0
Bank Sta=339.7,472.2
XS Rating Curve= 0 ,0
Exp/Cntr=0.3,0.1

Type RM Length L Ch R = 1 ,6532    ,861.9,919.8,986
XS GIS Cut Line= 2
2154255.96731764  348045.40567792153460.82848798348083.600155309
#Sta/Elev= 30
       0 1895.42    25.8 1895.34    38.3 1896.62    54.7 1893.25   215.7 1873.61
   245.2 1868.71   286.7 1859.56   294.5 1856.84   307.6 1855.54   321.2 1850.89
   330.6  1846.2   337.2 1845.17   402.9 1845.19     416 1849.45   435.7 1852.46
   468.6 1853.47   481.7 1852.01   488.3 1845.63   491.6 1845.19   557.3 1845.22
   563.8 1846.11   570.4 1852.02   583.6 1858.08   617.9 1886.96   652.4 1914.37
   711.6 1956.68   737.9 1973.06   770.8 1991.83   783.9 1995.53   796.1 2001.52
#Mann= 4 ,-1 , 0
       0     .05       0  118.45      .1       0   321.2    .045       0
     416      .1       0
Bank Sta=321.2,416
XS Rating Curve= 0 ,0
Exp/Cntr=0.3,0.1

Type RM Length L Ch R = 1 ,5613    ,597,672.5,743.6
XS GIS Cut Line= 2
2154457.35635056347764.1555842312153974.71722397346856.169539317
#Sta/Elev= 30
       0 1902.94    79.5 1900.23   203.3  1889.4   285.7 1880.26   341.5 1872.33
   396.5 1858.96   433.6 1854.38   450.6 1849.89   459.7 1850.06   463.4 1848.19
   467.1 1844.44   474.5 1843.69     560 1843.75   571.9 1845.92   580.4 1849.67
   588.9 1854.43   608.1 1872.68   676.2 1921.21   704.9 1934.93   727.2 1942.44
   746.6 1952.81   790.3 1971.73   857.2 2010.57   872.8 2022.45   898.1 2033.39
   916.7 2044.04   920.4 2047.74   931.5 2066.04   950.4 2068.72  1028.3 2068.71
#Mann= 4 ,-1 , 0
       0     .05       0  369.54      .1       0   459.7    .045       0
   580.4      .1       0
Bank Sta=459.7,580.4
XS Rating Curve= 0 ,0
Exp/Cntr=0.3,0.1

Type RM Length L Ch R = 1 ,4940    ,681.5,733.6,780.4
XS GIS Cut Line= 2
2154497.28671689347698.1836033172155103.18970455347088.808509722
#Sta/Elev= 30
       0 1899.48    98.4 1891.39   177.2 1878.51   268.9 1865.44   308.1 1857.91
   365.1 1851.98   377.5  1852.2   394.5 1849.42   399.9 1847.14   406.9 1843.99
   413.2 1842.63   464.3 1842.59   499.7 1842.77   506.2  1845.2   511.3 1849.07
   518.3 1854.81   534.9 1878.26   553.1 1891.87   594.8 1928.61     625  1951.2
   645.8 1968.31   678.3 1986.09   696.8 1999.93     706  2004.8   719.9 2010.76
   738.4 2016.91   775.4 2023.33     792  2023.4   831.9 2018.69   859.3 2019.48
#Mann= 6 ,-1 , 0
       0     .05       0  298.51      .1       0   399.9    .045       0
   511.3      .1       0  700.94      .1       0  774.92      .1       0
Bank Sta=399.9,511.3
XS Rating Curve= 0 ,0
Exp/Cntr=0.3,0.1

Type RM Length L Ch R = 1 ,4207    ,1058.8,1022.6,993.3
XS GIS Cut Line= 2
2154771.59227064347930.8222456432155554.57856555348047.141894892
#Sta/Elev= 30
       0 1898.91    37.1 1900.34    70.3 1898.93   166.4    1888   236.1 1874.62
   272.6 1863.94   295.8 1859.46     308  1854.8     319 1853.77   332.3 1849.86
   352.2 1848.17   357.1 1846.36   362.1 1843.06   368.7 1841.23   417.8 1841.16
   445.1 1841.23   461.1 1846.39     478 1854.79   504.8 1872.69   530.4 1894.85
   556.4 1913.35   574.4 1927.81   614.2 1955.26   650.7  1975.4   700.5  1998.5
   713.7 2006.93   733.6 2014.08   756.8 2016.48     770 2014.96   791.6 2009.56
#Mann= 5 ,-1 , 0
       0     .05       0  179.57      .1       0   357.1    .045       0
   461.1      .1       0  645.34      .1       0
Bank Sta=357.1,461.1
XS Rating Curve= 0 ,0
Exp/Cntr=0.3,0.1

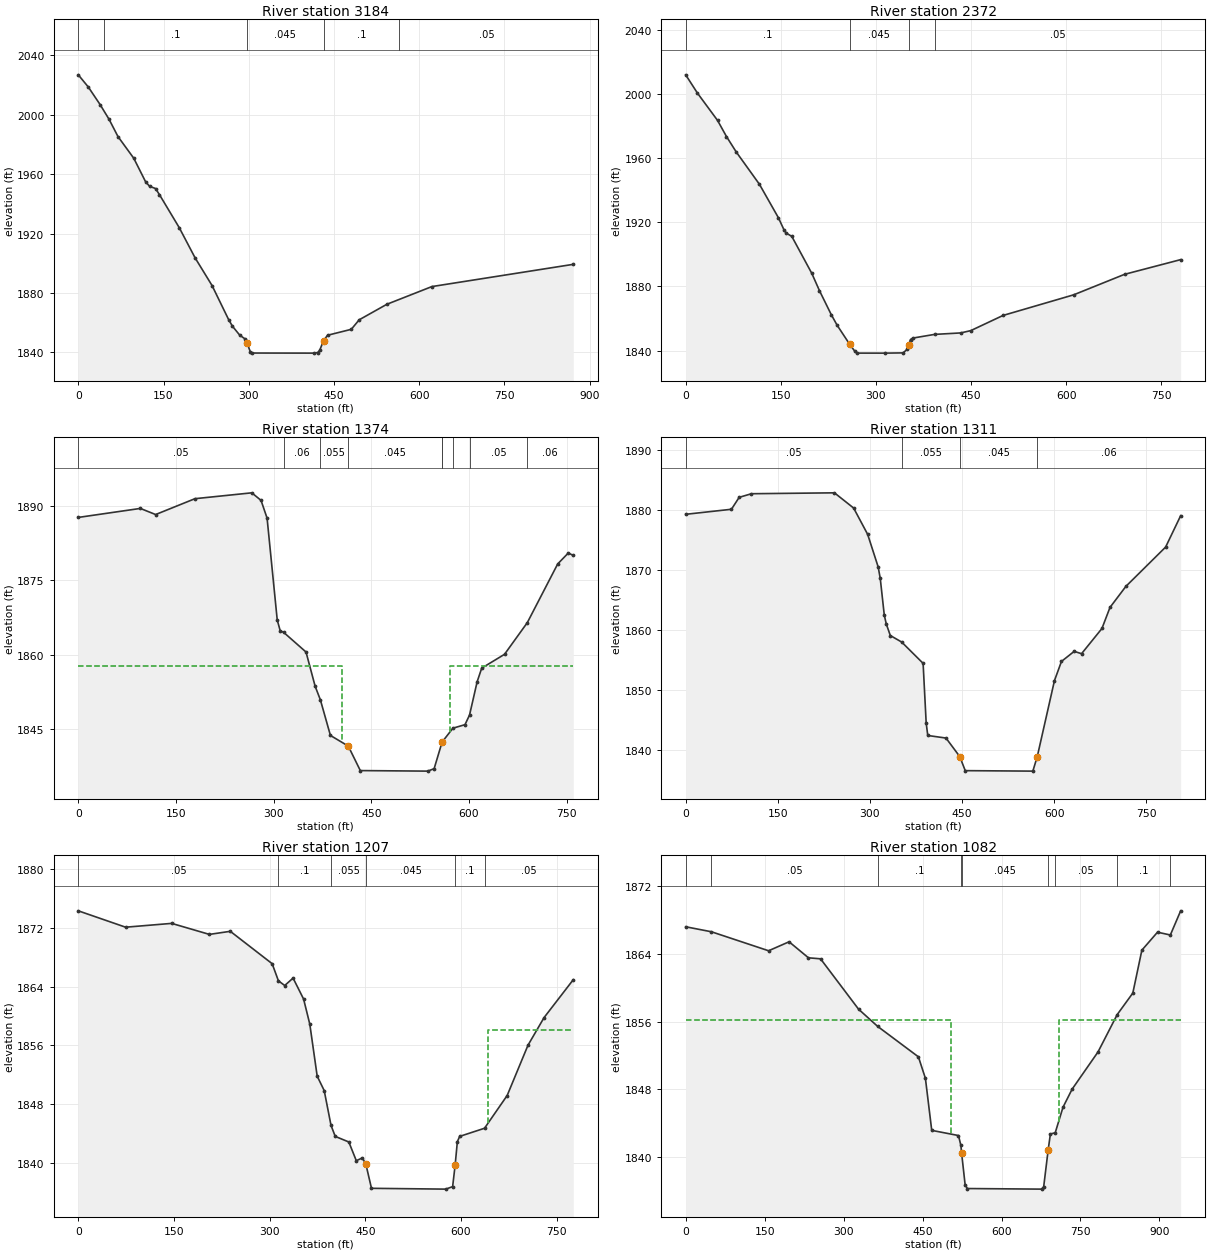
Type RM Length L Ch R = 1 ,3184    ,929.1,812.1,716.4
XS GIS Cut Line= 3
2154719.50904147349121.794601232 2155249.0230743348934.294648141
2155460.82842498 348708.60021764
#Sta/Elev= 30
       0 2026.97    17.6 2018.78    38.5 2006.87    54.3 1996.93    69.8 1985.43
    97.7 1970.76   118.5 1954.92   125.5  1951.9   135.9 1950.41   142.9 1946.26
   177.7 1924.05   205.5 1903.78   235.4  1885.1   264.7 1862.07   271.4 1857.65
   284.2 1851.64   292.6 1849.38   297.1 1846.18     303 1840.29   306.5 1839.62
   414.4 1839.56   421.3 1839.96   424.8 1841.39   431.8 1848.04   438.7 1851.59
   480.5 1855.59   494.4    1862   543.1 1872.45   622.4 1884.38   871.2 1899.35
#Mann= 5 ,-1 , 0
       0      .1       0    45.4      .1       0   297.1    .045       0
   431.8      .1       0  565.28     .05       0
Bank Sta=297.1,431.8
XS Rating Curve= 0 ,0
Exp/Cntr=0.3,0.1

Type RM Length L Ch R = 1 ,2372    ,994.4,998.2,1018.1
XS GIS Cut Line= 2
2155924.37014881349392.6280490612155483.39793363348748.530583978
#Sta/Elev= 30
       0 2011.97    18.5 2000.58    50.2 1983.56    64.3 1973.49    79.8  1963.8
   116.3 1943.69   146.3 1922.77   155.4 1914.94   158.7  1913.2   167.3 1911.22
   198.9 1888.12     211 1877.31   229.5 1862.44   238.8 1855.79   258.7 1843.84
   266.7 1839.55   270.7 1838.39   314.5 1838.38   342.8 1838.53   349.5 1840.82
   351.6 1843.51   354.6 1846.87   358.1 1847.76   392.4 1850.06   433.7 1850.98
   449.6 1852.42   500.5 1861.89   611.9 1874.75   692.1 1887.53   780.6  1896.7
#Mann= 4 ,-1 , 0
       0      .1       0   258.7    .045       0   351.6      .1       0
   392.4     .05       0
Bank Sta=258.7,351.6
XS Rating Curve= 0 ,0
Exp/Cntr=0.5,0.3

Type RM Length L Ch R = 1 ,1374    ,54.4,62.6,61
XS GIS Cut Line= 4
2156518.40931505348845.831898555 2156432.2982668348445.832042396
2156360.07597031348306.9428844752156237.96958722348155.438266233
#Sta/Elev= 30
       0 1887.68    95.3 1889.49   118.8 1888.26   179.2 1891.45   266.5 1892.63
   280.7 1891.11     290 1887.53   305.6 1867.03   310.1  1864.9   315.7 1864.52
   349.8 1860.59   363.8 1853.71   371.9 1850.95   387.3  1843.8   414.7 1841.66
   433.2 1836.73   536.9 1836.62   546.6 1837.12   558.8 1842.46   558.9 1842.48
   575.4 1845.26     594 1845.97     601 1847.92   612.7 1854.63   619.7 1857.35
   654.7 1860.13   689.7  1866.5   736.4 1878.32   752.7 1880.52   760.3 1880.03
#Mann= 9 ,-1 , 0
       0     .05       0   315.7     .06       0   371.9    .055       0
   414.7    .045       0   558.8    .045       0   558.9    .055       0
   575.4     .06       0     601     .05       0   689.7     .06       0
#XS Ineff= 2 , 0
             405  1857.8   571.4          1857.8
Permanent Ineff=
       F       F
Bank Sta=414.7,558.8
XS Rating Curve= 0 ,0
Exp/Cntr=0.5,0.3

Type RM Length L Ch R = 1 ,1311    ,96.3,104.5,105.8
XS GIS Cut Line= 4
2156550.46961838348822.1049118942156486.23352639348445.369116813
2156418.52500039348292.5912071472156270.95574172348082.521745399
#Sta/Elev= 30
       0 1879.36    74.5  1880.2    87.1 1882.19   107.1 1882.79   242.2 1882.94
   273.5  1880.4   296.3 1876.02   313.4  1870.6   316.8 1868.69   323.4 1862.54
   326.7 1861.06   333.2 1859.16   351.7 1858.07   386.6 1854.52   391.6 1844.57
   394.2  1842.5   423.9 1842.07   446.3 1838.98   455.2 1836.64   565.3 1836.56
   572.5 1838.99   600.5 1851.65   611.9 1854.84   632.6 1856.52   644.6 1856.13
   677.8 1860.33   690.9 1863.84   716.8 1867.35   781.5  1873.9     806 1879.13
#Mann= 4 ,-1 , 0
       0     .05       0   351.7    .055       0   446.3    .045       0
   572.5     .06       0
Bank Sta=446.3,572.5
XS Rating Curve= 0 ,0
Exp/Cntr=0.5,0.3

Type RM Length L Ch R = 1 ,1207    ,111.1,125,146.2
XS GIS Cut Line= 3
2156571.26189964348774.3625533132156573.43217088348422.800264314
 2156412.8416128348030.005118147
#Sta/Elev= 30
       0 1874.31    74.2 1872.08   146.4  1872.6   205.5  1871.1   238.3 1871.52
   303.9 1867.11   313.7 1864.78   323.6 1864.14   336.7 1865.15   353.2 1862.29
   362.9 1858.88   374.5 1851.79   385.5 1849.83   396.2 1845.08   402.8 1843.59
   424.1 1842.83   435.8 1840.28   445.4 1840.67   450.9 1839.77   459.6 1836.52
   576.1 1836.41   586.8 1836.75   590.7 1839.65   594.2 1842.87   597.8 1843.59
   636.8  1844.7   672.3 1849.16     705 1856.02   730.2 1859.78   775.9 1864.93
#Mann= 6 ,-1 , 0
       0     .05       0   313.7      .1       0   396.2    .055       0
   450.9    .045       0   590.7      .1       0   636.8     .05       0
#XS Ineff= 2 , 0
                          642.27         1858.12
Permanent Ineff=
       F       F
Bank Sta=450.9,590.7
XS Rating Curve= 0 ,0
Exp/Cntr=0.5,0.3

Type RM Length L Ch R = 1 ,1082    ,65.5,79.5,76.4
XS GIS Cut Line= 5
2156606.02528155348775.2300056372156637.27521905348334.257790476
 2156608.5715363348222.568053231 2156580.0991523348083.679223388
2156475.23814155347866.549408317
#Sta/Elev= 30
       0 1867.18    48.9 1866.59   157.5 1864.35   196.4 1865.41   233.2 1863.52
   256.2  1863.4   328.4 1857.46   364.7 1855.43   442.1 1851.84   455.4  1849.3
   467.4 1843.17   518.2 1842.56   522.8 1841.39   524.1 1840.52   530.9 1836.72
   535.2 1836.31   676.1 1836.24   680.1 1836.53   688.5 1840.81   692.8 1842.74
     702 1842.89   716.8  1845.9     734 1848.02   783.3 1852.42   819.8 1856.83
   849.4 1859.36   866.6 1864.42   896.3 1866.54   920.7 1866.21   940.3 1869.06
#Mann= 9 ,-1 , 0
       0      .1       0    48.9     .05       0   364.7      .1       0
   522.8    .045       0   524.1    .045       0   688.5      .1       0
     702     .05       0   819.8      .1       0   920.7    .055       0
#XS Ineff= 2 , 0
           504.1  1856.2   708.5          1856.2
Permanent Ineff=
       F       F
Bank Sta=524.1,688.5
XS Rating Curve= 0 ,0
Exp/Cntr=0.5,0.3

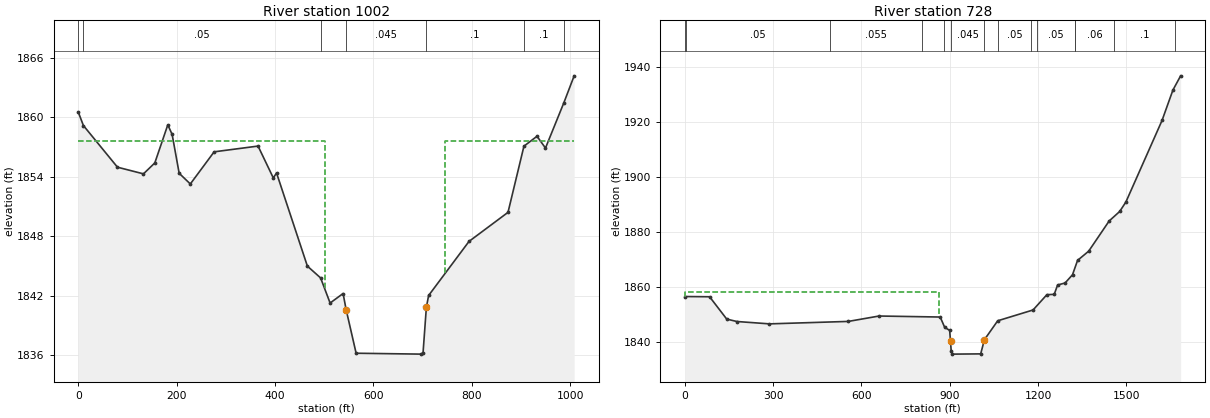
Type RM Length L Ch R = 1 ,1002    ,342.7,273.8,227
XS GIS Cut Line= 6
2156633.57148631348759.6050368992156682.18260956348313.771610975
2156673.84929289348229.0496675672156643.29357973348029.049411401
2156618.29362972347898.4938982282156551.62709638347776.271701723
#Sta/Elev= 30
       0  1860.5    10.3 1859.16    79.6 1854.96   132.4 1854.29   155.5 1855.39
   181.9 1859.23   190.7 1858.27     205 1854.35   227.7 1853.27   276.1 1856.51
   365.4 1857.09   396.4 1853.88     403 1854.38   465.7 1844.99   492.6  1843.8
   511.9 1841.27   538.3 1842.23   544.5  1840.6   564.8 1836.21   697.6 1836.12
   700.9 1836.27   707.6 1840.83   712.2 1842.03   794.3 1847.48   873.6 1850.41
     906 1857.08   932.6 1858.08   949.8 1856.89   987.2 1861.46  1008.1 1864.17
#Mann= 7 ,-1 , 0
       0      .1       0    10.3     .05       0   492.6      .1       0
   544.5    .045       0   707.6      .1       0     906      .1       0
   987.2    .055       0
#XS Ineff= 2 , 0
          500.89 1857.57     746         1857.57
Permanent Ineff=
       F       F
Bank Sta=544.5,707.6
XS Rating Curve= 0 ,0
Exp/Cntr=0.5,0.3

Type RM Length L Ch R = 1 ,728     ,733.35,728.3,727.13
XS GIS Cut Line= 3
2156665.68953231348783.252955481 2156922.6339003347984.641691804
2156264.64801155347453.391770065
#Sta/Elev= 30
       0 1856.65    84.2 1856.57   142.5 1848.46   176.9 1847.59   287.7 1846.73
   555.5 1847.62   660.2 1849.58   867.8 1849.21     883 1845.46   899.9 1844.37
   902.8 1840.39   905.1 1836.83   908.3 1835.75  1005.3 1835.84    1018 1840.99
  1063.1 1847.85  1183.2 1851.77  1230.2 1857.32  1255.1 1857.44  1266.7 1860.84
    1292 1861.56  1317.3 1864.56  1334.4 1869.76  1372.2 1873.11  1441.8 1884.07
  1477.6 1887.52  1498.7 1890.96  1621.4 1920.53  1658.4 1931.57  1684.6 1936.74
#Mann= 14 ,-1 , 0
       0      .1       0     4.8     .05       0  492.39    .055       0
  806.82      .1       0  880.26    .025       0   902.8    .045       0
    1018      .1       0 1063.57     .05       0 1177.91      .1       0
 1195.26     .05       0 1326.74    .055       0 1326.96     .06       0
 1458.65      .1       0    1667     .06       0
#XS Ineff= 2 , 0
          864.86 1858.44
Permanent Ineff=
       F       F
Bank Sta=902.8,1018
XS Rating Curve= 0 ,0
Exp/Cntr=0.3,0.1
LCMann Table=0

Chan Stop Cuts=-1
Use User Specified Reach Order=0
Composite Channel Slope=5